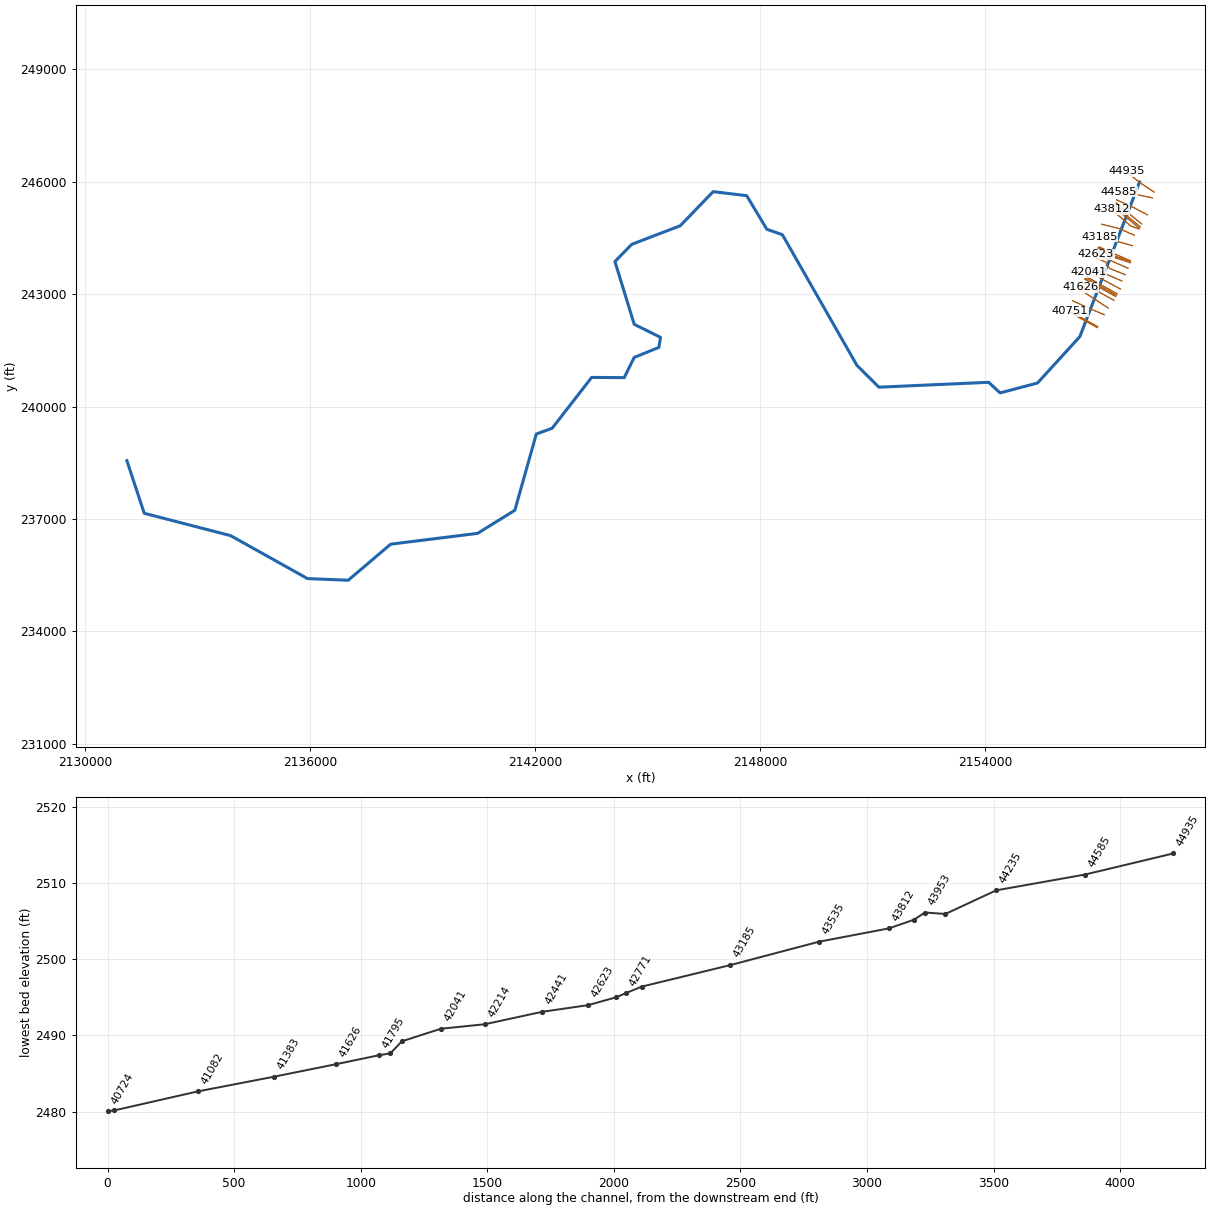
--- LAURELCK3.prj (project) ---

Proj Title=LAURELCK3
Current Plan=p01
Default Exp/Contr=0,0
English Units
Geom File=g01
Flow File=f01
Plan File=p01
BEGIN DESCRIPTION:
Stream Name: Laurel Creek (I)
Flood Zone: Approximate
Monroe County, West Virginia
HEC-RAS Version: 5.0.7
Vertical Datum: NAVD88
Projection: NAD 1983 StatePlane West Virginia S FIPS 4702 (US Feet)
LiDAR: 2016, 1-meter
Land Use: 2016 NLCD
Hydrologic Method:
SIR2010-5033 regression equations
END DESCRIPTION:
DSS File=dss
DSS Export Rating Curves= 0
DSS Export Rating Curve Sorted= 0
DSS Export Volume Flow Curves= 0
DXF OffsetX= 0
DXF OffsetY= 0
DXF ScaleX= 0
DXF ScaleY= 0

--- LAURELCK3.p01 (plan) ---

Plan Title=Floodplain
Program Version=5.07
Short Identifier=Floodplain
Geom File=g01
Flow File=f01
Subcritical Flow
K Sum by GR= 0
Std Step Tol= 0.01
Critical Tol= 0.01
Num of Std Step Trials= 20
Max Error Tol= 0.3
Flow Tol Ratio= 0.001
Split Flow NTrial= 30
Split Flow Tol= 0.02
Split Flow Ratio= 0.02
Log Output Level= 0
Friction Slope Method= 1
Unsteady Friction Slope Method= 2
Unsteady Bridges Friction Slope Method= 1
Parabolic Critical Depth
Global Vel Dist= 0 , 0 , 0
Global Log Level= 0
CheckData=True
Encroach Param=-1 ,0,0, 0
Computation Interval=0.1SEC
Output Interval=1MIN
Instantaneous Interval=Max Profile
Mapping Interval=1HOUR
Computation Time Step Use Courant=        0
Computation Time Step Use Time Series=    0
Computation Time Step Count To Double=0
Computation Time Step Max Doubling=0
Computation Time Step Max Halving=0
Computation Time Step Residence Courant=0
Run HTab= 0
Run UNet= 0
Run Sediment= 0
Run PostProcess= 0
Run WQNet= 0
Run RASMapper= 0
UNET Theta= 0
UNET Theta Warmup= 0
UNET ZTol= 0
UNET ZSATol= 0
UNET MxIter= 0
UNET Max Iter WO Improvement= 0
UNET MaxInSteps= 0
UNET DtIC= 0
UNET DtMin= 0
UNET MaxCRTS= 0
UNET WFStab= 0
UNET SFStab= 0
UNET WFX= 1
UNET SFX= 1
UNET 1D Methodology=Finite Difference
UNET DSS MLevel= 1
UNET Pardiso=0
UNET DZMax Abort= 0
UNET Use Existing IB Tables= 0
UNET Froude Reduction=False
UNET Froude Limit= 0
UNET Froude Power= 0
UNET D1 Cores= 0
UNET D2 Coriolis=0
UNET D2 Cores= 0
UNET D2 Theta= 1
UNET D2 Theta Warmup= 1
UNET D2 Z Tol= 0.01
UNET D2 Volume Tol= 0.01
UNET D2 Max Iterations= 20
UNET D2 Equation= 0
UNET D2 RampUpFraction=0.1
UNET D2 TimeSlices= 1
UNET D2 BCVolumeCheck=0
UNET D1D2 MaxIter= 0
UNET D1D2 ZTol=0.01
UNET D1D2 QTol=0.1
UNET D1D2 MinQTol=1
DSS File=dss
Write IC File= 0
Write IC File at Fixed DateTime=0
Write IC File at Sim End=0
Echo Input=False
Echo Parameters=False
Echo Output=False
Write Detailed= 0
HDF Write Warmup=0
HDF Write Time Slices=0
HDF Flush=0
HDF Face Node Velocities=0
HDF Compression= 1
HDF Chunk Size= 1
HDF Spatial Parts= 1
HDF Use Max Rows=0
HDF Fixed Rows= 1
Calibration Method= 0
Calibration Iterations= 20
Calibration Max Change=0.05
Calibration Tolerance=0.2
Calibration Maximum=1.5
Calibration Minimum=0.5
Calibration Optimization Method= 1
WQ AD Non Conservative
WQ ULTIMATE=-1
WQ Max Comp Step=1HOUR
WQ Output Interval=15MIN
WQ Output Selected Increments= 0
WQ Output face flow=0
WQ Output face velocity=0
WQ Output face area=0
WQ Output face dispersion=0
WQ Output cell volume=0
WQ Output cell surface area=0
WQ Output cell continuity=0
WQ Output cumulative cell continuity=0
WQ Output face conc=0
WQ Output face dconc_dx=0
WQ Output face courant=0
WQ Output face peclet=0
WQ Output face adv mass=0
WQ Output face disp mass=0
WQ Output cell mass=0
WQ Output cell source sink temp=0
WQ Output nsm pathways=0
WQ Output nsm derived pathways=0
WQ Output MaxMinRange=-1
WQ Daily Max Min Mean=-1
WQ Daily Range=0
WQ Daily Time=0
WQ Create Restart=0
WQ Fixed Restart=0
WQ System Summary=0
WQ Write To DSS=0
WQ Use Fixed Temperature=0
Sorting and Armoring Iterations= 10
XS Update Threshold= 0.02
Bed Roughness Predictor= 0
Hydraulics Update Threshold= 0.02
Energy Slope Method= 1
Volume Change Method= 1
Sediment Retention Method= 0
XS Weighting Method= 0
Number of US Weighted Cross Sections= 1
Number of DS Weighted Cross Sections= 1
Upstream XS Weight=0
Main XS Weight=1
Downstream XS Weight=0
Number of DS XS's Weighted with US Boundary= 1
Upstream Boundary Weight= 1
Weight of XSs Associated with US Boundary= 0
Number of US XS's Weighted with DS Boundary= 1
Downstream Boundary Weight= 0.5
Weight of XSs Associated with DS Boundary= 0.5
Percentile Method= 0
Sediment Output Level= 3
Mass or Volume Output= 0
Output Increment Type= 1
Profile and TS Output Increment= 1
XS Output Flag= 0
XS Output Increment= 10
Write Gradation File= 0
Read Gradation Hotstart= 0
Write HDF5 File= 1
Write Binary Output= 1
Write DSS Sediment File= 0
SV Curve= 0
Specific Gage Flag= 0

--- LAURELCK3.f01 (steady flow) ---

Flow Title=Flow
Program Version=5.07
Number of Profiles= 6
Profile Names=01pct,10pct,04pct,02pct,0_2pct,01plus
River Rch & RM=LAURELCK3,Main            ,44935
     627     332     441     531     874     927
River Rch & RM=LAURELCK3,Main            ,43185
     682     363     481     579     950    1010
River Rch & RM=LAURELCK3,Main            ,42214
     757     405     535     643    1050    1120
River Rch & RM=LAURELCK3,Main            ,41082
     824     441     583     700    1140    1220
River Rch & RM=LAURELCK3,Main            ,38414
     882     474     625     749    1220    1300
River Rch & RM=LAURELCK3,Main            ,37978
     920     495     653     782    1270    1360
River Rch & RM=LAURELCK3,Main            ,37302
    1430     785    1030    1220    1970    2120
River Rch & RM=LAURELCK3,Main            ,36835
    1510     830    1080    1290    2070    2240
River Rch & RM=LAURELCK3,Main            ,34782
    1630     895    1170    1390    2230    2410
River Rch & RM=LAURELCK3,Main            ,29528
    1950    1080    1410    1670    2660    2890
River Rch & RM=LAURELCK3,Main            ,29278
    2040    1130    1470    1750    2790    3020
River Rch & RM=LAURELCK3,Main            ,26368
    2270    1260    1640    1940    3090    3360
River Rch & RM=LAURELCK3,Main            ,22861
    2500    1400    1810    2140    3400    3700
River Rch & RM=LAURELCK3,Main            ,16214
    2670    1500    1930    2290    3620    3950
River Rch & RM=LAURELCK3,Main            ,11315
    2960    1670    2150    2540    4010    4380
Boundary for River Rch & Prof#=LAURELCK3,Main            , 1
Up Type= 0
Dn Type= 3
Dn Slope=0.010546
DSS Import GetInterval= 0
DSS Import GetPeak= 0
DSS Import FillOption= 0

--- LAURELCK3.g01 (geometry) ---

Geom Title=Geometry
Program Version=5.07

River Reach=LAURELCK3       ,Main
Reach XY= 30
     2158128.923      245996.101     2156534.305       241866.76
     2155404.965      240628.045     2154406.701      240364.156
     2154102.882      240647.142     2151174.468      240517.046
     2150587.604      241099.226     2148598.888      244587.941
     2148183.958      244732.906     2147646.631      245629.608
     2146751.666      245737.246     2145875.798      244828.392
     2144578.923      244330.129     2144131.007      243870.927
     2144645.763       242195.58     2145347.152      241848.358
     2145304.618      241580.128     2144644.028      241310.163
     2144379.271      240771.969     2143510.347      240778.045
     2142456.653      239420.564     2142033.784      239267.628
     2141460.868       237231.17     2140466.076      236613.983
     2138148.335      236325.913     2137016.391       235363.24
     2135929.585      235406.642     2133876.633      236554.212
     2131573.248      237150.566     2131110.756      238554.121

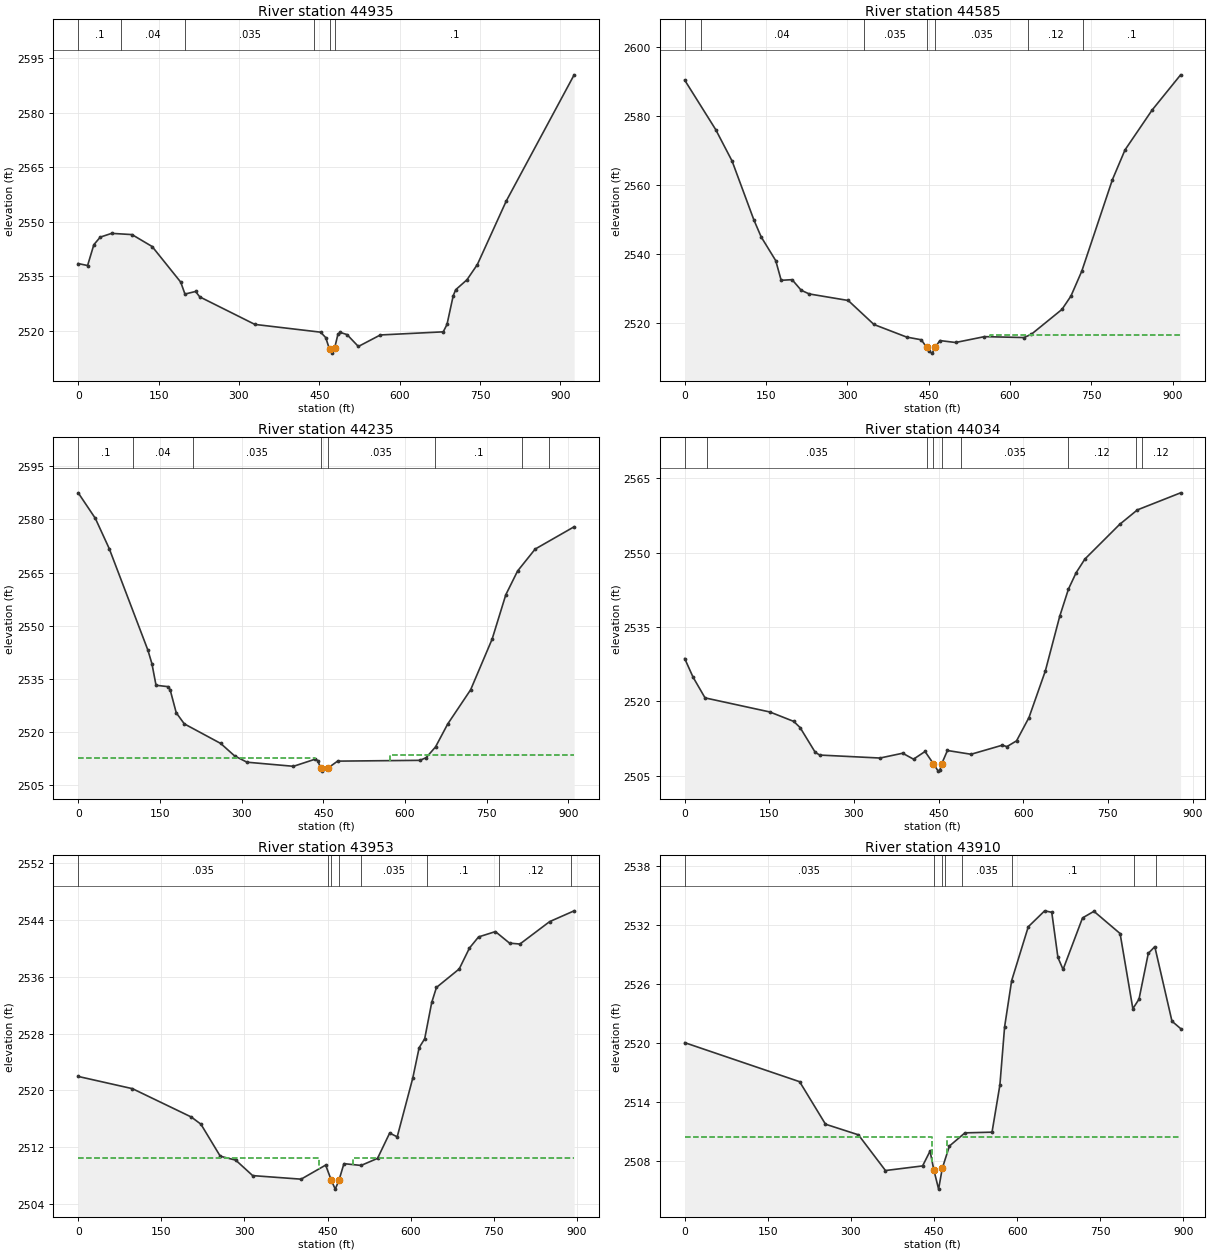
Type RM Length L Ch R = 1 ,44935   ,350,350,350
XS GIS Cut Line= 3
     2158514.913      245724.808     2158121.526      245989.398
     2157772.602      246275.753
#Sta/Elev= 30
       0  2538.5    17.5 2537.96    29.2 2543.69    41.1 2545.76    62.4  2546.8
   100.4 2546.46     138 2543.18   191.3  2533.4   199.2 2530.12     219 2530.83
   226.9 2529.34   329.7 2521.78   452.3 2519.65   461.9 2518.16     469 2514.93
   473.7 2513.89   478.4  2515.2   484.6 2519.03   488.9 2519.58   501.6 2518.99
   522.8 2515.72   563.8 2518.88   681.2 2519.74   688.2 2521.77   699.8 2529.66
   704.5 2531.32   725.5 2534.05   744.9 2538.24   798.7 2555.66   925.5 2590.36
#Mann= 6 ,-1 , 0
       0      .1       0      80     .04       0     200    .035       0
     440      .1       0     469    .045       0   478.4      .1       0
Bank Sta=469,478.4
XS Rating Curve= 0 ,0
Exp/Cntr=0.3,0.1

Type RM Length L Ch R = 1 ,44585   ,353.4,350.2,346.9
XS GIS Cut Line= 3
     2158471.169      245570.352     2158027.259      245665.474
     2157572.546      245739.756
#Sta/Elev= 30
       0 2590.45    57.2 2576.07    87.4 2566.94   127.7 2549.79   141.1 2544.88
   167.9    2538     178 2532.27   198.1 2532.46   214.9 2529.38   229.7 2528.31
   301.6 2526.41   349.1 2519.43   409.5 2515.77   436.4 2514.99   446.4 2512.76
   449.8 2511.59   456.5 2511.11   462.1 2512.82   470.7 2514.76   499.7  2514.2
   552.9  2515.9     626 2515.64   639.4 2516.59   695.8 2523.81   712.4 2527.69
   732.4 2534.93   788.9 2561.52   812.2 2570.18     862 2581.72   914.7 2591.98
#Mann= 7 ,-1 , 0
       0      .1       0      30     .04       0     330    .035       0
   446.4    .045       0   462.1    .035       0  633.99     .12       0
  733.99      .1       0
#XS Ineff= 2 , 0
                          563.16          2516.5
Permanent Ineff=
       F       F
Bank Sta=446.4,462.1
XS Rating Curve= 0 ,0
Exp/Cntr=0.3,0.1

Type RM Length L Ch R = 1 ,44235   ,203.2,200.5,197.8
XS GIS Cut Line= 3
     2158338.079      245118.005     2157936.083      245330.825
     2157519.856      245516.646
#Sta/Elev= 30
       0 2587.52    31.5  2580.3    56.9 2571.81     128 2543.14   135.4 2539.31
   142.9 2533.25   165.1 2532.86   168.8 2531.99     180  2525.5   194.8 2522.37
   261.7 2516.84   287.2 2513.33   309.9 2511.56   395.3  2510.4   435.5 2512.43
   439.8 2512.02     4452509.986   448.5 2509.04   458.22509.859   476.3 2511.86
   627.2 2512.08   638.8 2512.82   656.2 2515.88   678.5 2522.33   720.6 2531.98
   760.1 2546.28   785.2 2558.78   806.8 2565.47   839.1 2571.66   910.7 2577.95
#Mann= 8 ,-1 , 0
       0      .1       0     100     .04       0     210    .035       0
     445    .045       0   458.2    .035       0  654.86      .1       0
  814.86     .12       0  864.86      .1       0
#XS Ineff= 2 , 0
          434.96 2512.72  572.37         2513.48
Permanent Ineff=
       F       F
Bank Sta=445,458.2
XS Rating Curve= 0 ,0
Exp/Cntr=0.3,0.1

Type RM Length L Ch R = 1 ,44034   ,81,81,80.9
XS GIS Cut Line= 2
2158183.91181766 244874.317562962157504.94354352245432.229478144
#Sta/Elev= 30
       0 2528.65    14.8  2524.9    36.1 2520.71   150.9 2517.87   193.2 2515.97
   204.5 2514.73   231.4 2509.72   239.5 2509.18   346.1 2508.58   386.3 2509.55
   405.5 2508.35   425.9  2509.9   440.5 2507.47   449.2 2505.94   452.2  2506.1
   455.32507.383   465.6  2510.1   507.4 2509.34   562.6 2511.16   571.1 2510.89
   588.1 2512.05   610.1 2516.75   639.1 2526.15   664.5 2537.13     680 2542.64
   693.7 2545.96   709.2 2548.71   770.7 2555.69   802.2 2558.62   878.8 2562.06
#Mann= 9 ,-1 , 0
       0     .04       0      40    .035       0     430     .06       0
   440.5    .045       0   455.3     .06       0     490    .035       0
     680     .12       0     800      .1       0     810     .12       0
Bank Sta=440.5,455.3
XS Rating Curve= 0 ,0
Exp/Cntr(USF)=0,0
Exp/Cntr=0.5,0.3

Type RM Length L Ch R = 1 ,43953   ,42.9,42.9,42.8
XS GIS Cut Line= 2
     2158146.054      244799.485      2157455.95      245369.146
#Sta/Elev= 30
       0 2521.97    97.9 2520.25     204 2516.27   221.4 2515.26   256.3 2510.76
   284.3  2510.2   314.8 2508.03   402.2 2507.53   446.5 2509.51   456.72507.366
   463.8 2506.13   470.62507.398   479.5 2509.71   510.4 2509.46   540.1 2510.45
     562 2514.01   575.6 2513.48   603.6 2521.71   615.2 2526.01   625.2 2527.27
   637.9 2532.37   646.4 2534.48   687.5 2537.08     706 2540.02   722.4 2541.58
   752.8 2542.33   778.3 2540.71     797 2540.58   850.6 2543.73   894.9 2545.25
#Mann= 8 ,-1 , 0
       0    .035       0     450     .06       0   456.7    .045       0
   470.6     .06       0     510    .035       0     630      .1       0
     760     .12       0     890      .1       0
#XS Ineff= 2 , 0
             435  2510.5     495          2510.5
Permanent Ineff=
       F       F
Bank Sta=456.7,470.6
XS Rating Curve= 0 ,0
Exp/Cntr=0.5,0.3

Type RM Length L Ch R = 1 ,43910   ,99,98.8,98.8
XS GIS Cut Line= 2
     2158115.672      244769.103     2157425.568      245338.764
#Sta/Elev= 30
       0 2520.08   207.4 2516.11   254.1 2511.79   313.5 2510.71   362.3 2507.08
   429.3 2507.55   442.8 2509.06   449.6 2507.14   458.2 2505.19   464.8  2507.3
   477.7 2509.57   505.7 2510.91   554.6 2510.98   568.8 2515.78   577.3 2521.69
     590 2526.38     620 2531.86   649.6 2533.48   662.4 2533.33   673.5 2528.74
   682.8 2527.52   717.9 2532.76   738.5 2533.43   785.7 2531.17   808.7 2523.53
   819.8  2524.5   836.6 2529.16   848.3 2529.84   879.3 2522.26   894.9 2521.51
#Mann= 8 ,-1 , 0
       0    .035       0   449.6    .045       0   464.8    .035       0
     470     .06       0     500    .035       0     590      .1       0
     810     .12       0     850      .1       0
#XS Ineff= 2 , 0
           446.7  2510.5   473.3          2510.5
Permanent Ineff=
       F       F
Bank Sta=449.6,464.8
XS Rating Curve= 0 ,0
Exp/Cntr=0.5,0.3

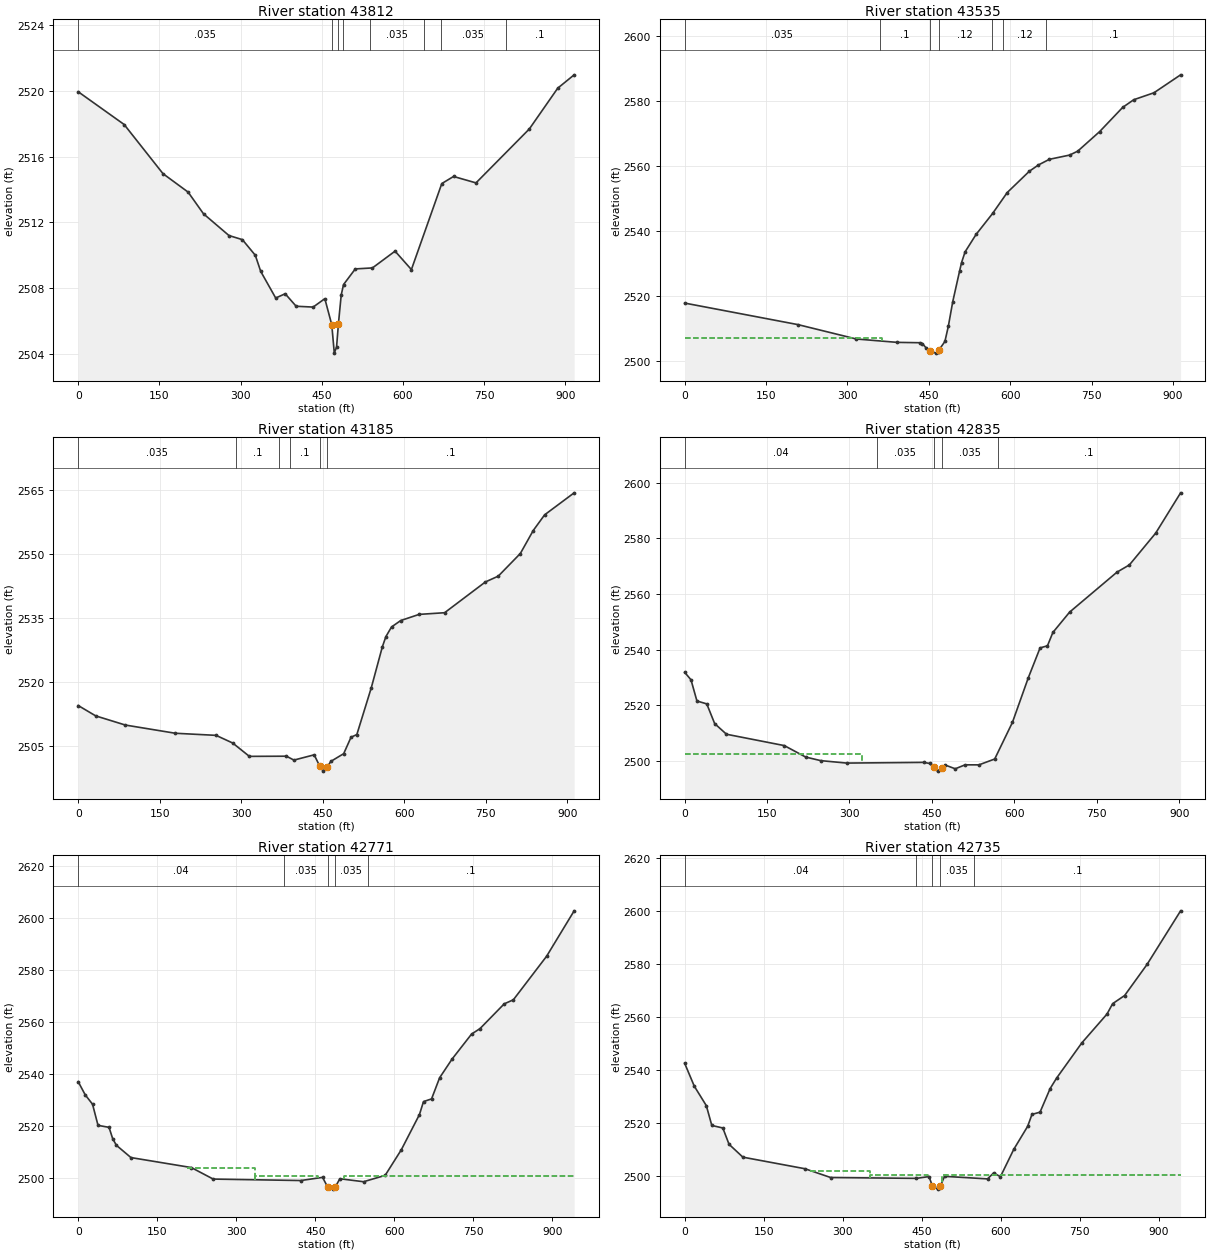
Type RM Length L Ch R = 1 ,43812   ,269.4,276.4,280.5
XS GIS Cut Line= 3
2158111.53697219244742.6702389762157894.43848481244818.206036255
2157373.36054465245265.557679583
#Sta/Elev= 30
       0 2519.94    84.9 2517.95   156.7 2514.96   203.1 2513.84   231.6 2512.52
   278.6  2511.2   303.4 2510.95   327.3    2510   337.3 2509.02     365  2507.4
   382.5 2507.66   402.8  2506.9   434.2 2506.85   455.8 2507.36   468.6 2505.78
   473.3 2504.05   477.5 2504.42  480.98 2505.85   486.1 2507.59   490.4 2508.22
   512.1 2509.17   543.8 2509.23   585.6 2510.25   615.8 2509.13     672 2514.36
   693.7 2514.79   735.2  2514.4   833.8 2517.68   886.3 2520.16   916.6 2520.97
#Mann= 8 ,-1 , 0
       0    .035       0   468.6    .045       0  480.98    .035       0
  489.86     .06       0  539.86    .035       0  639.86      .1       0
  669.86    .035       0  789.86      .1       0
Bank Sta=468.6,480.98
XS Rating Curve= 0 ,0
Exp/Cntr(USF)=0,0
Exp/Cntr=0.3,0.1

Type RM Length L Ch R = 1 ,43535   ,348.5,350.3,349.7
XS GIS Cut Line= 3
     2157984.342      244576.377      2157565.31      244756.775
     2157120.685      244866.793
#Sta/Elev= 30
       0 2517.74     209 2511.09   316.4 2506.66   391.7 2505.62   433.7 2505.51
   438.2 2505.26   445.3 2503.85   452.4 2503.07   462.8  2502.3   466.2 2502.52
  468.09 2503.12   479.7  2505.9     486 2510.57   494.2 2518.22   506.7 2527.58
   510.4 2530.23   516.9 2533.54   537.1  2538.9   567.6 2545.38   594.6 2551.84
   635.3  2558.4   652.1 2560.35   672.3 2562.09   709.5 2563.39   724.5  2564.6
   765.1 2570.66   807.5 2578.12   827.8 2580.47     865 2582.61   914.2 2588.15
#Mann= 7 ,-1 , 0
       0    .035       0     360      .1       0   452.4    .045       0
  468.09     .12       0  566.21      .1       0  586.21     .12       0
  666.21      .1       0
#XS Ineff= 2 , 0
           362.9 2506.91
Permanent Ineff=
       F       F
Bank Sta=452.4,468.09
XS Rating Curve= 0 ,0
Exp/Cntr=0.3,0.1

Type RM Length L Ch R = 1 ,43185   ,351.7,350.2,347.6
XS GIS Cut Line= 3
     2157934.459      244295.883     2157496.488      244417.875
     2157052.929      244530.857
#Sta/Elev= 30
       0 2514.56    32.2 2512.14    86.7    2510   178.7 2508.08   253.6 2507.59
   284.2  2505.8   314.9 2502.68     383 2502.72   396.9 2501.81   434.1 2503.04
   444.3 2500.41   451.1 2499.23   458.62500.297   464.7  2501.5   488.4 2503.31
   501.9 2507.15   512.6 2507.78   539.2 2518.72   559.5 2528.27   566.1 2530.68
   576.4 2532.92   593.3 2534.42   627.2 2535.86   674.1 2536.25   749.1 2543.44
   772.8  2544.8   813.4 2550.09   837.1 2555.46   858.1 2559.13   912.4 2564.27
#Mann= 6 ,-1 , 0
       0    .035       0     290      .1       0     370    .035       0
     390      .1       0   444.3    .045       0   458.6      .1       0
Bank Sta=444.3,458.6
XS Rating Curve= 0 ,0
Exp/Cntr=0.3,0.1

Type RM Length L Ch R = 1 ,42835   ,59.7,63.4,68.9
XS GIS Cut Line= 2
2157877.82618793243892.7361407612157052.80893203244259.050285817
#Sta/Elev= 30
       0 2531.87    11.5 2529.18    22.3 2521.58    40.2 2520.54    54.6 2513.46
    76.1 2509.64   181.3 2505.57   220.3 2501.45   247.6 2500.17   294.9 2499.29
   435.1 2499.54   445.8 2499.16     453 2497.75   460.2  2496.4   468.22497.646
   474.6 2498.55   492.5 2497.24   510.4 2498.66   535.6 2498.65   564.3 2500.75
   596.6 2513.91   625.5 2529.93   646.9 2540.64   660.3 2541.38   670.2 2546.18
   700.7 2553.49   786.9 2567.83   809.5 2570.43   857.3 2581.83   902.7  2596.3
#Mann= 5 ,-1 , 0
       0     .04       0     350    .035       0     453    .045       0
   468.2    .035       0     570      .1       0
#XS Ineff= 2 , 0
          323.14  2502.7
Permanent Ineff=
       F       F
Bank Sta=453,468.2
XS Rating Curve= 0 ,0
Exp/Cntr(USF)=0,0
Exp/Cntr=0.5,0.3

Type RM Length L Ch R = 1 ,42771   ,36.1,36.5,35.8
XS GIS Cut Line= 4
2157883.22364856243874.3880163272157457.84539976244021.432349245
2157398.76508743244024.0581409042157028.52846348244247.250431941
#Sta/Elev= 30
       0 2536.89    13.3 2531.84    27.2 2528.23    37.6 2520.09    58.5 2519.33
    65.4 2514.99    72.4 2512.43   100.1 2507.69   214.7 2503.85   256.3 2499.41
   422.7 2498.85   463.9 2500.07   473.3 2496.43   483.5 2495.54   487.9 2496.33
   496.7 2499.54   541.7 2498.39   582.7 2500.84   613.4  2510.7   647.8 2524.25
   655.5 2529.24   670.8 2530.28   686.1 2538.41   709.7 2545.61   746.8 2555.25
   762.7 2557.33   808.7 2566.87   826.1 2568.44   889.2  2585.2   941.5 2602.69
#Mann= 5 ,-1 , 0
       0     .04       0     390    .035       0   473.3    .045       0
   487.9    .035       0  549.21      .1       0
#XS Ineff= 4 ,-1
       0  207.45  2500.5  207.45  336.44 2503.66  336.44     455  2500.5
     505   941.5  2500.5
Permanent Ineff=
       F       F       F       F
Bank Sta=473.3,487.9
XS Rating Curve= 0 ,0
Exp/Cntr(USF)=0,0
Exp/Cntr=0.5,0.3

Type RM Length L Ch R = 1 ,42735   ,117.5,111.8,108
XS GIS Cut Line= 4
2157876.65916942243838.9398289272157451.28092062243985.984161845
2157392.20060828243988.6099535042157021.96398433244211.802244541
#Sta/Elev= 30
       0 2542.44    18.2 2533.84    41.1 2526.48    51.5 2519.02    72.4 2518.06
    84.2 2511.92   110.5 2507.06   228.3  2502.7   277.2 2499.38     440 2499.07
   463.8 2499.74   470.4 2496.15   480.2 2495.01   485.1 2496.09   493.4 2499.83
     575 2498.87   586.5 2501.13   599.4 2499.69   624.8 2510.03   651.1 2518.68
   659.3 2523.19   674.6 2524.02   693.8 2532.92   706.1 2536.88   753.9 2550.13
   801.7    2561   812.5 2564.94   835.2    2568   877.7  2579.7   941.5 2599.93
#Mann= 5 ,-1 , 0
       0     .04       0     440    .035       0   470.4    .045       0
   485.1    .035       0  549.21      .1       0
#XS Ineff= 4 ,-1
       0  237.43  2500.5  237.43  351.63 2501.95  351.63   461.7  2500.5
   488.3   941.5  2500.5
Permanent Ineff=
       F       F       F       F
Bank Sta=470.4,485.1
XS Rating Curve= 0 ,0
Exp/Cntr(USF)=0,0
Exp/Cntr=0.5,0.3

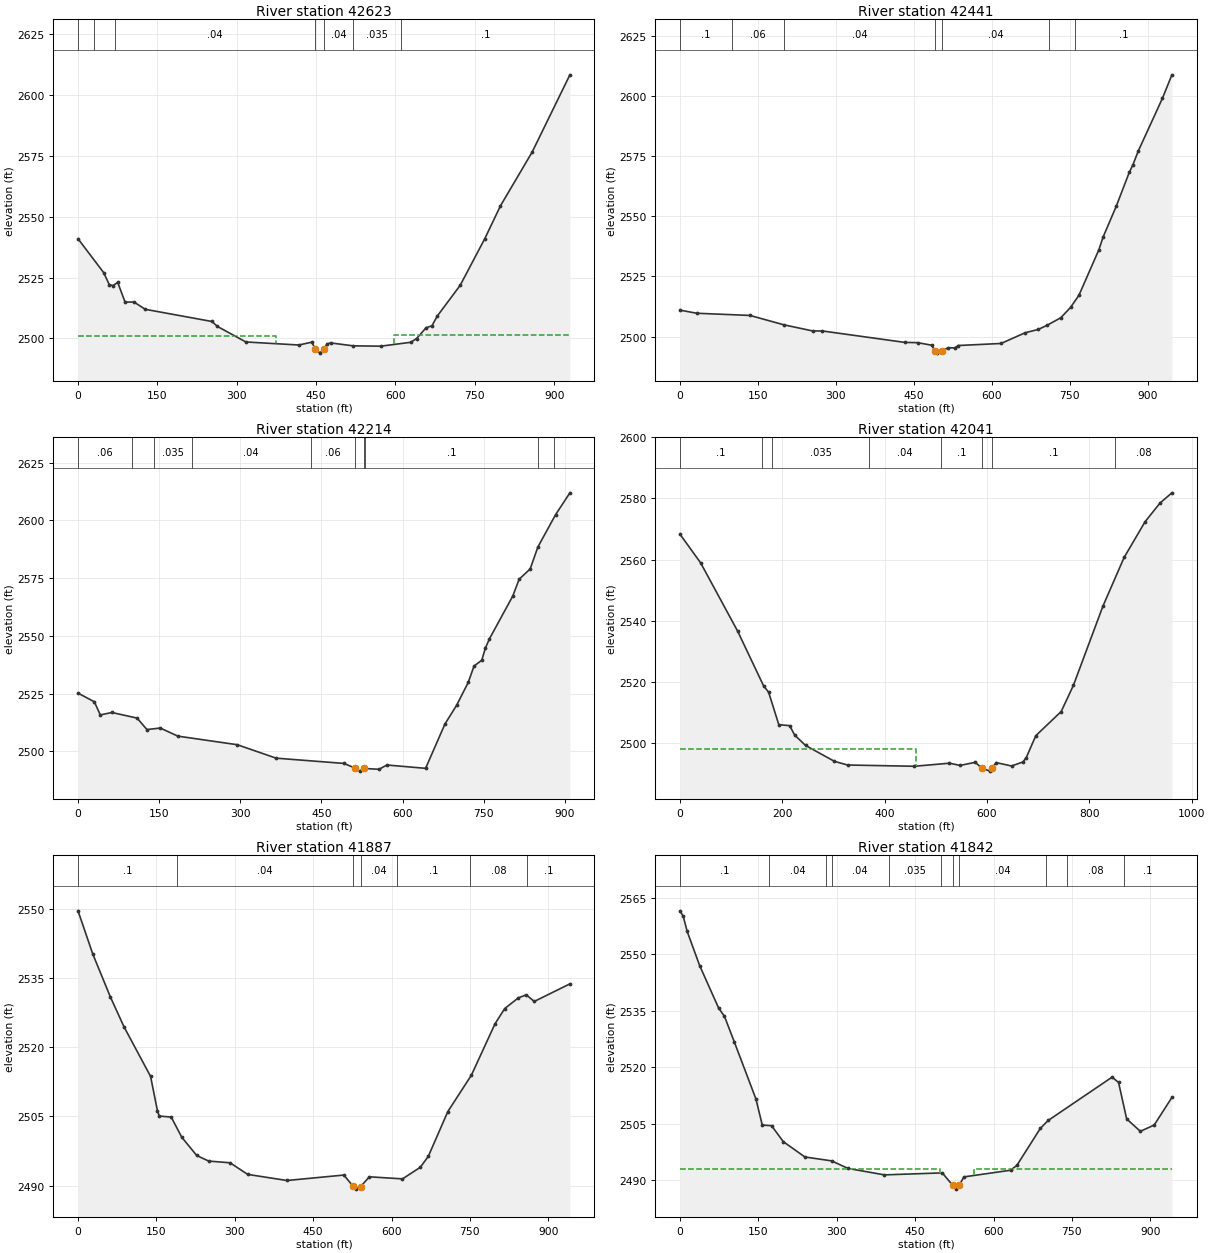
Type RM Length L Ch R = 1 ,42623   ,190.7,182.2,176.8
XS GIS Cut Line= 2
2157819.79813267243693.3140020942156968.82813267244067.391002094
#Sta/Elev= 30
       0    2541    48.4  2527.1    59.2  2522.1    66.3 2521.75      75 2523.07
    88.9 2514.97   105.8 2514.97   127.3 2511.98   253.2 2506.98   263.5 2504.94
   317.2 2498.56   417.4 2497.31   441.9 2498.48     4482495.828   457.4 2493.97
   464.1 2495.69   471.3 2497.78   477.3 2498.17     520 2496.97   572.3 2496.83
     629 2498.43   639.8 2499.98   657.7 2504.39     669 2505.24   678.9 2509.19
   722.2 2521.84   768.8 2541.06   798.4 2554.55   858.2 2576.62   929.6 2608.41
#Mann= 7 ,-1 , 0
       0     .04       0      30      .1       0      70     .04       0
     448    .045       0   464.1     .04       0     520    .035       0
     610      .1       0
#XS Ineff= 2 , 0
          373.67 2500.84  597.07         2501.41
Permanent Ineff=
       F       F
Bank Sta=448,464.1
XS Rating Curve= 0 ,0
Exp/Cntr=0.3,0.1

Type RM Length L Ch R = 1 ,42441   ,216.6,226.2,231.5
XS GIS Cut Line= 4
2157744.86962672243521.3564492392157335.07738971243683.438453426
2157220.39672637243859.2821372142156948.22128538243975.491876065
#Sta/Elev= 30
       0 2510.98    32.3 2509.69   134.6 2508.78     200 2504.87   255.3 2502.32
   273.8 2502.32   432.8 2497.55   457.2 2497.45   484.6 2496.37   490.4 2493.97
   495.2 2493.09   504.6 2494.12   515.9 2495.34   528.4 2495.24   535.5 2496.26
   617.8 2497.11   664.2 2501.57   689.2 2502.94   705.9 2504.62   732.8 2507.83
   751.5 2512.11   767.7 2517.18   806.2  2536.2   814.2 2541.43   839.6 2554.29
   864.6 2568.37   871.7 2571.57   881.8 2577.19   928.2  2599.1   946.6 2608.94
#Mann= 7 ,-1 , 0
       0      .1       0     100     .06       0     200     .04       0
   490.4    .045       0   504.6     .04       0  710.62    .035       0
  760.62      .1       0
Bank Sta=490.4,504.6
XS Rating Curve= 0 ,0
Exp/Cntr(USF)=0,0
Exp/Cntr=0.3,0.1

Type RM Length L Ch R = 1 ,42214   ,171,173.5,171.3
XS GIS Cut Line= 2
     2157652.482      243354.138     2156819.012      243717.277
#Sta/Elev= 30
       0 2525.22    30.2 2521.47    41.2 2515.79    62.7 2516.84   109.2 2514.41
   127.4 2509.45   152.1 2510.11   184.4 2506.61   294.4 2502.89   366.2 2497.07
   491.3  2494.8   511.2 2492.86   520.8 2491.46   528.7  2492.6   556.5 2492.26
   570.9 2494.11   642.4 2492.67   678.3 2511.92   699.7 2519.94   721.2 2529.85
   731.9 2536.92   746.2 2539.45     753 2544.77   760.5 2548.77   803.5 2567.23
   815.3 2574.52   835.7 2578.98     850 2588.51   882.6 2602.44   909.1 2611.91
#Mann= 10 ,-1 , 0
       0     .06       0     100     .04       0     140    .035       0
     210     .04       0     430     .06       0   511.2    .045       0
   528.7     .06       0     530      .1       0     850     .08       0
     880      .1       0
Bank Sta=511.2,528.7
XS Rating Curve= 0 ,0
Exp/Cntr=0.3,0.1

Type RM Length L Ch R = 1 ,42041   ,151.2,153.9,153
XS GIS Cut Line= 2
2157617.33117836243137.1910903572156771.34061202243593.979385127
#Sta/Elev= 30
       0 2568.31    40.3 2558.95   112.6 2536.64   163.3 2518.76   173.1  2516.7
   193.1 2506.05   214.3 2505.74     224 2502.67   245.3 2499.28   301.8 2494.07
   327.4 2492.87   457.9 2492.46   526.6 2493.46   547.3 2492.74   577.2 2493.75
   589.6 2491.86   605.7 2490.87  609.39 2491.94   618.2 2493.65     648 2492.55
   670.4 2493.88   676.8 2495.32   695.4 2502.46     745 2510.36   768.8 2518.88
   826.6 2544.82     868 2560.73     909 2572.41   938.2 2578.52   961.4 2581.85
#Mann= 8 ,-1 , 0
       0      .1       0     160     .04       0     180    .035       0
     370     .04       0     510      .1       0   589.6    .045       0
  609.39      .1       0     850     .08       0
#XS Ineff= 2 , 0
          461.81 2498.03
Permanent Ineff=
       F       F
Bank Sta=589.6,609.39
XS Rating Curve= 0 ,0
Exp/Cntr(USF)=0,0
Exp/Cntr=0.3,0.1

Type RM Length L Ch R = 1 ,41887   ,45.1,45.4,44.7
XS GIS Cut Line= 2
2157524.49896789243014.6268956462156702.01596789243472.525895646
#Sta/Elev= 30
       0 2549.53    28.2 2540.19      62 2530.85    88.1 2524.38   138.9 2513.64
   152.1 2506.14   155.6 2505.06   178.4 2504.83   198.5 2500.48   227.2 2496.51
     250  2495.3     291 2494.93   324.8 2492.41   399.9 2491.09   508.8 2492.27
  526.57 2489.83     532 2489.22   540.82489.767   557.6 2491.89     621 2491.44
   655.1 2493.95   670.3  2496.3   707.8 2506.03   752.9 2513.92     798 2525.03
   816.7 2528.36     843 2530.69     858 2531.32   873.1 2529.89   941.4  2533.7
#Mann= 7 ,-1 , 0
       0      .1       0     190     .04       0  526.57    .045       0
   540.8     .04       0     610      .1       0     750     .08       0
     860      .1       0
Bank Sta=526.57,540.8
XS Rating Curve= 0 ,0
Exp/Cntr=0.5,0.3

Type RM Length L Ch R = 1 ,41842   ,49.2,46.7,46.9
XS GIS Cut Line= 2
     2157511.867      242973.573     2156689.384      243431.472
#Sta/Elev= 30
       0 2561.47     6.2    2560    13.7    2556    37.6 2546.94    73.8  2535.7
    85.1 2533.47   103.8 2526.73   145.3 2511.55   157.4 2504.63   175.2 2504.47
   197.7 2500.23     239 2496.17     290 2495.14   321.6 2493.13   391.3 2491.42
   501.9 2491.95   521.52488.716   528.8 2487.64   534.62488.704   543.2 2490.88
   632.5 2492.65   644.6 2493.93   689.6 2503.75   704.6 2505.86   826.8 2517.34
   839.3 2515.95   854.8 2506.26     881 2502.98   907.5 2504.64   941.4 2511.97
#Mann= 11 ,-1 , 0
       0      .1       0     170     .04       0     280    .035       0
     290     .04       0     400    .035       0     500     .04       0
   521.5    .045       0   534.6     .04       0     700      .1       0
     740     .08       0     850      .1       0
#XS Ineff= 2 , 0
           497.5    2493   562.5            2493
Permanent Ineff=
       F       F
Bank Sta=521.5,534.6
XS Rating Curve= 0 ,0
Exp/Cntr(USF)=0,0
Exp/Cntr=0.5,0.3

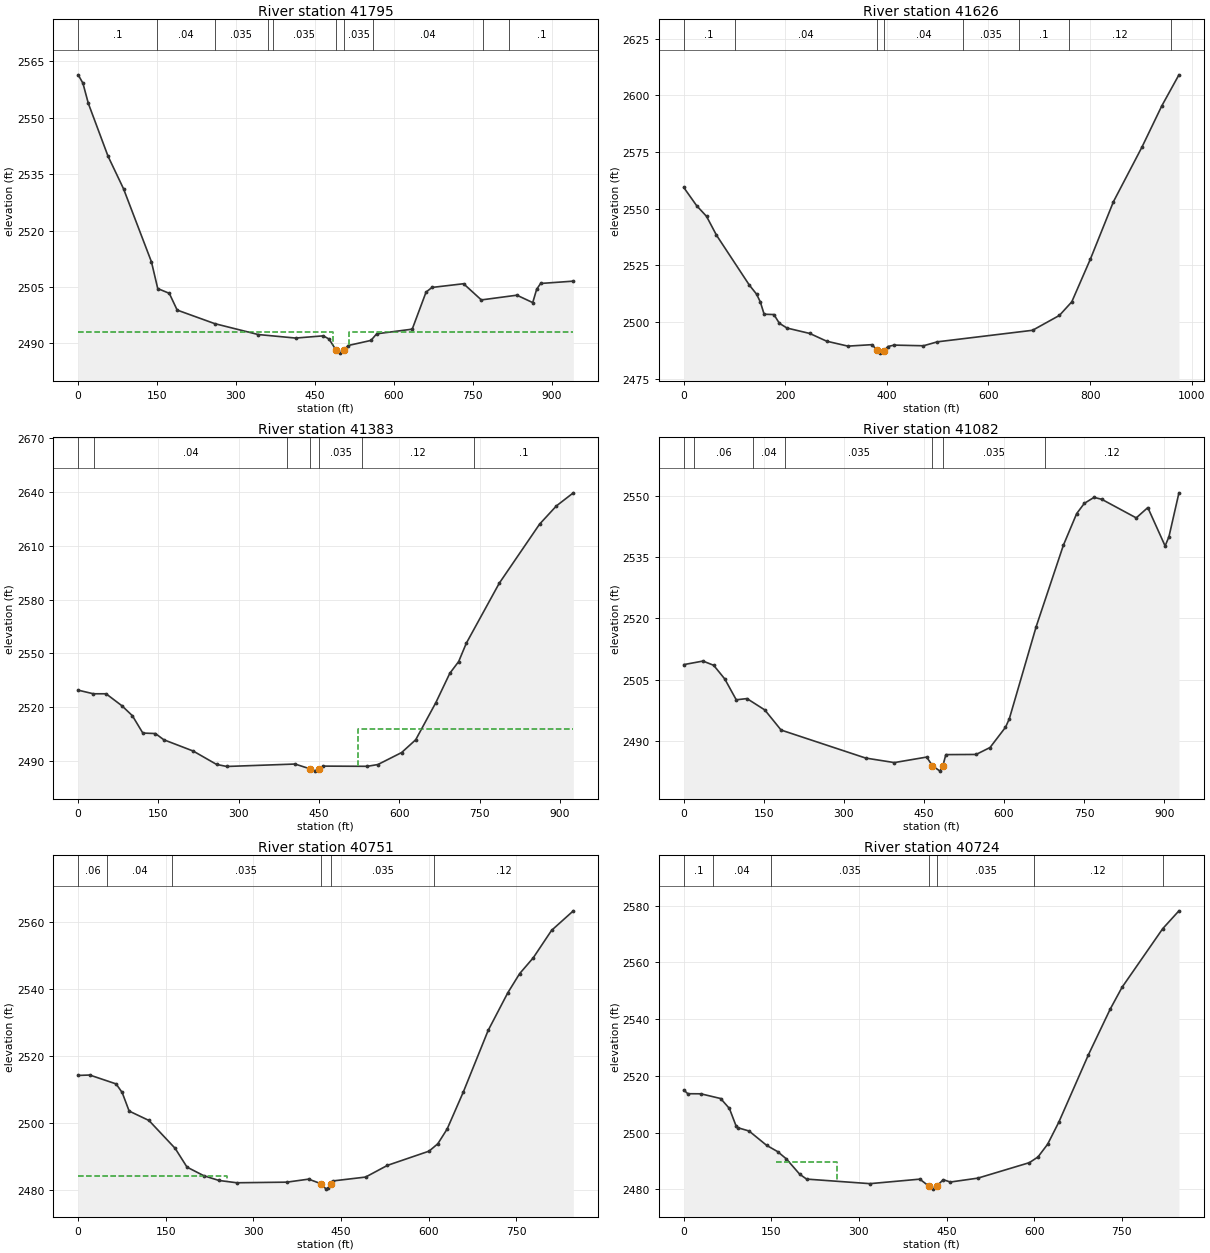
Type RM Length L Ch R = 1 ,41795   ,167.5,168.8,169.8
XS GIS Cut Line= 2
2157490.47123732  242940.69909332156667.98823732  243398.5990933
#Sta/Elev= 30
       0 2561.45       9 2559.23    19.3 2553.85    56.8 2539.78    86.2 2531.13
   139.3 2511.68   151.3 2504.56   173.2  2503.3   188.2 2498.84   259.6 2495.23
   342.2 2492.33   413.5 2491.39   466.1 2491.98     477 2491.12   489.7 2488.32
   498.7 2487.38   505.9 2488.23   513.1  2489.4   556.6 2490.76   567.5 2492.52
   635.1 2493.76   661.4 2503.62   672.6 2504.86   732.7 2505.85   766.5 2501.54
   834.1  2502.8   864.2 2500.83   871.7 2504.38   879.2 2505.92   941.4 2506.54
#Mann= 10 ,-1 , 0
       0      .1       0     150     .04       0     260    .035       0
     360     .04       0     370    .035       0   489.7    .045       0
   505.9    .035       0     560     .04       0     770     .08       0
     820      .1       0
#XS Ineff= 2 , 0
           484.2    2493   515.8            2493
Permanent Ineff=
       F       F
Bank Sta=489.7,505.9
XS Rating Curve= 0 ,0
Exp/Cntr(USF)=0,0
Exp/Cntr=0.5,0.3

Type RM Length L Ch R = 1 ,41626   ,243.3,243.2,242.9
XS GIS Cut Line= 3
2157444.68035372  242836.48535822156832.80302698243175.222117276
2156557.45851827243187.013631127
#Sta/Elev= 30
       0 2559.29    25.4 2551.25    44.8 2546.56    64.4 2538.25   129.2 2516.19
   143.2 2512.27   150.7 2508.82   158.2 2503.37   177.5 2503.23   188.2 2499.38
   203.2 2497.28   248.2 2494.88   281.3 2491.48   323.2  2489.3   370.6 2489.95
  380.73 2487.47   386.9 2486.21   394.7 2487.36   401.9 2489.11   414.1 2489.75
     472 2489.46   499.4  2491.2   686.8 2496.29   739.7 2502.86     764 2508.84
   800.8 2527.79   846.1 2553.07   901.9 2576.99   941.4 2595.37     975    2609
#Mann= 8 ,-1 , 0
       0      .1       0     100     .04       0  380.73    .045       0
   394.7     .04       0     550    .035       0     660      .1       0
  759.38     .12       0  959.38      .1       0
Bank Sta=380.73,394.7
XS Rating Curve= 0 ,0
Exp/Cntr=0.3,0.1

Type RM Length L Ch R = 1 ,41383   ,295.9,300.9,301.5
XS GIS Cut Line= 2
2157292.53056028242630.3760602932156518.62758918 243137.21427814
#Sta/Elev= 30
       0  2529.6    28.4 2527.59    52.1 2527.59    81.6 2520.96   101.2 2515.42
   120.8 2505.75   144.3 2505.48     160 2502.02   214.9 2495.75   258.6  2488.3
   277.7 2487.17   405.2 2488.52     4342485.773   443.1 2484.58   450.2 2485.81
   450.2 2485.82   450.2 2485.83   457.3 2487.37   540.3 2487.26     560 2488.25
   604.3 2494.91   630.6 2502.02   668.3 2522.71   694.3 2538.97   710.9 2545.52
   725.1 2555.68   786.7 2589.07     862  2621.9   893.4 2632.04   925.1 2639.33
#Mann= 7 ,-1 , 0
       0      .1       0      30     .04       0     390    .035       0
     434    .045       0   450.2    .035       0     530     .12       0
     740      .1       0
#XS Ineff= 2 , 0
                          522.03         2507.89
Permanent Ineff=
       F       F
Bank Sta=434,450.2
XS Rating Curve= 0 ,0
Exp/Cntr(USF)=0,0
Exp/Cntr=0.3,0.1

Type RM Length L Ch R = 1 ,41082   ,330.3,331,328.6
XS GIS Cut Line= 3
     2157186.665      242451.001     2156748.578      242638.508
     2156337.818      242825.212
#Sta/Elev= 30
       0 2508.71      36 2509.58      56 2508.54    76.8  2505.2    98.3  2500.1
   118.4  2500.4   151.8 2497.62   182.3  2492.7   340.7 2485.85   394.5 2484.74
   455.1 2486.09   465.9 2483.95   480.1 2482.65  485.36 2483.95     491 2486.69
   547.7 2486.73   573.8 2488.43   602.7 2493.37   609.9 2495.45   660.3 2518.03
   711.2 2537.92   736.1 2545.66   750.4 2548.16   768.5 2549.62   782.9 2549.17
   847.7 2544.61   869.4 2547.13   901.8 2537.74     909 2540.01   927.7 2550.74
#Mann= 7 ,-1 , 0
       0      .1       0      20     .06       0     130     .04       0
     190    .035       0   465.9    .045       0  485.36    .035       0
  676.53     .12       0
Bank Sta=465.9,485.36
XS Rating Curve= 0 ,0
Exp/Cntr=0.3,0.1

Type RM Length L Ch R = 1 ,40751   ,26.7,26.7,26.6
XS GIS Cut Line= 2
 2157012.0237711242132.670638591 2156269.8357711242542.827638591
#Sta/Elev= 30
       0  2514.1    19.8 2514.22    64.9 2511.57    75.3 2509.02    87.3 2503.46
   121.2 2500.65   166.1 2492.32   186.4 2486.72   215.3 2484.14     241 2482.74
   271.6 2482.05   357.2 2482.23   394.7 2483.13   415.7 2481.77   424.7 2480.15
   428.5  2480.5   432.3  2481.8     436 2482.59   492.2 2483.75   529.7 2487.25
   600.9 2491.49   615.9 2493.69   631.9  2498.1   659.6 2509.16   702.1 2527.53
   735.8 2538.79   756.1 2544.51   779.3 2549.21   810.8 2557.43     848 2563.25
#Mann= 6 ,-1 , 0
       0     .06       0      50     .04       0     160    .035       0
   415.7    .045       0   432.3    .035       0     610     .12       0
#XS Ineff= 2 , 0
          254.72 2483.97
Permanent Ineff=
       F       F
Bank Sta=415.7,432.3
XS Rating Curve= 0 ,0
Exp/Cntr=0.5,0.3

Type RM Length L Ch R = 1 ,40724   ,52.9,52.8,52.7
XS GIS Cut Line= 2
     2157000.655      242108.512     2156258.467      242518.669
#Sta/Elev= 30
       0 2514.99     6.9 2513.68    29.2 2513.65    63.1 2511.99    78.1 2508.49
    89.5 2502.36      92 2501.73   111.8 2500.53   141.8 2495.49   160.6 2493.28
   175.6 2490.72   198.4 2485.32   210.3 2483.58   318.9 2481.97   404.2 2483.56
   419.12481.201   426.7 2480.04   433.52481.208   444.4 2483.37   456.5 2482.54
   503.7 2483.92   591.8 2489.37   606.6 2491.38   623.1 2495.87   642.4 2503.71
   693.1 2527.47   730.3 2543.52   750.6 2551.22   820.3  2571.9     848 2578.17
#Mann= 7 ,-1 , 0
       0      .1       0      50     .04       0     150    .035       0
   419.1    .045       0   433.5    .035       0     600     .12       0
     820      .1       0
#XS Ineff= 4 ,-1
       0  158.24    2482  158.24  262.54  2489.6  262.54   397.5    2482
   452.5     848    2482
Permanent Ineff=
       F       F       F       F
Bank Sta=419.1,433.5
XS Rating Curve= 0 ,0
Exp/Cntr(USF)=0,0
Exp/Cntr=0.5,0.3