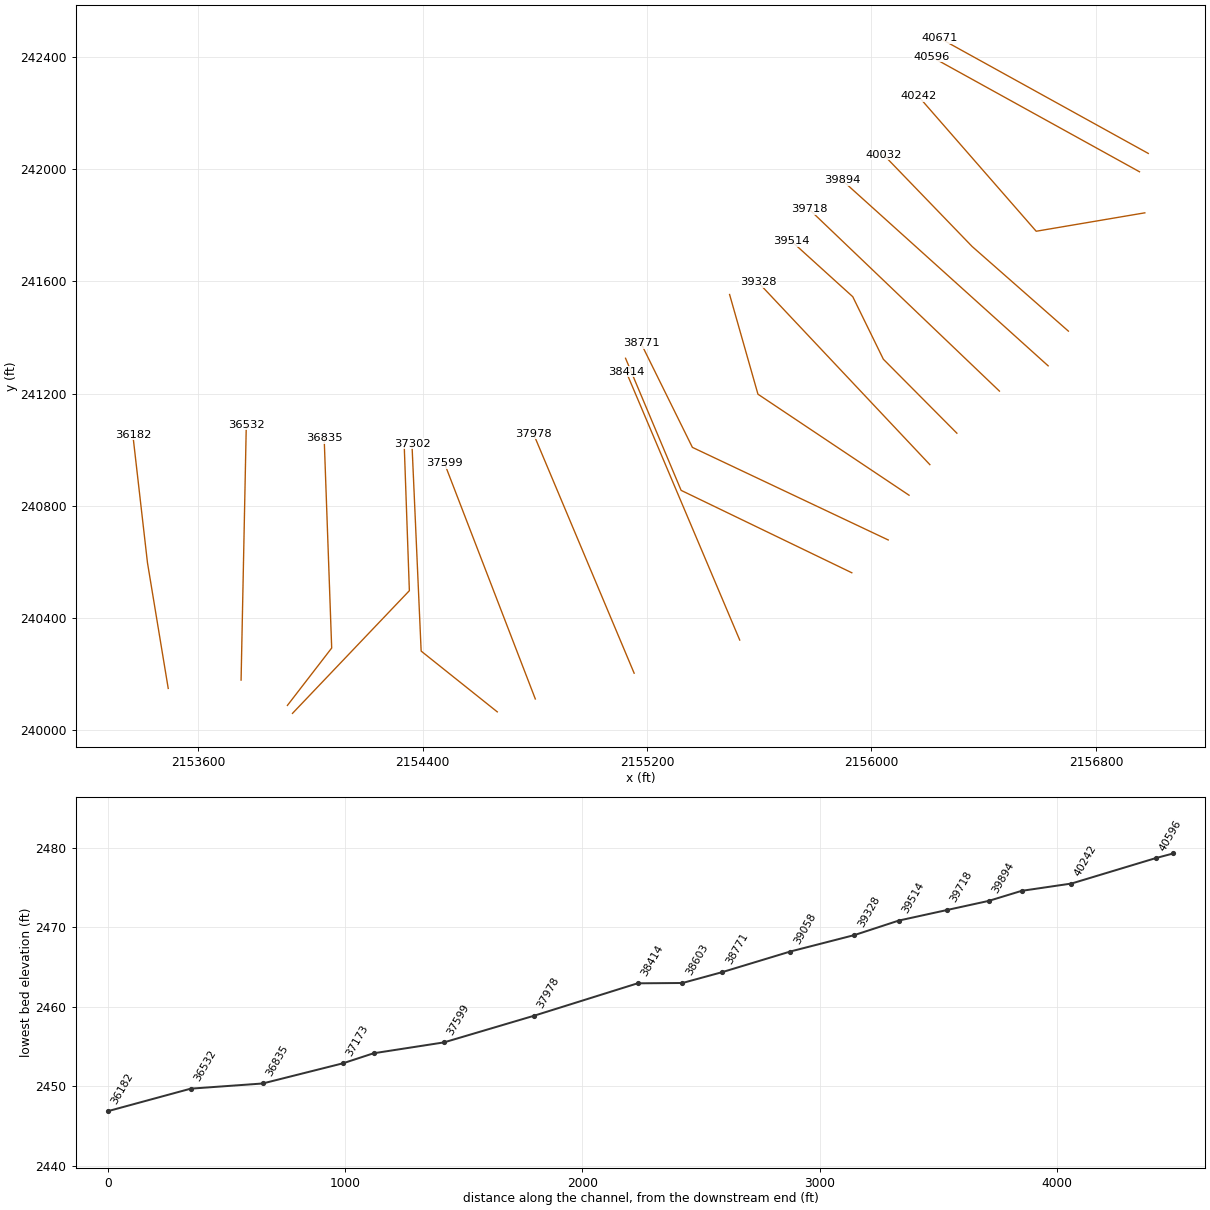
HEC-RAS study LAURELCK3.prj: LAURELCK3

--- LAURELCK3.g01 (geometry) --- (continued)

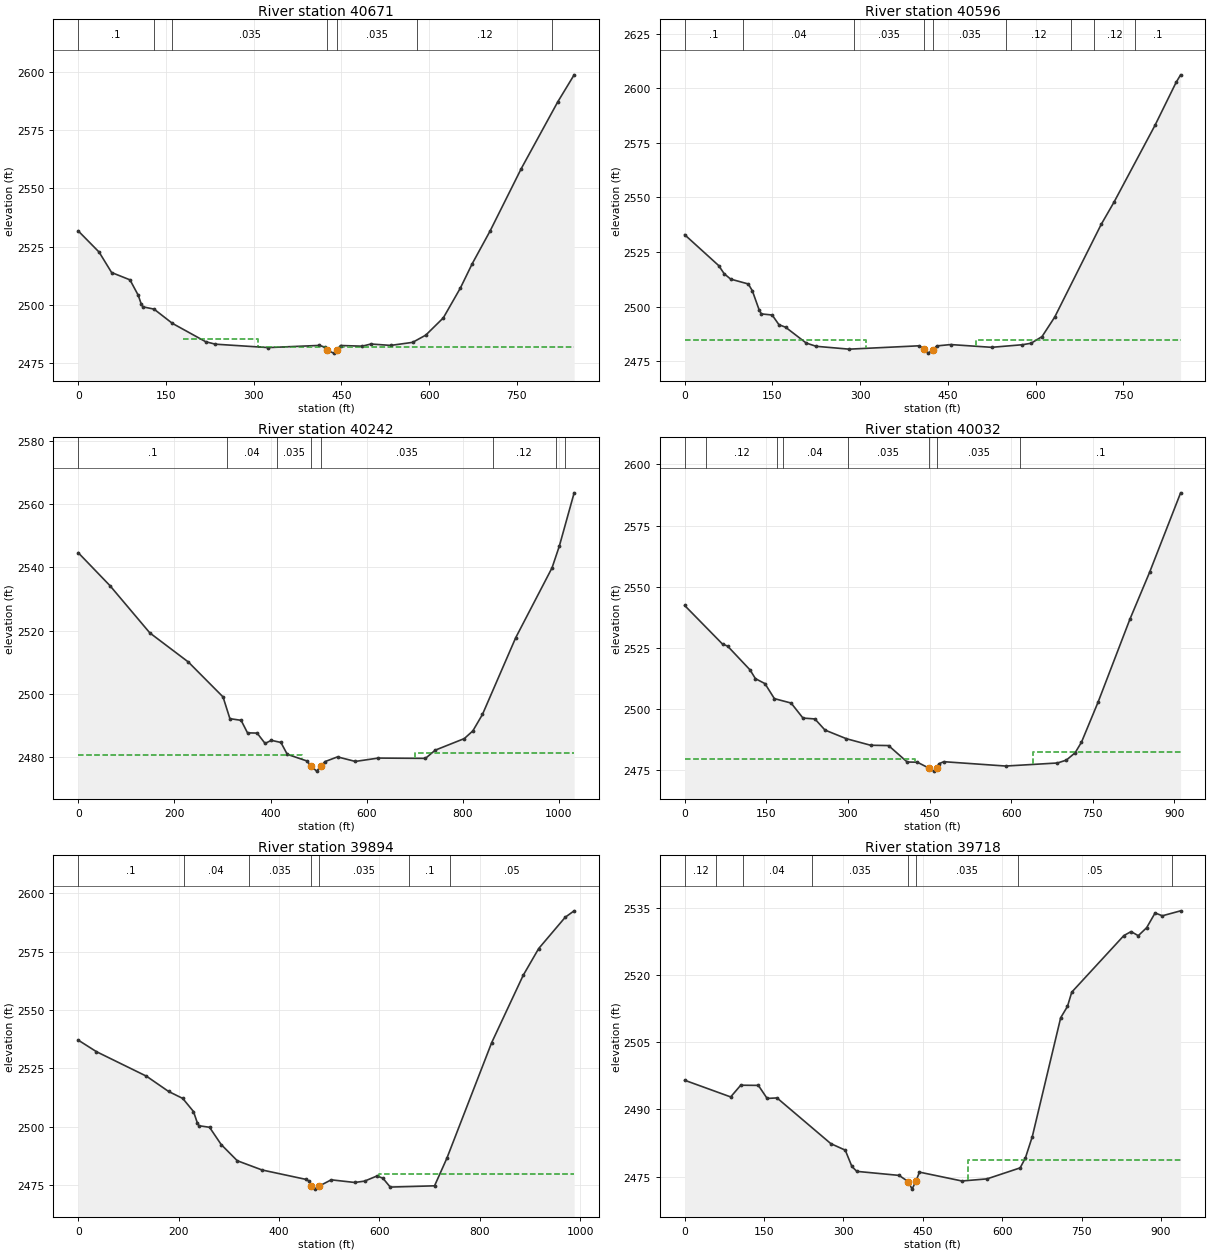
Type RM Length L Ch R = 1 ,40671   ,75.4,75.5,75.6
XS GIS Cut Line= 2
     2156986.549      242056.429     2156244.361      242466.585
#Sta/Elev= 30
       0 2531.74    35.7 2522.65    57.1 2513.88    88.5 2510.74   102.6 2504.15
   107.8 2500.35   110.7 2499.16   129.6 2498.19   160.9  2492.1   217.9 2484.21
   234.4 2483.15   325.1 2481.69     412 2482.61   421.7 2481.91   425.62480.578
   436.8 2479.31   441.8  2480.6   448.5 2482.58   485.6 2482.29   500.6 2483.22
   534.3 2482.62   571.8 2483.93   594.3 2487.04   624.3 2494.44   653.5 2507.25
   673.7 2517.66   704.2 2531.67   757.5 2558.43     820  2587.1     848 2598.68
#Mann= 7 ,-1 , 0
       0      .1       0     130     .04       0     160    .035       0
   425.6    .045       0   441.8    .035       0     580     .12       0
     810      .1       0
#XS Ineff= 4 ,-1
       0  179.34    2482  179.34  306.81 2485.42  306.81   424.2    2482
   445.8     848    2482
Permanent Ineff=
       F       F       F       F
Bank Sta=425.6,441.8
XS Rating Curve= 0 ,0
Exp/Cntr(USF)=0,0
Exp/Cntr=0.5,0.3

Type RM Length L Ch R = 1 ,40596   ,358.6,354.1,347.2
XS GIS Cut Line= 2
2156955.28487947241991.0585661642156213.09687947242401.214566164
#Sta/Elev= 30
       0 2532.93    58.1 2518.81    67.7 2515.01    78.7  2512.6   108.8 2510.37
   115.7 2507.26   127.5 2498.38   131.2 2496.67   149.6 2496.16   161.2 2491.72
   172.5 2490.58   207.8 2483.33   224.7 2481.84   281.2 2480.53   401.1 2482.07
   409.22480.525   416.1 2478.71   424.72480.245   431.1 2482.01   454.8 2482.63
   524.8 2481.37   577.3 2482.55   592.3 2483.23     611 2486.28   632.7 2495.21
   712.2 2537.66   734.1 2547.84   804.1 2582.97   840.3 2602.69     848 2606.14
#Mann= 9 ,-1 , 0
       0      .1       0     100     .04       0     290    .035       0
   409.2    .045       0   424.7    .035       0     550     .12       0
     660      .1       0     700     .12       0     770      .1       0
#XS Ineff= 2 , 0
          310.03 2484.88  497.29         2484.79
Permanent Ineff=
       F       F
Bank Sta=409.2,424.7
XS Rating Curve= 0 ,0
Exp/Cntr=0.3,0.1

Type RM Length L Ch R = 1 ,40242   ,208.2,210,210
XS GIS Cut Line= 3
     2156974.331      241844.705     2156587.128      241779.078
     2156167.112      242260.346
#Sta/Elev= 30
       0 2544.66    65.9 2534.25   149.1 2519.25     229 2510.07   301.2 2499.01
   315.5 2492.13   338.8  2491.6   352.1 2487.64   372.1 2487.56   388.7 2484.28
   401.7 2485.27   421.6 2484.59   434.8 2480.84   475.2 2478.76   484.5 2477.11
   495.8 2475.52   505.4  2477.2   513.2 2478.53   539.3 2480.03   576.3 2478.59
     624 2479.65   722.2 2479.56   742.6 2482.16     803 2485.82   820.8 2488.26
   840.8 2493.47     910 2517.77   985.5 2539.87  1000.7 2546.76  1031.5 2563.61
#Mann= 8 ,-1 , 0
       0      .1       0     310     .04       0  412.73    .035       0
   484.5    .045       0   505.4    .035       0  862.73     .12       0
  992.73      .1       0 1012.73     .12       0
#XS Ineff= 2 , 0
          464.99 2480.73  700.03         2481.24
Permanent Ineff=
       F       F
Bank Sta=484.5,505.4
XS Rating Curve= 0 ,0
Exp/Cntr=0.3,0.1

Type RM Length L Ch R = 1 ,40032   ,137.8,138.2,138.6
XS GIS Cut Line= 3
     2156701.894      241423.089     2156358.856       241724.69
     2156043.033      242051.794
#Sta/Elev= 30
       0 2542.33    69.6 2526.54    78.9 2525.72   120.1    2516     130 2512.42
   147.5 2510.39   164.9 2504.24   195.6 2502.44   217.4  2496.3   239.3 2495.94
   257.9 2491.39   297.4 2487.84   341.6 2485.19   374.7 2485.05     409 2478.33
   427.6 2478.25   448.5 2475.88   457.9  2474.6   463.32475.977   467.2 2477.59
   476.1 2478.46   590.1 2476.68   685.2 2477.93   701.5 2479.11   717.6  2482.1
   729.3 2486.44   760.1 2502.98   818.1 2536.61   854.6 2555.97   911.5  2588.4
#Mann= 8 ,-1 , 0
       0      .1       0      40     .12       0     170    .035       0
     180     .04       0     300    .035       0   448.5    .045       0
   463.3    .035       0  616.77      .1       0
#XS Ineff= 2 , 0
          423.68 2479.45  639.47         2482.25
Permanent Ineff=
       F       F
Bank Sta=448.5,463.3
XS Rating Curve= 0 ,0
Exp/Cntr=0.3,0.1

Type RM Length L Ch R = 1 ,39894   ,176,176,175.2
XS GIS Cut Line= 2
 2156629.7519201241299.3807490692155895.51878644241960.980067359
#Sta/Elev= 30
       0 2537.12    36.4 2532.16     136 2521.68   180.1 2515.14   208.3 2512.16
   229.7 2506.56   237.5 2501.62   240.8 2500.46   261.7 2499.81   284.9 2492.43
     317 2485.49   366.3 2481.54   454.5 2477.48   459.2 2476.87   464.82474.653
   471.6 2473.34   479.7  2474.6   504.2 2477.32   551.1 2476.19   570.7 2476.77
   595.2 2478.96   607.1 2478.03   621.8 2474.22   710.1 2474.75   734.6 2486.53
   823.9 2536.01   886.7 2564.83   917.6  2576.3   970.6 2589.72   988.3 2592.45
#Mann= 7 ,-1 , 0
       0      .1       0     210     .04       0     340    .035       0
   464.8    .045       0   479.7    .035       0     660      .1       0
     740     .05       0
#XS Ineff= 2 , 0
                          598.68            2480
Permanent Ineff=
       F       F
Bank Sta=464.8,479.7
XS Rating Curve= 0 ,0
Exp/Cntr(USF)=0,0
Exp/Cntr=0.3,0.1

Type RM Length L Ch R = 1 ,39718   ,207.1,203.5,198.5
XS GIS Cut Line= 2
 2156456.0623616241209.3779778452155778.67308345241856.766332258
#Sta/Elev= 30
       0 2496.53    86.9  2492.8   105.9 2495.42   139.2 2495.38   155.8 2492.46
   174.4 2492.58   276.1 2482.36   303.4  2480.9   315.9 2477.26   325.2 2476.16
   405.1 2475.26   422.7 2473.84   429.6 2472.19   436.6  2473.9   443.6 2475.99
   523.8 2474.01   571.2 2474.48   633.8 2476.94   643.7 2479.15   656.8 2483.94
   710.4  2510.5   723.2 2513.03   731.3 2516.22   829.8 2528.87   843.4 2529.76
     857 2528.84   872.9 2530.64   888.8 2533.93   902.4 2533.29     937  2534.4
#Mann= 8 ,-1 , 0
       0     .12       0      60      .1       0     110     .04       0
     240    .035       0   422.7    .045       0   436.6    .035       0
     630     .05       0     920      .1       0
#XS Ineff= 2 , 0
                          535.53         2478.59
Permanent Ineff=
       F       F
Bank Sta=422.7,436.6
XS Rating Curve= 0 ,0
Exp/Cntr(USF)=0,0
Exp/Cntr=0.3,0.1

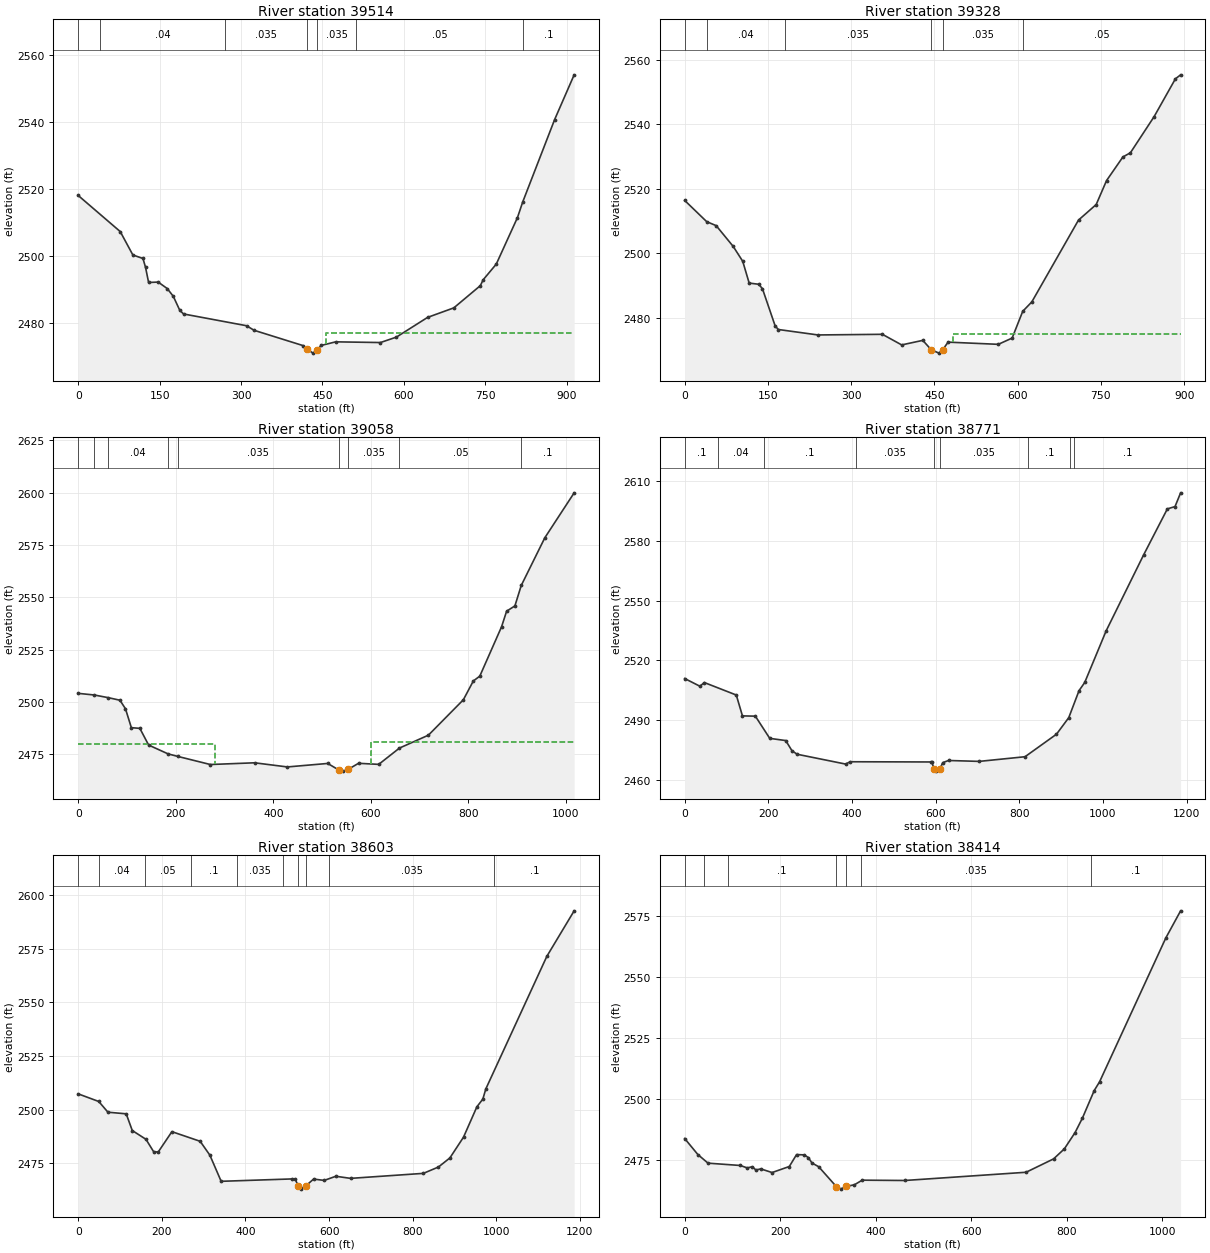
Type RM Length L Ch R = 1 ,39514   ,174.7,186.3,186.5
XS GIS Cut Line= 4
2156304.47874691 241059.373359142156042.36541317241323.065688864
2155933.41469011241545.7041229432155715.51324399241743.078621239
#Sta/Elev= 30
       0 2517.92    77.4 2507.15   100.7 2500.16   119.3 2499.11     124 2496.49
   129.7 2491.95   147.3 2492.07     164 2490.14   175.2 2487.81   187.2 2483.62
   194.1 2482.55   310.1 2479.04     324 2477.68   414.4  2473.1   422.2    2472
   432.6 2470.86   440.42471.748   447.3 2473.14   474.4 2474.23   556.8 2474.02
   586.2 2475.64   643.7 2481.53     692 2484.37   740.9 2491.01     746 2492.74
   770.2 2497.43   809.3 2511.34     819 2516.01   877.7 2540.57   913.7 2553.94
#Mann= 7 ,-1 , 0
       0     .12       0      40     .04       0     270    .035       0
   422.2    .045       0   440.4    .035       0   511.8     .05       0
  819.67      .1       0
#XS Ineff= 2 , 0
                          456.58          2476.9
Permanent Ineff=
       F       F
Bank Sta=422.2,440.4
XS Rating Curve= 0 ,0
Exp/Cntr(USF)=0,0
Exp/Cntr=0.3,0.1

Type RM Length L Ch R = 1 ,39328   ,260.8,270.2,270.8
XS GIS Cut Line= 2
2156208.15999174240947.2646441072155595.50954903241597.810990493
#Sta/Elev= 30
       0 2516.43    39.6 2509.85    56.8  2508.6    87.5 2502.14   104.6 2497.54
   116.2 2490.78   133.4 2490.41   140.1 2489.04   163.1 2477.45   168.8 2476.37
   240.2 2474.68   356.2 2474.88     391 2471.59     429    2473   444.4 2470.06
   458.4 2469.04   465.1 2470.14   474.6 2472.45   565.1 2471.77     590 2473.71
   609.1 2482.01   625.5 2484.94   709.6 2510.33   741.5 2515.16   760.1 2522.58
   789.6 2529.92   803.1 2531.21   845.9 2542.45   884.2 2554.17   893.6 2555.41
#Mann= 6 ,-1 , 0
       0     .12       0      40     .04       0     180    .035       0
   444.4    .045       0   465.1    .035       0     610     .05       0
#XS Ineff= 2 , 0
                          482.89         2475.09
Permanent Ineff=
       F       F
Bank Sta=444.4,465.1
XS Rating Curve= 0 ,0
Exp/Cntr(USF)=0,0
Exp/Cntr=0.3,0.1

Type RM Length L Ch R = 1 ,39058   ,284,286.5,287.1
XS GIS Cut Line= 3
2156133.94718038240838.3139210482155595.50954903241198.325005941
 2155494.4538059241553.599102875
#Sta/Elev= 30
       0 2504.14    33.3 2503.34    61.8 2502.07    85.5 2500.86    96.9 2496.79
     109 2487.73   126.4 2487.42   144.4 2479.43   184.2 2475.22   203.9 2474.02
     271 2470.13   361.8 2470.95   428.9 2468.97   511.7 2470.64   534.7 2467.48
   543.3 2466.97   553.6 2467.82   574.9 2470.71   616.3  2470.2   658.9    2478
   718.2 2484.15   789.9 2501.08   810.3 2510.05   823.6 2512.37   868.3 2535.99
   878.6 2543.41   895.6 2545.93   908.6  2555.7     957 2578.51  1017.1 2599.97
#Mann= 9 ,-1 , 0
       0     .12       0    33.3      .1       0    61.8     .04       0
   184.2     .06       0   203.9    .035       0   534.7    .045       0
   553.6    .035       0   658.9     .05       0   908.6      .1       0
#XS Ineff= 2 , 0
          280.41    2480  601.24         2480.91
Permanent Ineff=
       F       F
Bank Sta=534.7,553.6
XS Rating Curve= 0 ,0
Exp/Cntr(USF)=0,0
Exp/Cntr=0.3,0.1

Type RM Length L Ch R = 1 ,38771   ,164.9,167.8,166.1
XS GIS Cut Line= 3
2156059.73436902240678.8353264242155361.81814305241008.845487576
2155178.65460863241379.909544374
#Sta/Elev= 30
       0 2510.88    36.4 2507.01      47 2508.86   123.4 2502.59   138.1 2492.12
     169 2491.98   203.4 2480.83   241.6 2479.73   256.4 2474.67   268.7 2472.86
   384.8 2467.92   395.7 2469.09   588.1 2468.98   591.5 2468.72   596.4 2465.21
   601.4 2464.38   609.8 2465.38   617.1 2468.65   630.9 2469.72   704.2 2469.27
   813.8 2471.61     889 2482.92   918.4 2491.25   942.9 2504.79   956.5 2508.89
  1007.7  2534.8  1097.2  2572.9  1154.1 2596.06  1172.4 2597.21  1185.8 2604.12
#Mann= 9 ,-1 , 0
       0      .1       0      80     .04       0     190      .1       0
     410    .035       0   596.4    .045       0   609.8    .035       0
  822.01      .1       0  922.01    .035       0  932.01      .1       0
Bank Sta=596.4,609.8
XS Rating Curve= 0 ,0
Exp/Cntr(USF)=0,0
Exp/Cntr=0.3,0.1

Type RM Length L Ch R = 1 ,38603   ,199.3,189,178.6
XS GIS Cut Line= 3
2155930.01115073240561.9305509612155321.73694188240855.580169028
2155123.63997731241326.351778945
#Sta/Elev= 30
       0 2507.37    49.2 2503.82    71.1 2498.83   114.8 2498.08   129.3  2490.3
   162.1  2486.2   180.3 2480.46   191.3 2480.28   224.1 2489.77   291.7 2485.28
   314.9 2478.83   341.9 2466.65   511.4 2467.76   519.2 2467.53   526.2 2464.56
   533.5 2463.01   544.92464.633     563 2467.69   588.4 2467.07   616.2    2469
   651.5 2468.02   825.5 2470.35   861.5  2473.3     889 2477.54   921.6 2487.22
   953.6 2501.36   967.8 2504.94     975 2509.71  1120.9 2571.43  1186.2 2592.61
#Mann= 10 ,-1 , 0
       0      .1       0      50     .04       0     160     .05       0
     270      .1       0     380    .035       0     490      .1       0
   526.2    .045       0   544.9      .1       0     600    .035       0
  995.45      .1       0
Bank Sta=526.2,544.9
XS Rating Curve= 0 ,0
Exp/Cntr(USF)=0,0
Exp/Cntr=0.3,0.1

Type RM Length L Ch R = 1 ,38414   ,437.9,436.5,436
XS GIS Cut Line= 2
     2155530.525      240322.147     2155125.822      241278.121
#Sta/Elev= 30
       0 2483.71    27.6 2477.14    48.9 2473.61   116.3 2472.66   130.9 2471.67
   141.6 2472.15   148.9 2470.83   159.4 2471.25     183 2469.77     219 2472.24
   234.2 2477.12   250.3    2477   258.7 2475.92   266.5 2473.67   280.5 2472.15
   317.6 2463.98   326.8 2462.97   337.5 2464.05   355.3 2464.76   371.6 2466.64
   460.7 2466.51   714.6 2469.88   772.2 2475.36   794.7 2479.46   817.2 2486.15
   832.7 2492.14   857.2 2503.34   868.4 2506.92  1007.4 2565.99  1038.1 2576.99
#Mann= 7 ,-1 , 0
       0      .1       0      40     .05       0      90      .1       0
   317.6    .045       0   337.5      .1       0     370    .035       0
     850      .1       0
Bank Sta=317.6,337.5
XS Rating Curve= 0 ,0
Exp/Cntr=0.3,0.1

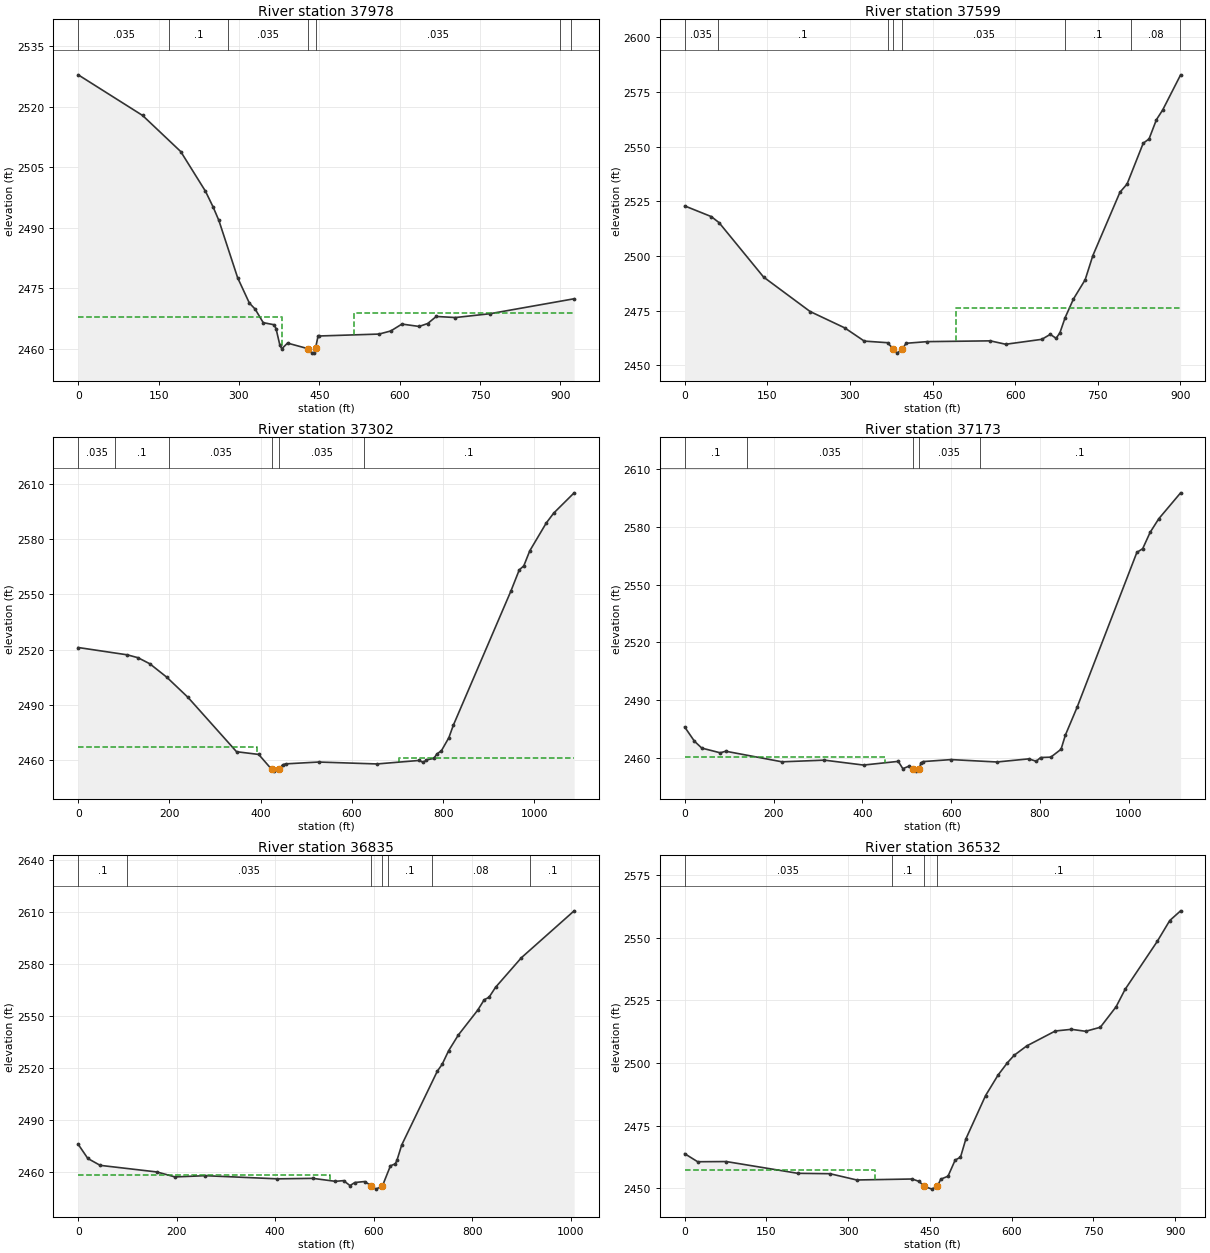
Type RM Length L Ch R = 1 ,37978   ,376.9,379,376.5
XS GIS Cut Line= 2
     2155154.261      240204.017     2154795.497      241057.175
#Sta/Elev= 30
       0 2527.95   120.1 2517.87   191.3 2508.91   237.5 2499.06   251.8 2495.14
   262.5 2491.81   297.6 2477.57   319.4 2471.31   330.1 2469.83   345.3 2466.45
   365.7 2465.93   369.2 2464.95   376.4 2460.83   379.9 2459.96   390.6 2461.38
   427.92460.024   436.9 2458.89   440.4 2458.98   442.92460.152   447.5 2463.06
     449 2463.14   561.4 2463.62   583.3 2464.39   604.1  2466.1   636.2 2465.51
   652.2 2466.24   668.2 2467.99   703.8 2467.72   767.9 2468.66   925.5 2472.38
#Mann= 7 ,-1 , 0
       0    .035       0     170      .1       0     280    .035       0
   427.9    .045       0   442.9    .035       0     900     .05       0
     920      .1       0
#XS Ineff= 2 , 0
          380.76 2467.79  514.78         2468.96
Permanent Ineff=
       F       F
Bank Sta=427.9,442.9
XS Rating Curve= 0 ,0
Exp/Cntr=0.3,0.1

Type RM Length L Ch R = 1 ,37599   ,299.4,296.8,291
XS GIS Cut Line= 2
      2154802.06      240112.139     2154478.297      240952.171
#Sta/Elev= 30
       0  2522.9    48.3 2518.01    62.4 2515.25   143.3 2490.33   227.7 2474.58
   290.5  2467.1   326.1 2461.04   368.3 2460.31   378.82457.413   385.9 2455.54
   394.72457.398   402.1 2460.05   440.2  2460.8   554.7 2461.16   582.8  2459.6
   648.3 2461.85   663.7 2464.13   674.2 2462.33   681.1  2464.8   690.6 2471.75
   705.8 2480.33     727  2489.1     741 2500.19   790.2 2529.17   803.1 2532.91
   832.4 2551.58     843 2553.55   856.4 2562.36   867.6 2566.73   900.3 2582.87
#Mann= 8 ,-1 , 0
       0    .035       0      60      .1       0     370    .035       0
   378.8    .045       0   394.7    .035       0     690      .1       0
     810     .08       0     900      .1       0
#XS Ineff= 2 , 0
                          492.78         2476.36
Permanent Ineff=
       F       F
Bank Sta=378.8,394.7
XS Rating Curve= 0 ,0
Exp/Cntr=0.3,0.1

Type RM Length L Ch R = 1 ,37302   ,136.5,128.7,115.7
XS GIS Cut Line= 3
      2154666.43        240066.2     2154395.169       240282.77
     2154362.356      241022.174
#Sta/Elev= 30
       0 2521.16   107.6 2517.19     131 2515.64   156.9 2512.36     194  2505.1
   240.6 2494.16   347.1 2464.69   395.6 2463.22   424.22455.107   428.4 2454.17
   440.12455.223   448.1 2457.59   454.6  2458.1   526.9  2459.1     655 2458.06
   746.9 2459.95   756.8 2458.86   763.3 2460.22   779.8 2461.09   786.3 2463.48
   796.2 2465.21   812.6 2472.33   822.4 2479.08   948.7 2551.85   966.9 2563.26
   976.8  2565.4   989.9 2573.56  1026.1 2588.66  1042.5 2594.03  1087.2 2604.99
#Mann= 6 ,-1 , 0
       0    .035       0      80      .1       0     200    .035       0
   424.2    .045       0   440.1    .035       0  627.11      .1       0
#XS Ineff= 2 , 0
          391.58 2467.16  702.16         2461.41
Permanent Ineff=
       F       F
Bank Sta=424.2,440.1
XS Rating Curve= 0 ,0
Exp/Cntr=0.3,0.1

Type RM Length L Ch R = 1 ,37173   ,321.3,338.4,347.7
XS GIS Cut Line= 3
2153936.61189032240060.7899521512154353.17638856240498.053307453
2154335.06488864241010.350019582
#Sta/Elev= 30
       0  2475.9      22 2468.48    38.5 2464.91      80 2462.45    92.4 2463.27
   219.2 2457.76   314.5 2458.63   402.6 2456.07   480.8 2457.99   491.2 2454.18
   504.6 2455.47   513.8 2454.12   520.9 2452.91   527.9 2454.21     532 2457.21
   537.2 2457.89   599.9 2458.92   702.8 2457.67   774.9  2459.3   791.4 2458.03
   801.3 2459.99   824.3 2460.19   847.3 2464.29   857.1  2471.7   883.4 2486.14
    1018  2566.8  1031.1 2568.75  1047.8 2577.22  1067.2  2584.3  1116.5 2597.83
#Mann= 5 ,-1 , 0
       0      .1       0     140    .035       0   513.8    .045       0
   527.9    .035       0  663.92      .1       0
#XS Ineff= 2 , 0
          450.71 2460.38
Permanent Ineff=
       F       F
Bank Sta=513.8,527.9
XS Rating Curve= 0 ,0
Exp/Cntr(USF)=0,0
Exp/Cntr=0.3,0.1

Type RM Length L Ch R = 1 ,36835   ,303.7,302.9,301.9
XS GIS Cut Line= 3
2153918.54178642240089.1307139592154076.32917544240293.652094028
     2154049.531      241041.862
#Sta/Elev= 30
       0  2476.2    19.5 2468.05    44.6 2464.08   159.9 2460.26   196.5 2457.41
   258.1 2458.12   404.2 2456.31   476.4 2456.58   522.3 2454.87   538.8 2455.27
   551.9 2452.41   561.7 2454.19   581.4 2454.74     5952452.392   604.4 2450.37
   617.62452.146     634 2463.83   643.8 2464.94   647.1  2466.9   656.9 2475.86
   729.2 2518.41     739 2522.34   752.1 2530.18   771.8 2539.22   811.2 2553.57
   824.4 2559.57   834.2    2561   847.3 2566.71   899.9 2583.81    1007 2610.84
#Mann= 7 ,-1 , 0
       0      .1       0     100    .035       0     595    .045       0
   617.6    .035       0  628.31      .1       0  718.31     .08       0
  918.31      .1       0
#XS Ineff= 2 , 0
          511.11 2458.28
Permanent Ineff=
       F       F
Bank Sta=595,617.6
XS Rating Curve= 0 ,0
Exp/Cntr=0.3,0.1

Type RM Length L Ch R = 1 ,36532   ,346.1,350,351.6
XS GIS Cut Line= 3
     2153753.435      240179.426     2153762.719      240634.332
     2153772.004      241089.237
#Sta/Elev= 30
       0 2463.86    23.8 2460.65    76.3 2460.72   207.5 2456.03   266.6 2455.87
   315.8 2453.37   417.5 2453.76   429.9 2452.81   439.9 2450.83   453.6 2449.72
   463.6 2450.91     470 2453.69   483.2 2454.88   496.3 2461.31   506.1 2462.46
     516 2469.78   552.1 2487.04     575 2495.22   592.2 2500.15   604.6 2503.12
   627.6 2506.85   680.1 2512.81   709.6 2513.47   735.8 2512.69   762.7  2514.3
   791.6 2522.47     808 2529.37   867.1 2548.55   890.1 2556.89     910 2560.75
#Mann= 4 ,-1 , 0
       0    .035       0     380      .1       0   439.9    .045       0
   463.6      .1       0
#XS Ineff= 2 , 0
          350.11 2457.44
Permanent Ineff=
       F       F
Bank Sta=439.9,463.6
XS Rating Curve= 0 ,0
Exp/Cntr=0.3,0.1

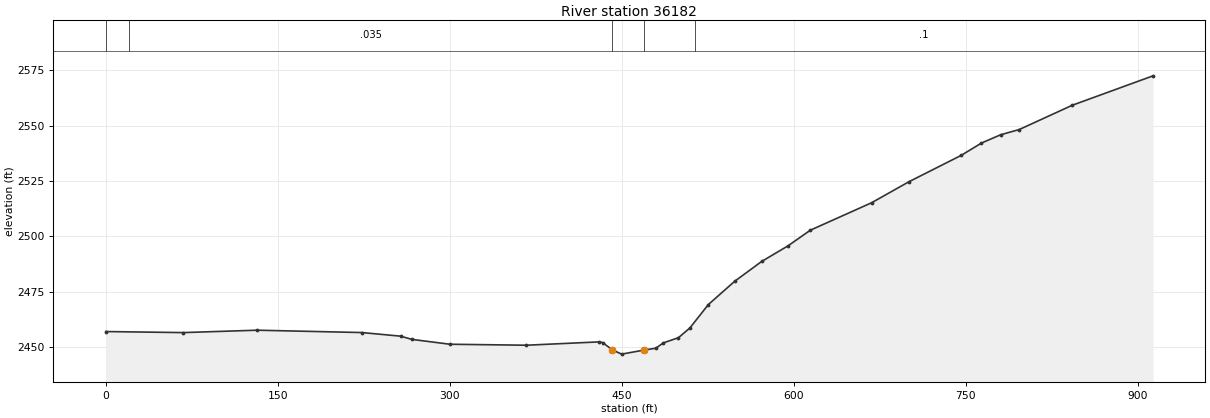
Type RM Length L Ch R = 1 ,36182   ,351.8,350,347.7
XS GIS Cut Line= 3
     2153493.767      240149.689     2153419.787       240597.78
     2153367.589      241054.067
#Sta/Elev= 30
       0 2457.07    67.5  2456.6     132 2457.68   223.3 2456.62   257.1 2454.99
     267 2453.53   300.2 2451.34   366.8  2450.9     430  2452.4   433.3 2452.11
   441.8  2448.8   449.9 2446.88   469.8 2448.74   479.7 2449.54   486.3 2451.95
   499.5 2454.31   509.4 2458.67   525.6 2469.28   548.6  2479.8   572.1 2488.73
   595.2 2495.81   614.5 2502.82     668 2515.23   700.4 2524.67   746.3 2536.66
   763.7 2542.14   780.4 2545.88   796.7 2548.26   842.9 2559.21   913.4  2572.5
#Mann= 5 ,-1 , 0
       0      .1       0      20    .035       0   441.8    .045       0
   469.8    .035       0  514.16      .1       0
Bank Sta=441.8,469.8
XS Rating Curve= 0 ,0
Exp/Cntr=0.3,0.1