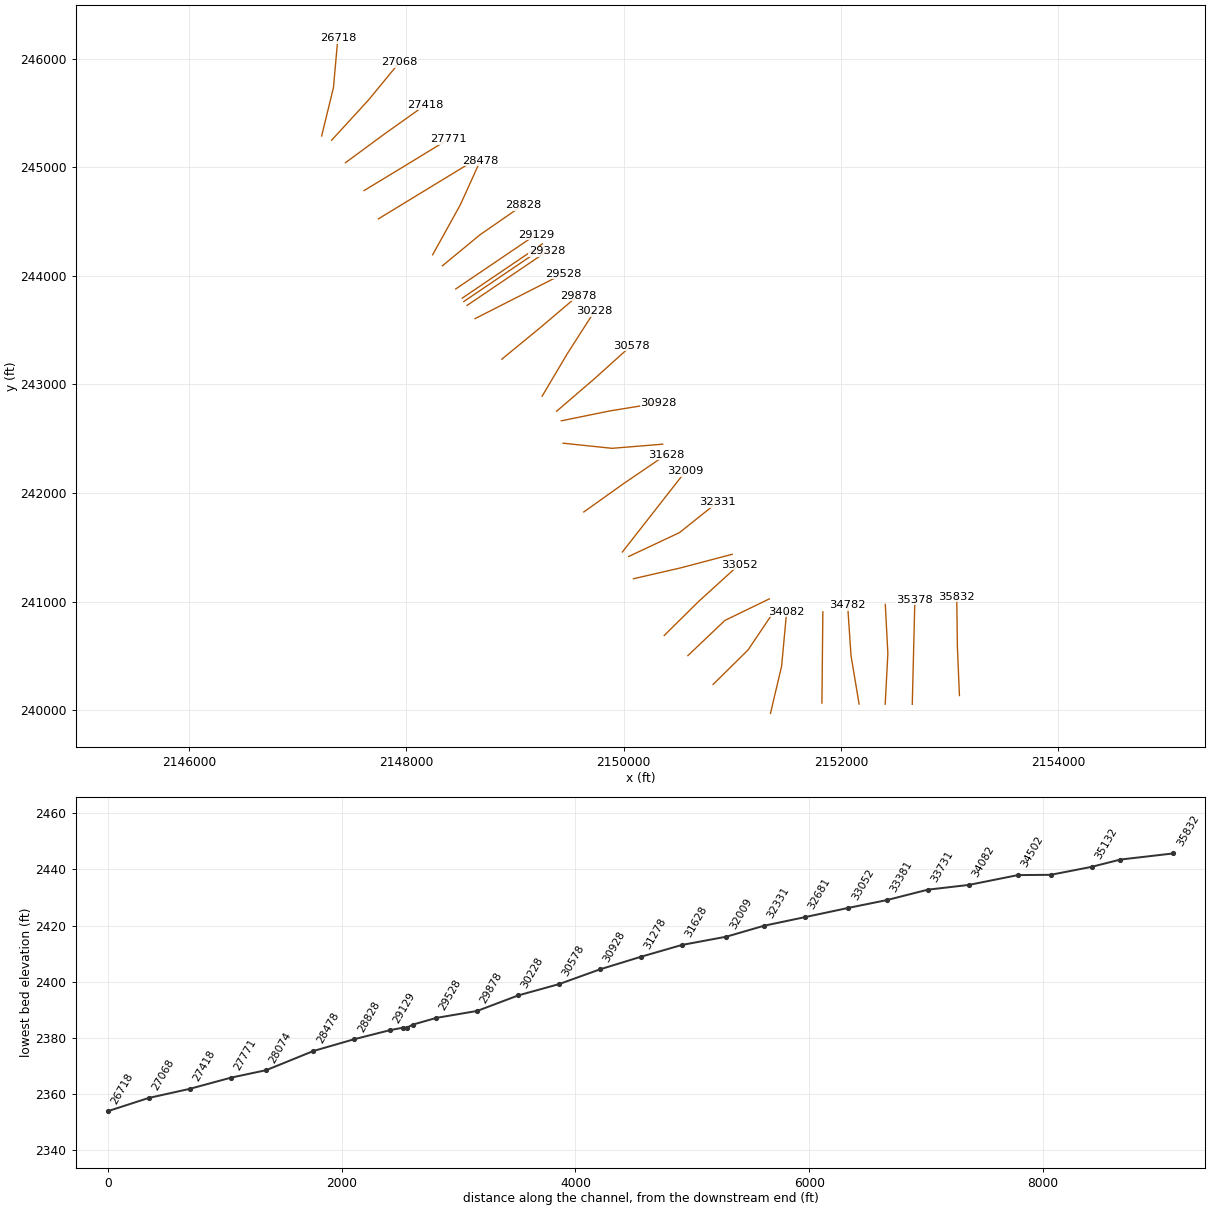
HEC-RAS study LAURELCK3.prj: LAURELCK3

--- LAURELCK3.g01 (geometry) --- (continued)

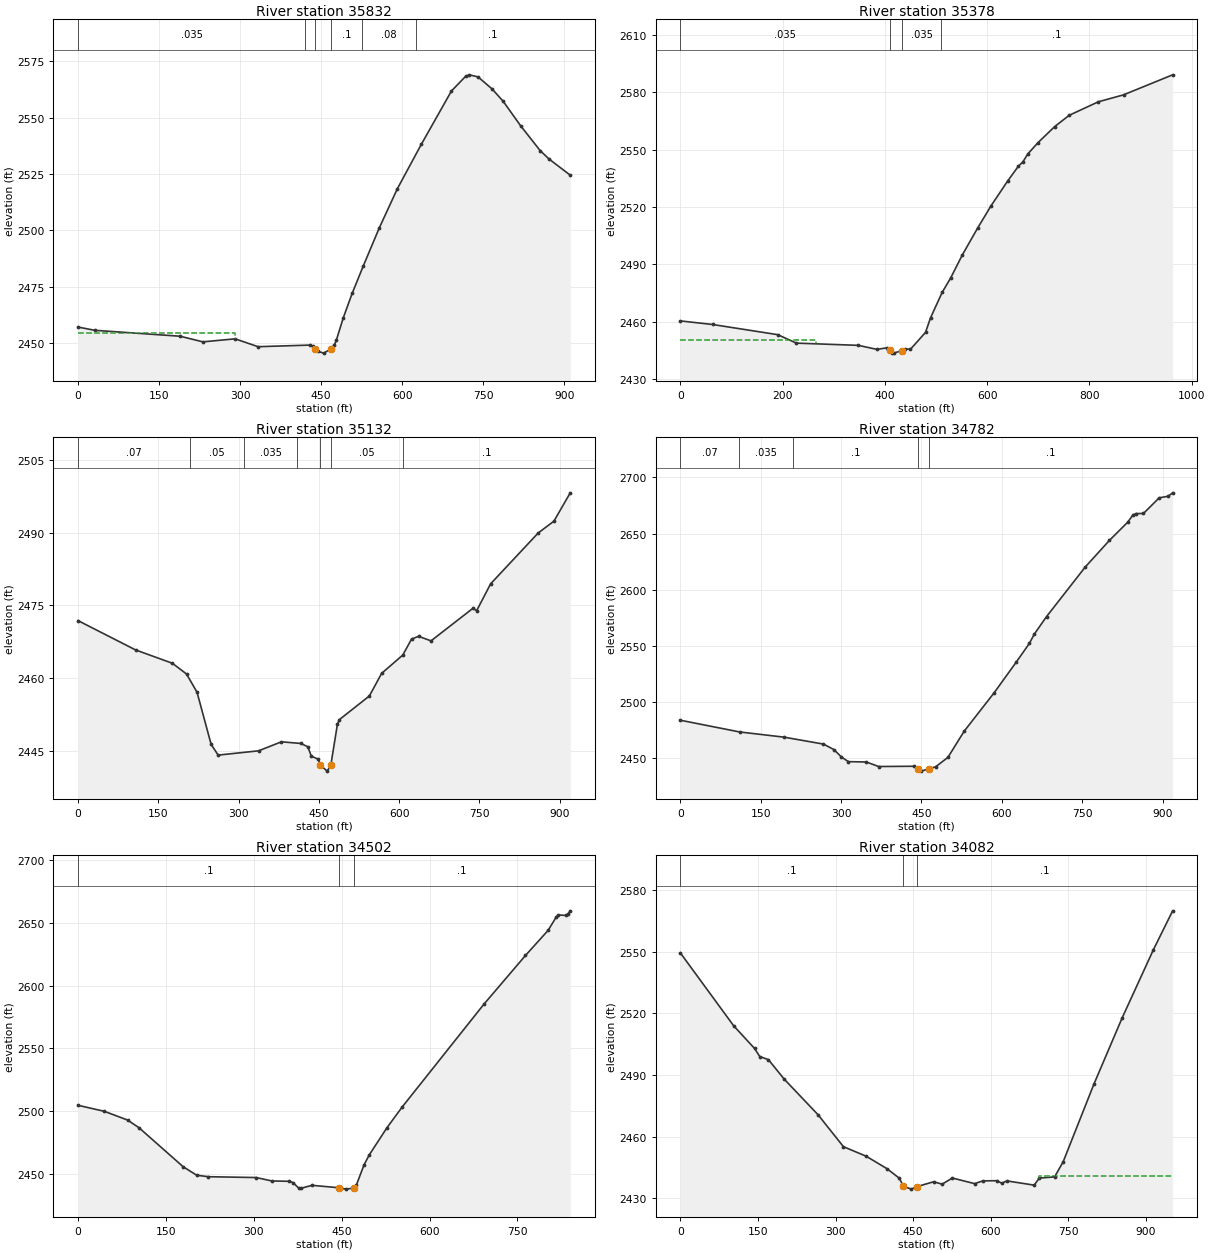
Type RM Length L Ch R = 1 ,35832   ,452.3,454.4,451.4
XS GIS Cut Line= 3
     2153089.913      240135.964     2153070.984      240590.402
     2153065.143      241046.312
#Sta/Elev= 30
       0 2457.19    31.1 2455.75   188.8 2453.13   231.1 2450.64   290.6 2451.97
   333.2 2448.49   428.5  2449.2     435  2448.6   439.2 2447.46   444.2 2446.39
   454.7 2445.64   467.8 2447.48   474.5 2449.38   477.8 2451.24   490.8 2461.27
   507.2  2472.1   527.6 2484.14   557.5 2501.18   590.8 2518.48   635.2 2538.19
     691 2561.85   717.1 2568.32   723.9    2569   740.1 2568.09     766 2562.78
   786.9  2557.2   818.9 2546.44     855 2535.44   871.4 2531.71   910.8 2524.51
#Mann= 6 ,-1 , 0
       0    .035       0     420      .1       0   439.2    .045       0
   467.8      .1       0  524.83     .08       0  624.83      .1       0
#XS Ineff= 2 , 0
          291.02 2454.66
Permanent Ineff=
       F       F
Bank Sta=439.2,467.8
XS Rating Curve= 0 ,0
Exp/Cntr=0.3,0.1

Type RM Length L Ch R = 1 ,35378   ,243.7,245.6,243.4
XS GIS Cut Line= 2
      2152656.04      240055.262     2152680.103      241017.799
#Sta/Elev= 30
       0 2460.32    62.9 2458.45   190.5 2453.11   226.7 2448.69   348.2 2447.52
   384.3 2445.41   403.9 2446.23   409.6 2444.89   413.8 2443.54   417.1 2443.45
   433.8 2444.82     440 2445.64     450 2445.49   479.4  2454.3   489.3 2461.98
   512.2 2475.37   528.7 2482.86   551.6 2494.97   581.2 2508.88   607.4 2520.53
   640.2 2533.63   661.1 2541.37   669.8 2543.57   679.6 2547.81   699.3 2553.65
   732.1  2562.1   760.4    2568   817.5 2575.09   866.7 2578.72   962.8 2589.21
#Mann= 4 ,-1 , 0
       0    .035       0   409.6    .045       0   433.8    .035       0
     510      .1       0
#XS Ineff= 2 , 0
          265.36 2450.44
Permanent Ineff=
       F       F
Bank Sta=409.6,433.8
XS Rating Curve= 0 ,0
Exp/Cntr=0.3,0.1

Type RM Length L Ch R = 1 ,35132   ,346,350,350.1
XS GIS Cut Line= 3
     2152406.993      240056.554     2152431.471      240522.391
     2152407.933      240975.086
#Sta/Elev= 30
       0 2471.86   107.4 2465.83   176.4 2463.07   202.7 2460.87   222.4 2457.11
   248.7 2446.38   261.8 2444.16   337.4 2445.04   380.1  2446.9   416.2 2446.56
   429.4 2445.88   435.9 2443.96   449.1 2443.29   452.6 2442.14   465.5 2440.86
   472.3 2442.03   484.7 2450.51   488.5 2451.48   544.4 2456.34   567.3 2460.99
   606.8 2464.76   623.2 2468.05   636.3 2468.63   659.6 2467.69   738.2 2474.42
   744.8 2473.89     771 2479.44     860 2489.92   889.3 2492.35   919.8 2498.18
#Mann= 7 ,-1 , 0
       0     .07       0     210     .05       0     310    .035       0
     410     .05       0   452.6    .045       0   472.3     .05       0
  606.48      .1       0
Bank Sta=452.6,472.3
XS Rating Curve= 0 ,0
Exp/Cntr=0.3,0.1

Type RM Length L Ch R = 1 ,34782   ,275.4,279.8,273.9
XS GIS Cut Line= 3
     2152166.803      240057.838      2152092.32      240504.757
     2152061.298      240969.588
#Sta/Elev= 30
       0 2483.42   110.5 2472.97   193.2 2468.34   267.1 2462.14   286.7  2457.2
   300.3 2450.73   313.6 2446.47   346.9 2446.19   370.2 2442.13   436.7 2442.37
   443.4 2440.27     450 2438.02   463.2 2440.07   476.4 2441.86   499.4 2450.29
   529.7 2473.62   585.2 2507.61   626.8 2535.17   651.5    2552   660.5 2560.12
   683.5 2575.89   755.8 2620.13   800.9 2643.87   834.8 2659.99   844.6 2666.38
   850.3 2667.75   864.4 2667.89   893.9 2681.86   910.4 2683.22   918.9 2686.29
#Mann= 5 ,-1 , 0
       0     .07       0     110    .035       0     210      .1       0
   443.4    .045       0   463.2      .1       0
Bank Sta=443.4,463.2
XS Rating Curve= 0 ,0
Exp/Cntr=0.3,0.1

Type RM Length L Ch R = 1 ,34502   ,422.4,420.2,417.3
XS GIS Cut Line= 2
     2151824.758        240066.2     2151833.508      240906.232
#Sta/Elev= 30
       0  2504.7    45.1 2499.88    84.5 2492.96   104.2 2486.79   179.6 2455.69
   202.6 2449.01   222.5 2447.82   304.3 2447.15   330.6 2444.44   360.1 2444.16
   366.7 2443.19   376.5 2438.86   379.8  2438.5   399.5 2440.96   445.4 2439.02
   457.4 2437.93   470.7  2438.8   474.9 2440.96   488.1 2457.22   497.2 2465.31
   527.4 2486.94   553.7 2503.64   692.8 2585.27   763.7 2624.05   802.3 2644.04
   816.2 2654.66     820 2656.32   832.6 2655.94   835.8 2656.76   840.1  2659.6
#Mann= 3 ,-1 , 0
       0      .1       0   445.4    .045       0   470.7      .1       0
Bank Sta=445.4,470.7
XS Rating Curve= 0 ,0
Exp/Cntr=0.3,0.1

Type RM Length L Ch R = 1 ,34082   ,358.9,350.7,339.9
XS GIS Cut Line= 3
     2151351.501      239971.864      2151453.91      240405.755
     2151500.598      240909.337
#Sta/Elev= 30
       0 2549.35   102.8 2513.97   143.3 2502.89   153.4 2498.96   170.2 2497.43
   200.5    2488     266 2470.65   315.2 2455.08     359 2450.46   399.5 2444.36
   423.1 2439.76  431.28 2435.77   446.6 2434.43   456.5 2435.58   489.5 2438.02
     506 2436.85   525.7 2439.84   568.6 2437.11     585 2438.45   611.4 2438.53
   621.3 2437.33   631.2 2438.43   683.9 2436.37   693.8 2439.81   723.4 2440.38
   739.9 2447.71   799.2 2485.41   854.1 2517.82   914.5 2550.99   951.6 2569.86
#Mann= 3 ,-1 , 0
       0      .1       0  431.28    .045       0   456.5      .1       0
#XS Ineff= 2 , 0
                          693.05         2440.84
Permanent Ineff=
       F       F
Bank Sta=431.28,456.5
XS Rating Curve= 0 ,0
Exp/Cntr=0.3,0.1

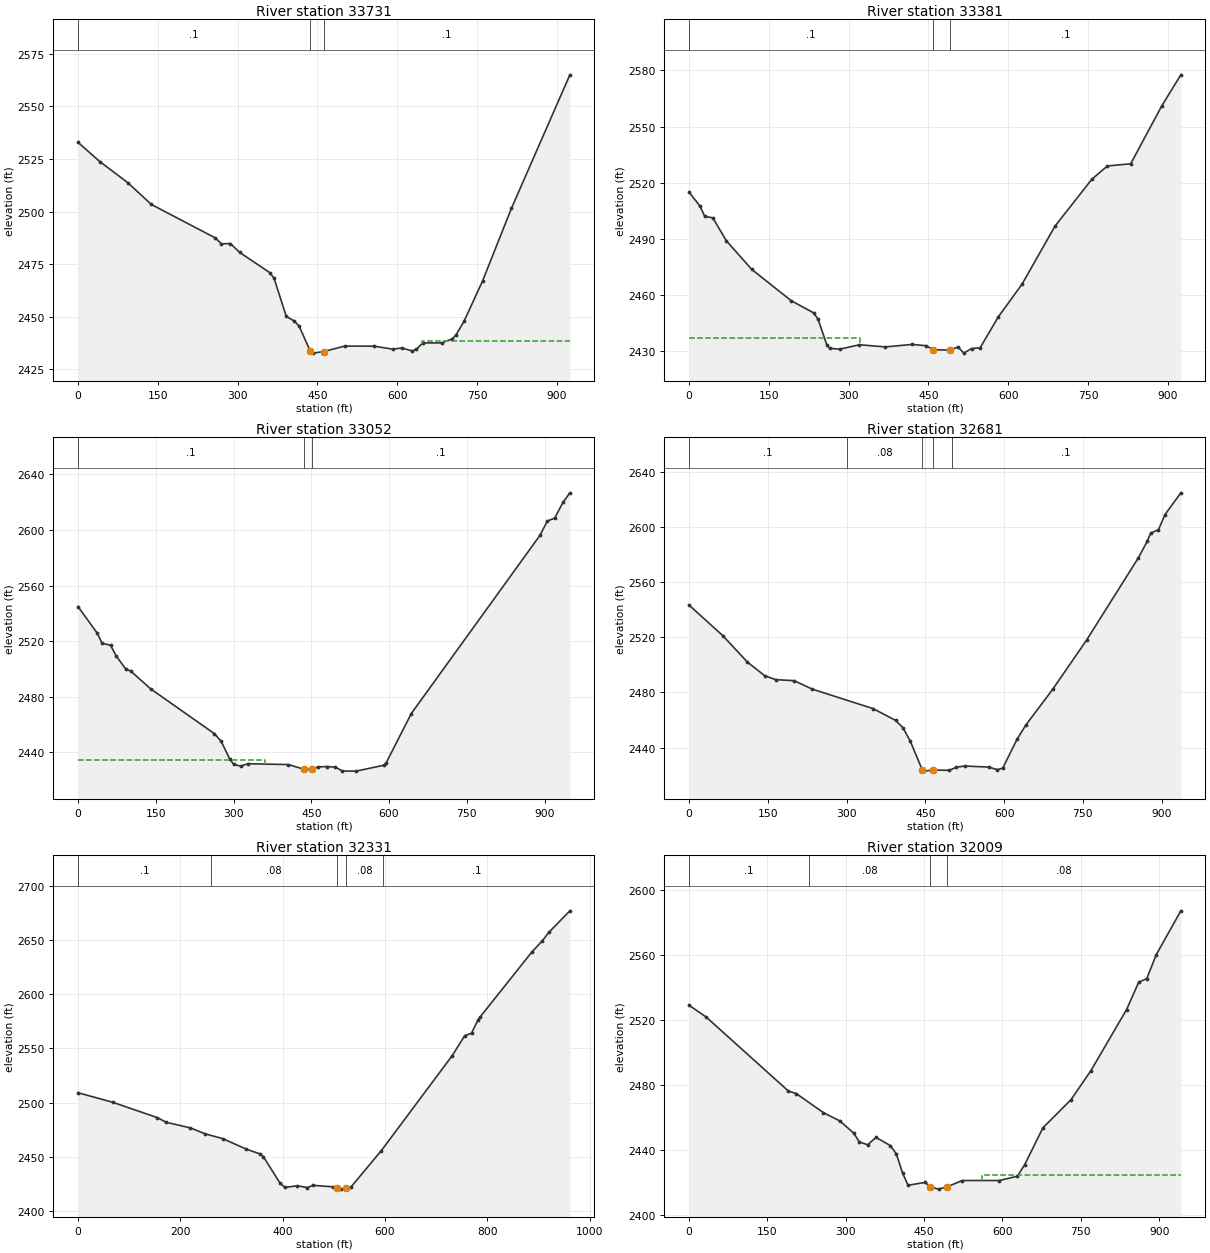
Type RM Length L Ch R = 1 ,33731   ,349.3,350.1,338.5
XS GIS Cut Line= 3
     2150823.704      240238.194     2151145.401      240555.762
     2151408.926      240947.934
#Sta/Elev= 30
       0 2532.91      41 2523.78    93.3 2513.79   137.9  2503.4   258.4 2487.45
   269.6 2484.66   286.4 2484.83   303.8 2480.62   360.1 2471.06   368.4  2468.4
   391.4 2450.22   406.5 2447.99   415.8 2445.49   436.7 2433.57   442.1 2432.74
     462 2433.51   501.6  2436.1     557 2436.04   592.4 2434.59   608.3 2435.21
   628.1 2433.81     636 2434.53   647.8 2437.58   683.4  2437.6   703.2 2439.48
     710  2441.2   725.4  2447.8   760.3 2466.97   814.6 2501.52   924.5 2565.01
#Mann= 3 ,-1 , 0
       0      .1       0   436.7    .045       0     462      .1       0
#XS Ineff= 2 , 0
                          645.97         2438.41
Permanent Ineff=
       F       F
Bank Sta=436.7,462
XS Rating Curve= 0 ,0
Exp/Cntr=0.3,0.1

Type RM Length L Ch R = 1 ,33381   ,326.4,329.1,336.2
XS GIS Cut Line= 3
     2150591.944      240503.678     2150932.274      240827.556
     2151341.213      241025.925
#Sta/Elev= 30
       0 2515.08      21 2507.42    29.6 2502.03    44.8 2501.29    70.4 2488.96
   118.2 2473.69   192.3    2457   234.3 2450.54   242.5 2447.21   258.9 2433.58
   264.4 2431.62   283.3 2431.14   320.1 2433.51   369.3 2432.36   419.1 2433.68
   445.4 2433.01   459.4 2430.87     490 2430.62   505.6 2432.34   516.5 2429.04
   531.1 2431.48   547.2 2431.91   581.5 2448.46   625.9 2465.85   687.9 2496.86
   757.2  2521.9   786.4 2528.97   830.1 2530.12   888.4 2560.98   924.3 2577.62
#Mann= 3 ,-1 , 0
       0      .1       0   459.4    .045       0     490      .1       0
#XS Ineff= 2 , 0
          321.98  2437.3
Permanent Ineff=
       F       F
Bank Sta=459.4,490
XS Rating Curve= 0 ,0
Exp/Cntr=0.3,0.1

Type RM Length L Ch R = 1 ,33052   ,375.8,370.9,360.3
XS GIS Cut Line= 3
     2150373.866      240688.646     2150691.505      241003.039
     2151062.895      241340.638
#Sta/Elev= 30
       0 2544.84      37  2525.7    46.5 2518.46    62.7 2516.92    73.9 2509.15
    92.4 2499.64   101.6 2498.42     140 2485.57   263.2 2453.25   276.2 2447.67
   292.4 2435.25   300.1 2431.13     314 2429.87   327.8 2431.59   405.9 2430.99
   436.2 2427.57   452.2 2427.53   462.5  2429.3   480.4 2429.55   496.6 2429.13
   509.9 2426.33   536.5 2426.26   589.7 2430.48   594.2 2432.07   642.9 2467.75
   891.2 2596.19   905.4 2606.52   919.3 2608.51   935.5 2619.86   948.8 2626.78
#Mann= 3 ,-1 , 0
       0      .1       0   436.2    .045       0   452.2      .1       0
#XS Ineff= 2 , 0
           361.5 2433.97
Permanent Ineff=
       F       F
Bank Sta=436.2,452.2
XS Rating Curve= 0 ,0
Exp/Cntr=0.3,0.1

Type RM Length L Ch R = 1 ,32681   ,345.2,350,351.4
XS GIS Cut Line= 3
     2150091.573      241211.262     2150530.049      241312.482
     2151000.253      241436.605
#Sta/Elev= 30
       0 2543.35    64.2 2521.26   111.3    2502   144.4 2492.06   165.2 2489.28
   200.3 2488.52   234.7 2482.41   350.4  2468.3   393.4 2459.76     407 2454.55
   421.1 2444.92  443.91 2424.07   448.1 2422.98     465 2423.81   495.5 2423.54
   509.1 2425.83   525.6 2426.69   570.2 2425.89   587.1 2424.08   597.3 2425.13
   624.4 2445.99   641.4 2456.45   692.2 2482.18   756.8 2517.87   855.2 2577.39
   872.2 2589.42   878.9 2595.45   893.7 2597.89   906.1 2608.83   936.3 2624.66
#Mann= 5 ,-1 , 0
       0      .1       0     300     .08       0  443.91    .045       0
     465     .08       0  500.01      .1       0
Bank Sta=443.91,465
XS Rating Curve= 0 ,0
Exp/Cntr=0.3,0.1

Type RM Length L Ch R = 1 ,32331   ,313.6,321.8,323.4
XS GIS Cut Line= 3
     2150047.045      241416.186      2150513.91      241635.606
     2150862.135      241913.416
#Sta/Elev= 30
       0 2509.09    67.5  2500.3   155.1 2486.06   172.4 2481.75   219.8 2476.53
   248.8 2471.01   283.4 2466.56   328.5 2456.96   354.9 2452.62   362.3 2449.92
   394.3 2425.85   404.2 2421.49   428.9 2423.05   448.2 2421.32     459 2423.43
   498.9 2422.05   506.2 2420.83   513.4 2419.92   524.5  2420.7   533.9  2422.1
   592.8 2455.52   731.3 2543.36   755.7  2561.8   769.1 2564.14   781.3 2576.02
   785.8  2579.1   886.4 2638.93   907.6 2649.65   920.1 2657.38   961.3 2677.33
#Mann= 5 ,-1 , 0
       0      .1       0     260     .08       0   506.2    .045       0
   524.5     .08       0  595.86      .1       0
Bank Sta=506.2,524.5
XS Rating Curve= 0 ,0
Exp/Cntr=0.3,0.1

Type RM Length L Ch R = 1 ,32009   ,385.5,381.1,374.7
XS GIS Cut Line= 2
     2149989.375      241457.503     2150569.085      242199.094
#Sta/Elev= 30
       0 2528.99    32.5 2521.83   190.2 2476.29   205.4  2474.7     257 2463.07
   288.8  2457.9   315.3 2450.44   326.1 2444.98     342 2443.27     358 2447.79
   385.4 2442.76   397.1 2437.53   408.8 2425.94   419.3 2418.41   452.6 2420.19
   460.9 2417.49   477.6 2416.03   494.2 2417.49   523.3 2421.32   594.2 2421.32
   628.5 2423.94   642.5 2431.04   677.4 2453.69   731.3 2471.02   769.1 2488.71
   837.5  2526.3   860.7 2543.07   876.2  2545.3     894 2559.82   941.3 2586.93
#Mann= 4 ,-1 , 0
       0      .1       0     230     .08       0   460.9    .045       0
   494.2     .08       0
#XS Ineff= 2 , 0
                          560.28         2424.45
Permanent Ineff=
       F       F
Bank Sta=460.9,494.2
XS Rating Curve= 0 ,0
Exp/Cntr=0.3,0.1

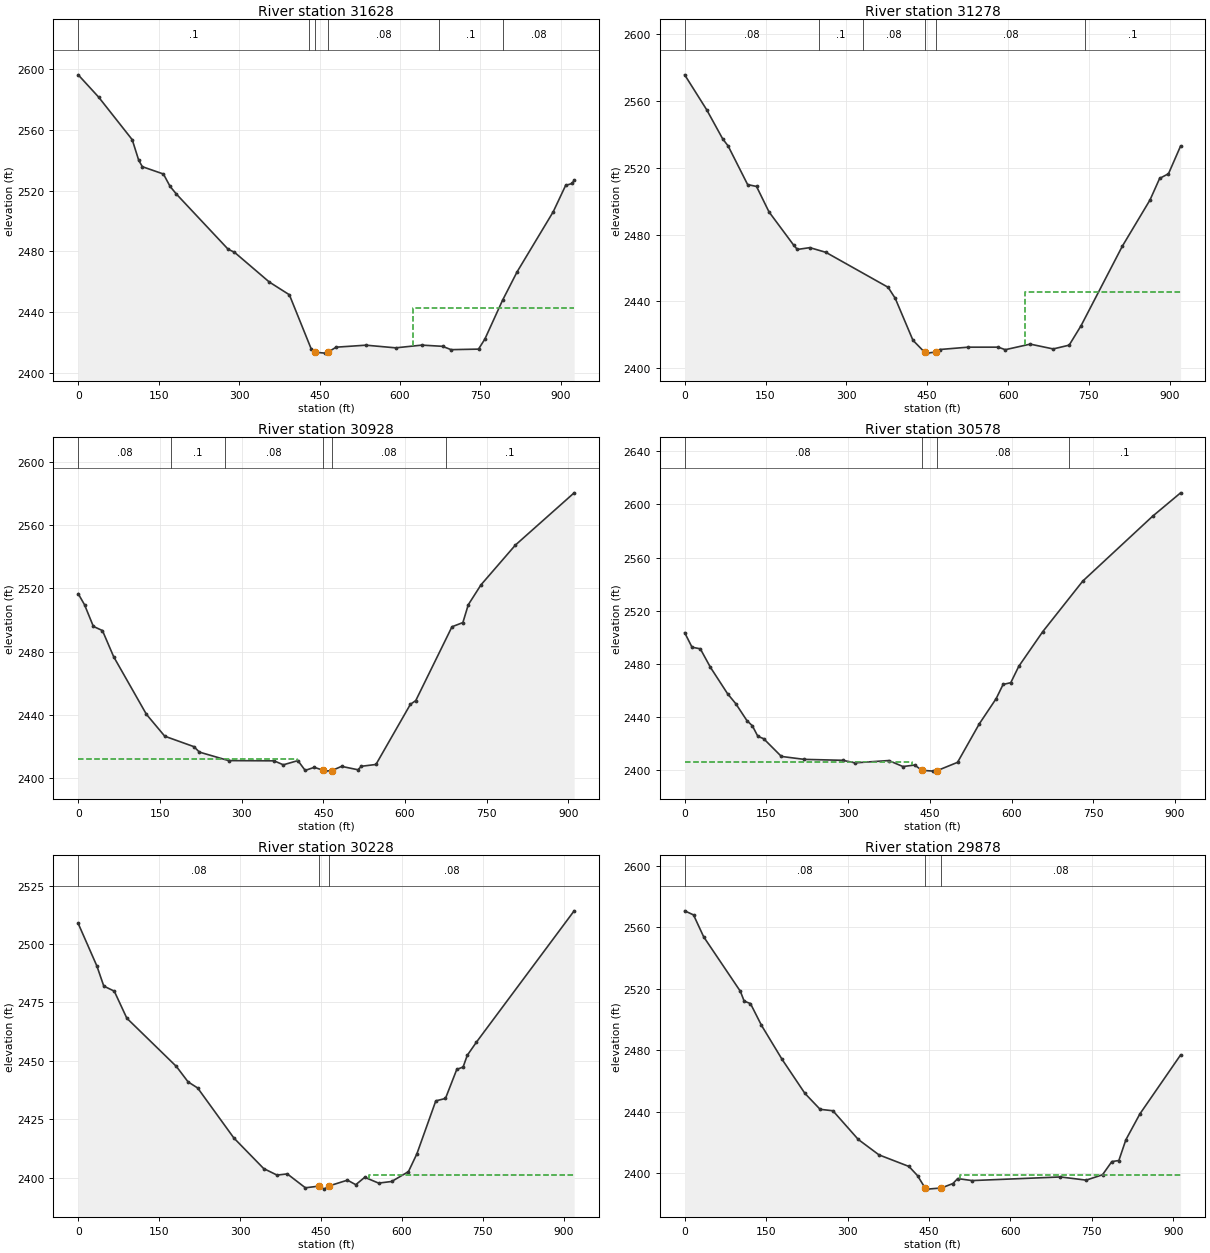
Type RM Length L Ch R = 1 ,31628   ,359.6,350,339.9
XS GIS Cut Line= 3
     2149634.311      241825.874     2150002.192      242088.208
     2150392.935      242354.531
#Sta/Elev= 30
       0 2596.27      38 2581.64   100.7 2553.57   112.8 2540.04   119.6  2535.8
   158.9 2530.98   171.3 2522.83   183.1 2517.76   279.5 2481.47   291.3 2479.48
   356.3 2459.88   393.7 2451.49   434.8 2415.53   441.8 2413.65   460.2 2413.08
   466.1 2413.76   480.8 2416.99   536.4 2418.31     592 2416.56   640.8 2418.35
   679.3 2417.56   695.2 2415.36   746.4 2415.72   758.2 2422.33   791.2 2447.88
   818.3 2466.57   885.7 2506.14   908.8 2523.47   921.1 2524.79   924.7 2526.94
#Mann= 6 ,-1 , 0
       0      .1       0     430     .08       0   441.8    .045       0
   466.1     .08       0  671.84      .1       0  791.84     .08       0
#XS Ineff= 2 , 0
                          623.73         2443.09
Permanent Ineff=
       F       F
Bank Sta=441.8,466.1
XS Rating Curve= 0 ,0
Exp/Cntr=0.3,0.1

Type RM Length L Ch R = 1 ,31278   ,346.3,350,351
XS GIS Cut Line= 3
     2149444.116      242458.868     2149894.444       242411.94
     2150360.174      242450.051
#Sta/Elev= 30
       0 2575.78    40.9 2554.79    70.6 2537.33    80.5 2533.18   116.8 2509.96
   133.3 2508.84   156.4  2493.6   202.5 2473.52   209.1 2471.06   232.2 2472.14
   261.9 2469.34   377.4 2448.37   390.6 2441.77   423.5  2416.6   445.1 2409.42
   449.9 2408.88   466.4 2409.57     473 2411.04   525.7 2412.45   581.6 2412.46
   594.8 2410.94   641.1 2414.28   683.7 2411.39   713.3 2413.66   735.5 2425.39
     812 2473.04   863.3 2500.74   881.2 2513.68   897.6 2516.46   920.1 2533.12
#Mann= 6 ,-1 , 0
       0     .08       0     250      .1       0     330     .08       0
   445.1    .045       0   466.4     .08       0  742.77      .1       0
#XS Ineff= 2 , 0
                           632.2         2445.59
Permanent Ineff=
       F       F
Bank Sta=445.1,466.4
XS Rating Curve= 0 ,0
Exp/Cntr=0.3,0.1

Type RM Length L Ch R = 1 ,30928   ,339.4,350,357.1
XS GIS Cut Line= 3
     2149427.545      242665.247     2149873.969      242756.224
     2150323.018      242829.212
#Sta/Elev= 30
       0 2516.68    11.6 2509.72    27.8 2496.02    44.5 2493.36    65.1 2476.81
   125.2 2440.38   158.9 2426.51   212.5 2419.89   222.5 2416.45   276.1 2411.07
   359.8 2410.92   376.5  2408.4   403.3 2411.07   416.7 2404.86   433.4 2406.81
   449.5 2404.99   453.4 2404.41   465.7 2404.79   483.5 2407.42   513.4 2405.29
     520 2407.48   546.6 2408.62   609.8 2446.67   619.7 2449.06   686.2 2495.78
   706.2 2498.43   716.1  2509.7   739.4 2522.29   802.6 2547.47   910.5 2580.55
#Mann= 6 ,-1 , 0
       0     .08       0     170      .1       0     270     .08       0
   449.5    .045       0   465.7     .08       0   675.6      .1       0
#XS Ineff= 2 , 0
          402.53 2411.81
Permanent Ineff=
       F       F
Bank Sta=449.5,465.7
XS Rating Curve= 0 ,0
Exp/Cntr=0.3,0.1

Type RM Length L Ch R = 1 ,30578   ,345.3,350,353.4
XS GIS Cut Line= 3
     2149384.326      242753.426     2149729.685      243050.175
     2150067.739       243354.82
#Sta/Elev= 30
       0 2503.43    13.5 2492.48    28.7 2491.29    47.2  2477.4    78.9 2457.37
    93.8 2449.97   114.2 2437.25   124.3 2433.26   134.3  2425.4     145 2423.58
   177.5 2410.23   219.4 2408.02   290.4 2407.31   312.5 2405.39   374.7 2407.13
   400.7 2402.62   422.3 2403.74   435.3 2399.79   456.5 2399.16  463.98 2399.62
   500.9 2405.78   540.8 2434.75   571.8 2453.78   584.5 2464.44   598.6 2465.77
   613.3 2478.09   657.4 2504.26   730.8 2542.31   858.8 2591.08   910.4 2608.77
#Mann= 4 ,-1 , 0
       0     .08       0   435.3    .045       0  463.98     .08       0
  705.34      .1       0
#XS Ineff= 2 , 0
          417.98 2406.21
Permanent Ineff=
       F       F
Bank Sta=435.3,463.98
XS Rating Curve= 0 ,0
Exp/Cntr=0.3,0.1

Type RM Length L Ch R = 1 ,30228   ,354,350,343.9
XS GIS Cut Line= 3
     2149250.663       242891.38     2149482.166      243282.486
     2149732.798      243673.673
#Sta/Elev= 30
       0 2508.79    34.6 2490.59    47.4    2482    66.8 2479.84    90.1 2468.26
     182  2447.6   203.6 2441.02   221.4  2438.4   288.4 2417.03   343.7 2403.93
   368.4 2401.14   387.5 2401.64     421  2395.7   446.8 2396.43   456.1 2395.13
   464.5 2396.47     499 2398.97   514.4 2397.03     531 2400.19   556.7 2397.71
   580.9  2398.4     612 2402.61   627.6 2410.21   662.7 2432.89   680.6 2433.92
   701.6 2446.36   713.3 2447.37     721 2452.37   737.6 2457.89   919.1  2514.2
#Mann= 3 ,-1 , 0
       0     .08       0   446.8    .045       0   464.5     .08       0
#XS Ineff= 2 , 0
                          538.56         2401.18
Permanent Ineff=
       F       F
Bank Sta=446.8,464.5
XS Rating Curve= 0 ,0
Exp/Cntr=0.3,0.1

Type RM Length L Ch R = 1 ,29878   ,354.2,350,344.5
XS GIS Cut Line= 3
     2148880.001      243232.476     2149230.882      243520.436
     2149581.333      243818.008
#Sta/Elev= 30
       0 2570.66    16.3    2568      35 2553.75   102.6  2518.3   109.6 2511.92
   121.2 2510.33   141.5 2496.17   179.5 2474.01   221.5 2451.91   249.5 2441.54
   273.1  2440.6   319.8 2421.94     358  2411.9   413.2 2404.37     429  2398.4
   442.9 2390.35   442.9 2390.32   447.1 2389.62   472.8 2390.37   494.2 2393.25
     503 2396.49   529.4 2395.18   692.3 2397.54   739.7 2395.47   769.8 2398.97
     787 2407.55   799.9 2408.23   812.8  2421.7   838.7 2438.57   913.7 2476.93
#Mann= 3 ,-1 , 0
       0     .08       0   442.9    .045       0   472.8     .08       0
#XS Ineff= 2 , 0
                          507.42         2398.64
Permanent Ineff=
       F       F
Bank Sta=442.9,472.8
XS Rating Curve= 0 ,0
Exp/Cntr=0.3,0.1

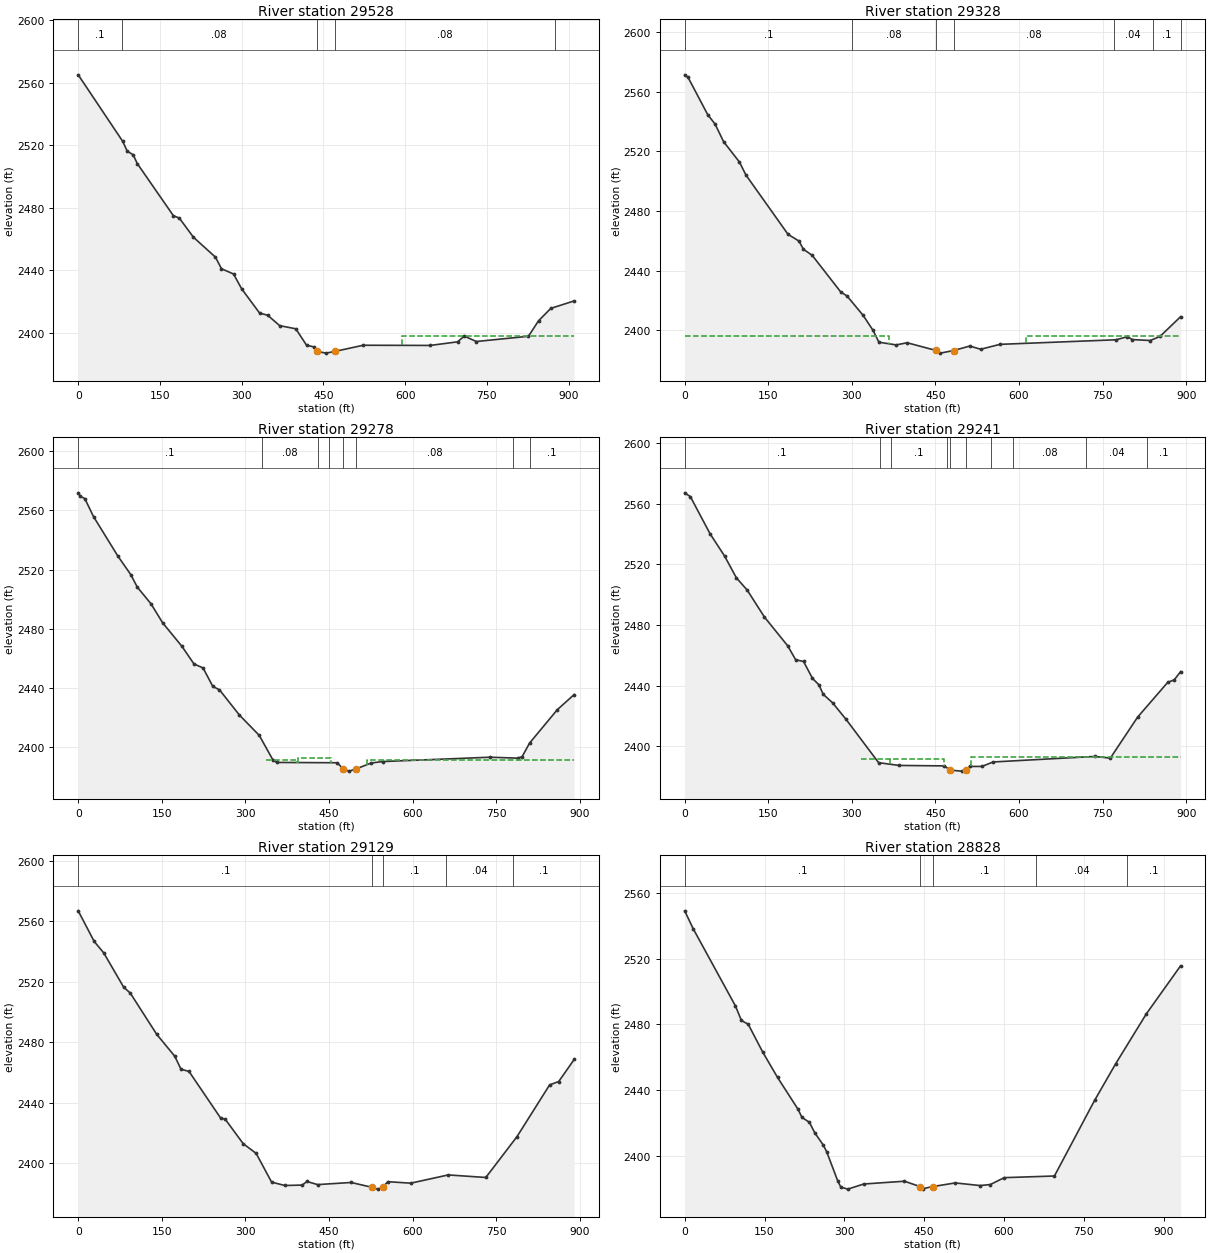
Type RM Length L Ch R = 1 ,29528   ,197.3,199.9,202.5
XS GIS Cut Line= 3
     2148633.678      243605.646     2149039.157      243812.074
     2149444.635      244018.501
#Sta/Elev= 30
       0 2565.08    81.4 2522.68    89.9 2516.32   100.9 2513.93   108.3 2508.38
   174.6 2475.03   185.6 2473.46   211.4 2461.26   251.9 2448.48   262.9 2441.07
     285 2437.75   299.8 2428.31   332.9 2412.72   347.6 2411.38   369.7 2404.71
   399.2  2402.7   418.9 2392.25   432.3 2391.12   437.5 2388.33   454.6 2387.14
   471.7 2388.29   522.9 2392.18   645.8 2392.06   696.1 2394.36   708.4 2398.04
   730.5 2394.57   826.2 2397.92   844.6  2407.8   867.2 2415.76     910 2420.52
#Mann= 5 ,-1 , 0
       0      .1       0      80     .08       0   437.5    .045       0
   471.7     .08       0     875      .1       0
#XS Ineff= 2 , 0
                          594.99         2398.39
Permanent Ineff=
       F       F
Bank Sta=437.5,471.7
XS Rating Curve= 0 ,0
Exp/Cntr=0.3,0.1

Type RM Length L Ch R = 1 ,29328   ,50.9,50,49.1
XS GIS Cut Line= 2
2148560.43611791243727.4712102462149297.19811791244226.602210246
#Sta/Elev= 30
       0 2571.29       6 2569.62    41.4 2544.56    54.5 2538.31    69.8 2526.51
    98.2 2512.87   109.9 2504.15   185.5 2464.36   205.1 2459.88     213 2454.39
   228.8 2450.32     280 2425.77   291.3 2423.07   320.2 2410.08   338.1 2399.96
   348.5 2392.11   379.4 2390.26   399.2 2391.72   450.8 2386.56   458.7 2384.76
   482.5 2386.49   511.6  2389.5   531.1 2387.36   565.9 2390.65   773.8  2393.7
   794.3 2395.74   803.5 2393.85   835.3 2393.22   852.8 2395.91   889.9 2409.17
#Mann= 7 ,-1 , 0
       0      .1       0     300     .08       0   450.8    .045       0
   482.5     .08       0     770     .04       0     840      .1       0
  889.92     .04       0
#XS Ineff= 2 , 0
          366.66 2396.55  612.82         2395.99
Permanent Ineff=
       F       F
Bank Sta=450.8,482.5
XS Rating Curve= 0 ,0
Exp/Cntr=0.5,0.3

Type RM Length L Ch R = 1 ,29278   ,35.9,37.1,35.8
XS GIS Cut Line= 2
2148530.16042279243763.2515772082149266.92242279244262.382577208
#Sta/Elev= 30
       0 2571.83     3.9 2569.47    11.8 2567.94    27.6 2555.68    71.2 2529.06
    94.2 2516.61     106  2508.1   130.7 2496.77   151.4 2484.02   186.2 2468.02
   207.6 2456.21   224.1 2453.41   241.6 2440.93   253.5 2438.68   289.2 2421.64
   324.9 2407.86   349.3 2391.32   356.4 2389.59   465.1 2389.37   475.4 2385.09
   486.3 2383.71   499.2 2385.28   525.8 2389.21   546.8 2390.19   739.1 2393.12
   788.5 2392.49   796.4 2393.41     810 2402.71   859.8 2425.29   889.9 2435.46
#Mann= 8 ,-1 , 0
       0      .1       0     330     .08       0     430      .1       0
     450     .08       0   475.4    .045       0   499.2     .08       0
     780     .04       0     810      .1       0
#XS Ineff= 4 ,-1
       0  336.26  2389.5  336.26  393.22 2391.36  393.66  452.942392.793
  517.35  889.752390.992
Permanent Ineff=
       F       F       F       F
Bank Sta=475.4,499.2
XS Rating Curve= 0 ,0
Exp/Cntr(USF)=0,0
Exp/Cntr=0.5,0.3

Type RM Length L Ch R = 1 ,29241   ,115.6,112.3,111.4
XS GIS Cut Line= 2
 2148516.6092886243795.059037986 2149253.3712886244294.191037986
#Sta/Elev= 30
       0 2567.18    10.2 2564.66    45.6 2540.16    71.6  2525.5    92.8 2511.12
   112.3 2502.98   143.1 2485.27     185 2466.22   199.1 2457.11   213.3 2455.96
   229.3 2444.84   240.9 2440.55   248.8 2434.21   265.3 2428.76   289.7 2417.73
     348 2389.23   384.8  2387.4   466.1  2387.1     476  2384.3   496.8 2383.65
   504.2 2384.11   511.6 2386.74   533.4 2386.75   553.5 2389.69   735.4 2393.33
   763.8 2392.23   812.8 2419.29   866.8 2442.22   878.5 2443.86   889.9 2449.31
#Mann= 10 ,-1 , 0
       0      .1       0     350     .08       0     370      .1       0
     470     .08       0     476    .045       0   504.2     .08       0
     550      .1       0     590     .08       0     720     .04       0
     830      .1       0
#XS Ineff= 4 ,-1
       0  315.72  2389.5  315.72  369.11  2391.9  369.11  465.62 2391.65
  514.07  889.77 2392.81
Permanent Ineff=
       F       F       F       F
Bank Sta=476,504.2
XS Rating Curve= 0 ,0
Exp/Cntr(USF)=0,0
Exp/Cntr=0.5,0.3

Type RM Length L Ch R = 1 ,29129   ,299,300.7,298.5
XS GIS Cut Line= 2
2148456.05789836243879.0052835512149192.81989836244378.137283551
#Sta/Elev= 30
       0 2566.85    28.7 2546.57    45.8 2539.03    81.5 2516.39    93.4 2512.45
   140.9 2485.13   173.2  2470.7   184.5 2462.03   198.8 2460.63   255.5 2429.79
   263.8    2429     296 2412.83   319.3  2406.4     347 2387.39   370.8 2385.15
     402 2385.43   410.4  2387.8   429.5 2385.75   489.7 2387.15   527.72383.903
   537.2 2382.75   546.1 2383.98   555.6 2387.67   596.7 2386.69     664 2392.14
   731.4 2390.46   787.4 2417.52   845.9 2451.71   862.2 2453.93   889.9 2468.51
#Mann= 5 ,-1 , 0
       0      .1       0   527.7    .045       0   546.1      .1       0
     660     .04       0     780      .1       0
Bank Sta=527.7,546.1
XS Rating Curve= 0 ,0
Exp/Cntr=0.3,0.1

Type RM Length L Ch R = 1 ,28828   ,342.2,350,354.2
XS GIS Cut Line= 3
     2148333.053      244091.647     2148680.237      244378.447
     2149076.104      244652.557
#Sta/Elev= 30
       0 2549.18      16 2538.26    95.2 2491.33   106.6 2482.35   119.4 2480.04
   146.5 2463.17   174.4 2447.69     213 2428.25   220.4 2423.24   234.3 2420.34
   244.3 2413.96   260.6 2406.35   266.8 2402.35   287.4 2384.75   293.3 2380.81
   306.6 2379.58   336.4  2382.7     413  2384.4   441.9 2381.16   447.1  2379.8
   465.9 2381.12   508.3 2383.36     555 2381.76   574.4 2382.39   600.3 2386.57
   694.7 2387.58   770.1 2433.62   809.8 2455.99   867.4  2486.4   931.8 2515.69
#Mann= 5 ,-1 , 0
       0      .1       0   441.9    .045       0   465.9      .1       0
  660.32     .04       0  830.32      .1       0
Bank Sta=441.9,465.9
XS Rating Curve= 0 ,0
Exp/Cntr=0.3,0.1

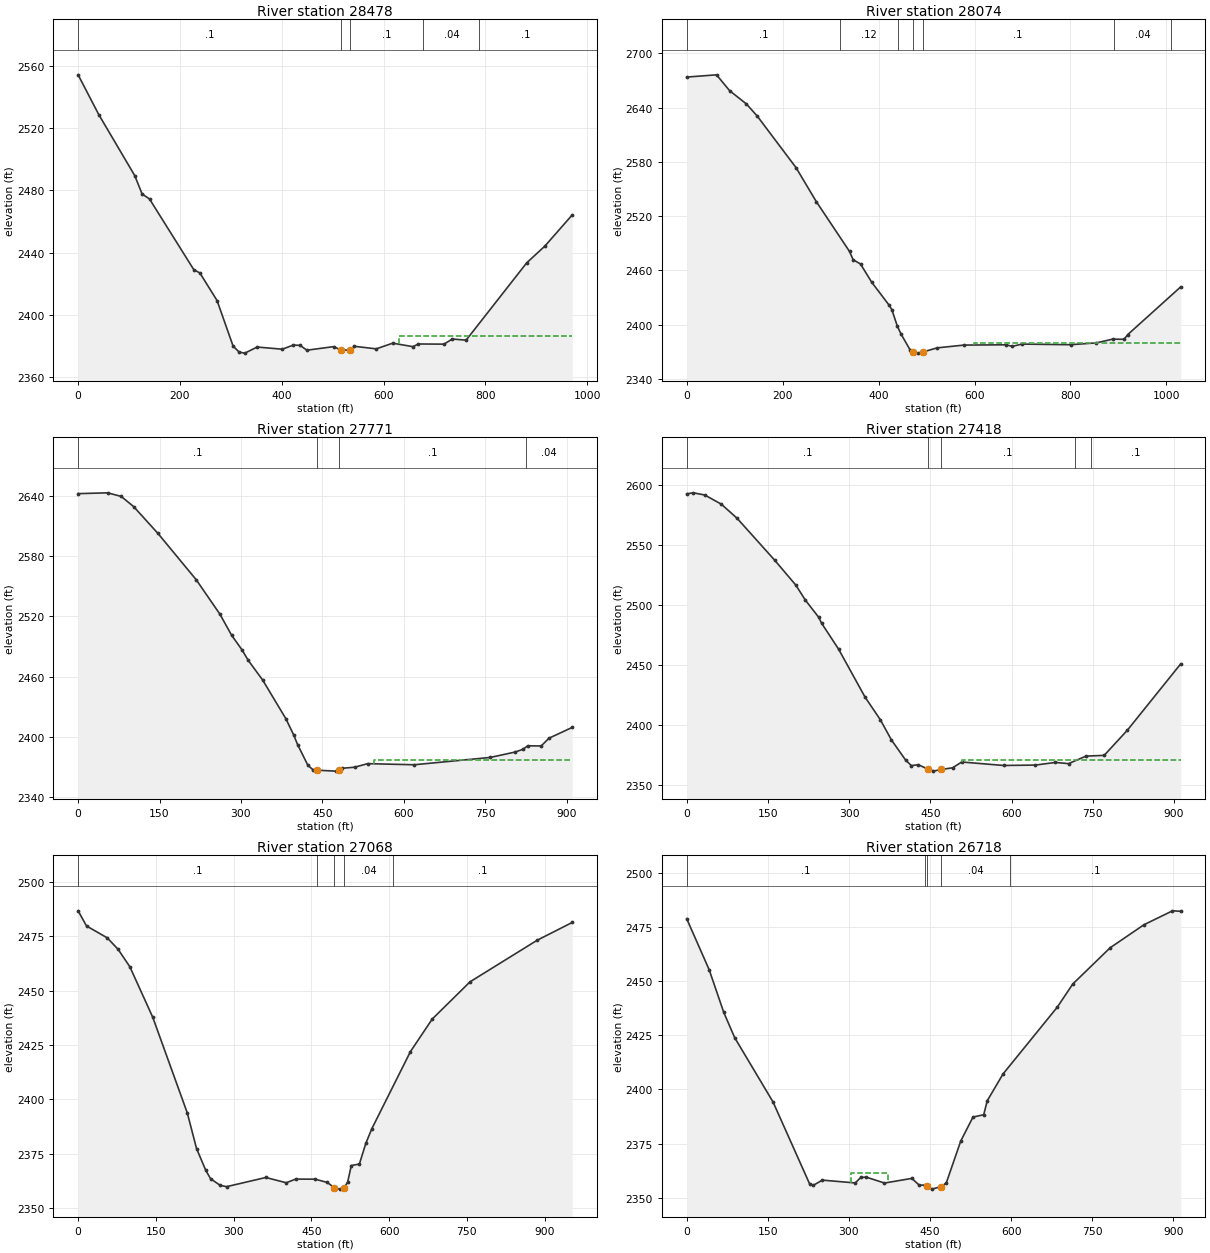
Type RM Length L Ch R = 1 ,28478   ,408,403.8,391.1
XS GIS Cut Line= 3
     2148243.732      244193.305     2148499.205      244655.578
     2148681.617       245058.17
#Sta/Elev= 30
       0 2554.37    40.5 2528.83   111.3 2489.49   125.7 2477.72   140.2 2474.53
   227.1  2429.1   239.2 2426.91   272.9 2409.18   304.4 2379.88   316.5 2375.98
   327.5 2375.38   351.6  2379.3     401  2377.9   422.7 2380.59     436 2380.36
   449.3 2377.26   501.6 2379.55   516.6 2377.35   533.9 2377.31   542.2 2379.78
   585.5 2378.13   617.9 2381.78   657.5 2379.54   668.3 2381.26   718.7 2381.16
   734.7 2384.46     762 2383.72   880.9 2433.41   916.8 2444.27   970.2  2464.2
#Mann= 5 ,-1 , 0
       0      .1       0   516.6    .045       0   533.9      .1       0
  678.17     .04       0  788.17      .1       0
#XS Ineff= 2 , 0
                          630.55         2386.32
Permanent Ineff=
       F       F
Bank Sta=516.6,533.9
XS Rating Curve= 0 ,0
Exp/Cntr=0.3,0.1

Type RM Length L Ch R = 1 ,28074   ,297.9,303.1,300.8
XS GIS Cut Line= 2
     2147744.914      244524.496     2148624.323      245060.454
#Sta/Elev= 30
       0  2673.7    62.2 2676.18    89.6 2658.59   124.6 2643.93   147.2 2630.48
   227.9 2573.62   270.2 2536.01   339.4 2480.98     347  2471.8   362.4 2467.06
   385.4 2447.14   421.5 2421.89   427.6 2416.72   439.2 2398.24   446.8 2389.71
   465.9 2371.95   471.9 2369.95   481.5 2368.56   492.2 2369.81   522.4  2374.4
   578.1 2377.46   666.5 2377.77   678.4 2375.99   698.9 2378.56   800.4 2377.85
   854.2 2379.91     888 2384.02   911.8 2383.84   919.5 2389.05  1029.9  2441.8
#Mann= 7 ,-1 , 0
       0      .1       0     320     .12       0     440      .1       0
   471.9    .045       0   492.2      .1       0     890     .04       0
    1010      .1       0
#XS Ineff= 2 , 0
                           598.8          2379.4
Permanent Ineff=
       F       F
Bank Sta=471.9,492.2
XS Rating Curve= 0 ,0
Exp/Cntr=0.3,0.1

Type RM Length L Ch R = 1 ,27771   ,349.3,353.3,353.4
XS GIS Cut Line= 3
     2147612.508       244784.47     2148001.461      245020.569
     2148389.703      245257.829
#Sta/Elev= 30
       0 2642.31    54.5 2643.12    79.4 2639.53   102.4 2629.35   147.1 2602.65
   217.5 2556.58     261  2522.4   282.8 2501.21     302  2486.6   313.5 2476.13
   339.8 2456.77   382.6 2418.18   397.2  2401.8   404.3 2392.32   423.4 2371.54
     433 2367.11   440.2  2366.8   474.7 2365.88   480.7 2366.55   486.2 2368.72
   509.5 2369.79   533.2 2373.32   619.1 2372.23   759.2 2379.51   805.2 2384.92
   819.6 2387.68   828.4 2391.12     853 2390.94   867.3 2398.66     910 2409.41
#Mann= 4 ,-1 , 0
       0      .1       0   440.2    .045       0   480.7      .1       0
     825     .04       0
#XS Ineff= 2 , 0
                          544.62         2377.36
Permanent Ineff=
       F       F
Bank Sta=440.2,480.7
XS Rating Curve= 0 ,0
Exp/Cntr=0.3,0.1

Type RM Length L Ch R = 1 ,27418   ,345.4,350,351
XS GIS Cut Line= 3
     2147441.441      245041.086     2147809.534      245312.047
     2148180.666       245575.65
#Sta/Elev= 30
       0 2593.06    12.2 2593.87    33.4 2592.05    63.9 2584.43      93 2572.67
   162.7  2537.6   201.5 2516.96   219.2  2504.4   243.7 2490.17   249.2 2485.13
   280.4 2463.65   329.2 2423.71   357.8 2404.58   378.1 2387.86   404.1 2371.23
   414.8 2366.47   427.6 2367.26  446.19 2363.42   455.5 2361.89   469.9 2363.27
     491 2364.66   507.9  2369.5   585.2 2366.61     644 2366.93   680.9 2369.15
   705.1 2368.13   737.2 2374.39     771 2375.03   813.7 2395.97   912.3  2451.3
#Mann= 5 ,-1 , 0
       0      .1       0  446.19    .045       0   469.9      .1       0
  717.07     .04       0  747.07      .1       0
#XS Ineff= 2 , 0
                          507.55         2371.43
Permanent Ineff=
       F       F
Bank Sta=446.19,469.9
XS Rating Curve= 0 ,0
Exp/Cntr=0.3,0.1

Type RM Length L Ch R = 1 ,27068   ,339.9,350,357.3
XS GIS Cut Line= 3
     2147314.201      245247.906     2147657.156      245622.321
     2147939.758      245966.672
#Sta/Elev= 30
       0 2486.79    16.2 2479.83    56.3 2474.33    77.3 2469.03    99.8 2461.05
     144 2437.79   210.7 2393.71   228.5 2377.35   246.3 2367.32   255.5 2363.48
   273.9 2360.43   286.4 2359.79   362.2 2364.02   401.6 2361.59   419.8 2363.28
   457.4 2363.24   480.6 2361.75   494.5 2359.31   504.4 2358.66   513.1  2359.2
   520.1 2361.92   527.1 2369.53   542.7  2370.2   555.1 2379.71   566.7 2386.47
   641.3 2422.02   683.3 2436.98   756.3 2454.12   885.6 2473.23   953.2 2481.42
#Mann= 5 ,-1 , 0
       0      .1       0     460     .04       0   494.5    .045       0
   513.1     .04       0  607.74      .1       0
Bank Sta=494.5,513.1
XS Rating Curve= 0 ,0
Exp/Cntr=0.3,0.1

Type RM Length L Ch R = 1 ,26718   ,340.3,350,351.1
XS GIS Cut Line= 3
       2147222.6      245287.473     2147331.185      245732.875
     2147371.573      246186.182
#Sta/Elev= 30
       0 2478.75    41.5 2455.23    68.6 2435.47    88.8 2423.82   159.6  2394.2
   227.3 2356.36     234  2355.7   250.9  2358.1   311.7 2356.81   321.8 2359.33
     332 2359.49   365.7 2356.76   416.4 2358.91   429.9 2355.78     440 2355.81
  444.43 2355.22   453.5 2353.95   470.1  2355.1     480 2356.81   506.7 2376.11
   529.4 2387.22   549.2 2388.28   555.8 2394.77     585 2407.12   685.2 2437.92
   713.9 2448.61     783 2465.34   845.6 2475.98   898.3 2482.39   913.5 2482.18
#Mann= 5 ,-1 , 0
       0      .1       0     440     .04       0  444.43    .045       0
   470.1     .04       0  598.45      .1       0
#XS Ineff= 1 ,-1
  303.25   372.8 2361.44
Permanent Ineff=
       F
Bank Sta=444.43,470.1
XS Rating Curve= 0 ,0
Exp/Cntr=0.3,0.1