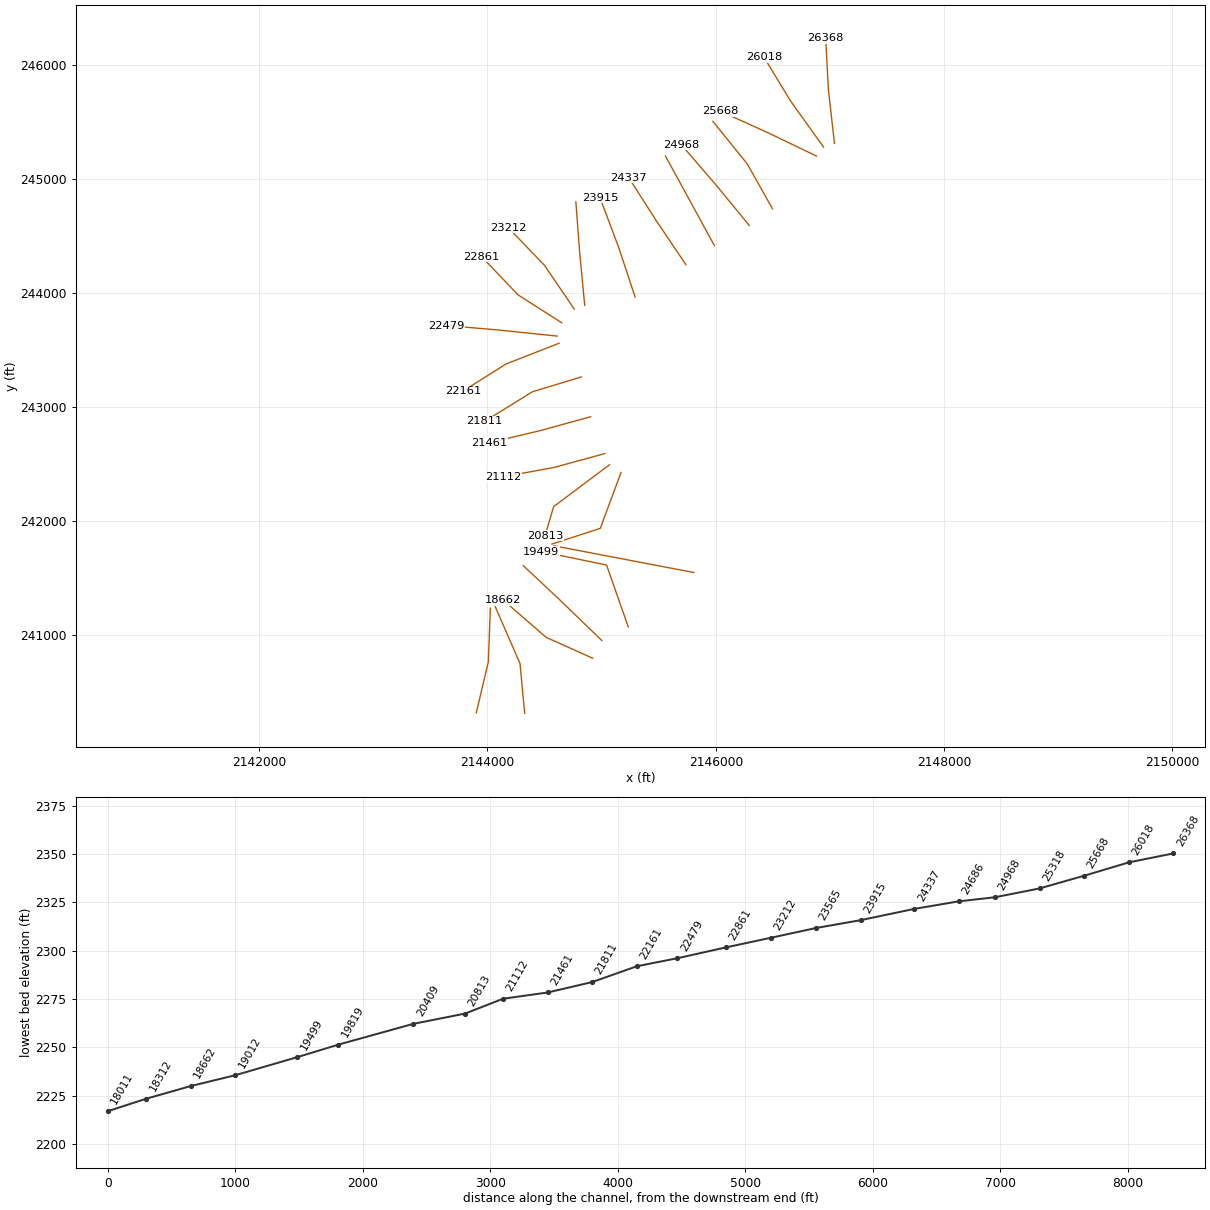
HEC-RAS study LAURELCK3.prj: LAURELCK3

--- LAURELCK3.g01 (geometry) --- (continued)

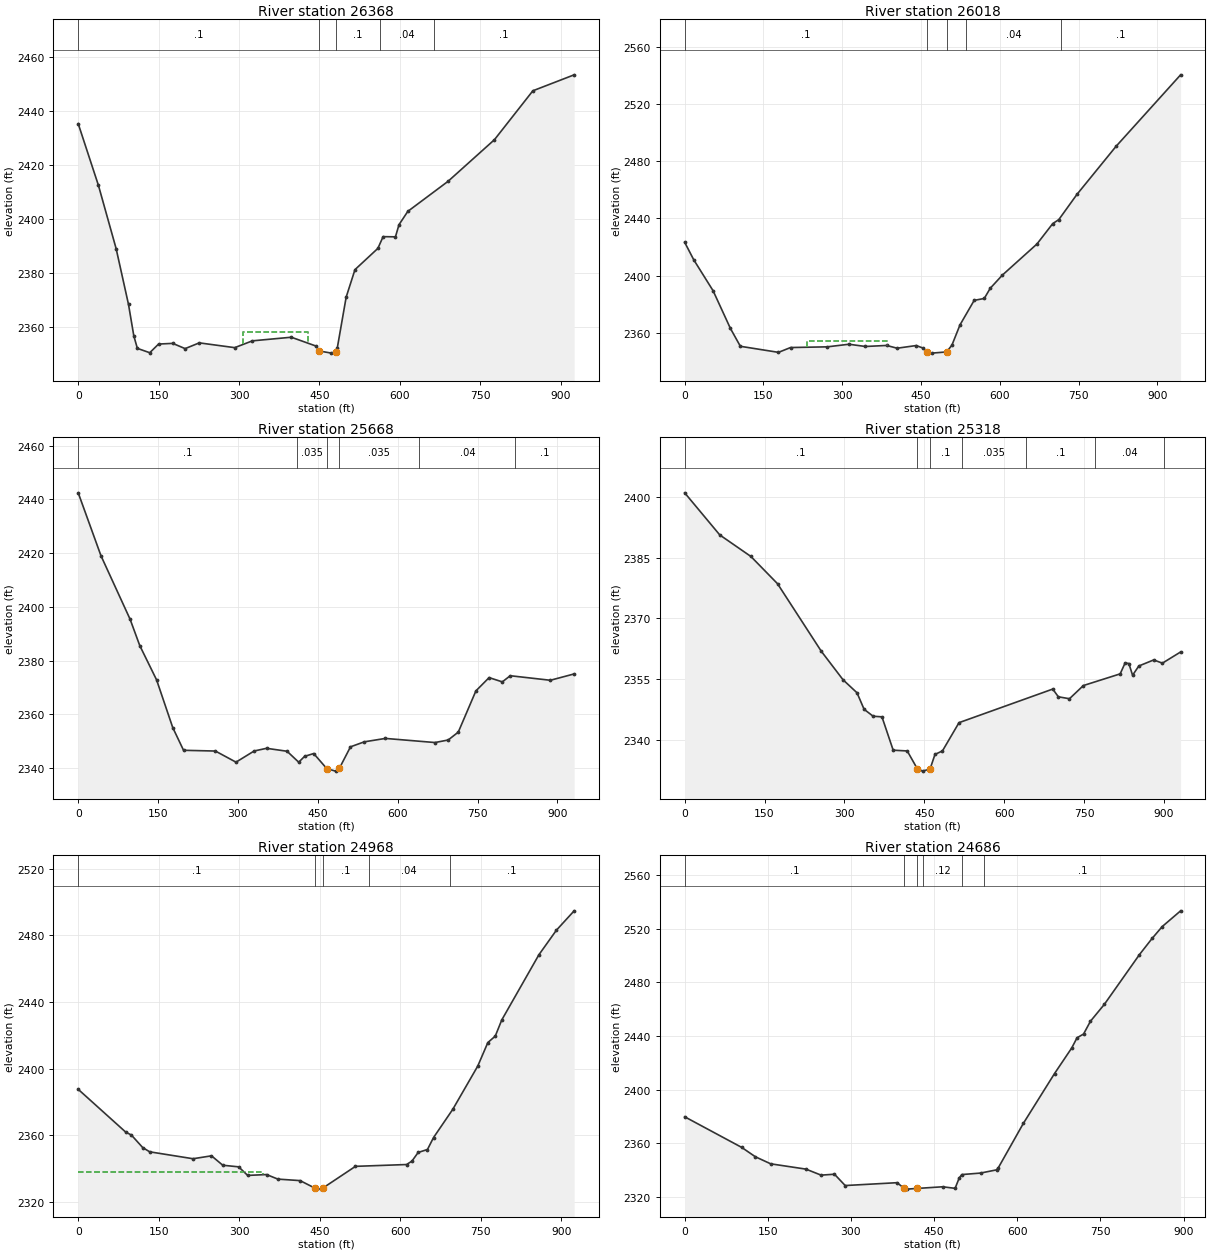
Type RM Length L Ch R = 1 ,26368   ,331.1,350,354.5
XS GIS Cut Line= 3
     2147040.005      245313.384     2146986.956      245783.622
     2146963.209      246234.782
#Sta/Elev= 30
       0 2435.32    37.7 2412.49    70.7 2389.07    93.8 2368.39   103.7 2356.75
   110.3 2352.11   133.4  2350.5   149.9 2353.71   176.3 2353.96   199.4 2352.02
   225.8 2354.15   291.9 2352.38   324.9  2354.9   397.5 2356.24   443.8 2352.95
  449.71 2351.14   472.4 2350.35     480 2350.91   483.3 2352.35   499.8 2371.11
   516.2 2381.27   558.9 2389.14   568.7 2393.49   591.7 2393.42   598.3 2397.91
   614.7 2402.84   689.7 2413.96   776.4 2429.41     848 2447.51     925 2453.42
#Mann= 5 ,-1 , 0
       0      .1       0  449.71    .045       0     480      .1       0
  563.22     .04       0  663.22      .1       0
#XS Ineff= 1 ,-1
  307.96  429.26    2358
Permanent Ineff=
       F
Bank Sta=449.71,480
XS Rating Curve= 0 ,0
Exp/Cntr=0.3,0.1

Type RM Length L Ch R = 1 ,26018   ,333.3,350,355.7
XS GIS Cut Line= 3
     2146944.529      245280.962     2146655.736      245684.707
     2146423.393      246067.392
#Sta/Elev= 30
       0 2423.28    17.3 2411.02    54.1 2389.37      87 2363.05     106 2350.49
   178.6 2346.25   201.5 2349.62   271.4 2350.11   312.8 2351.93     344 2350.36
   384.4 2351.08   404.5 2349.15   440.8 2351.02   453.9 2349.22   460.9  2346.7
   460.9 2346.66   470.4 2345.71   498.6 2346.55   508.8 2351.33   524.1 2365.47
   551.1 2382.64   570.3 2383.97   581.7 2391.11   604.7  2400.3   670.6 2422.09
   700.7 2436.39   712.2 2439.16   746.7 2456.79     821 2490.37   944.1 2540.51
#Mann= 5 ,-1 , 0
       0      .1       0   460.9    .045       0   498.6      .1       0
   536.4     .04       0   716.4      .1       0
#XS Ineff= 1 ,-1
  233.03  385.39 2354.25
Permanent Ineff=
       F
Bank Sta=460.9,498.6
XS Rating Curve= 0 ,0
Exp/Cntr=0.3,0.1

Type RM Length L Ch R = 1 ,25668   ,360.7,350,342.6
XS GIS Cut Line= 3
     2146882.333      245202.822     2146448.941      245410.984
     2146038.576      245596.918
#Sta/Elev= 30
       0 2442.45    42.8 2418.99    97.4 2395.38   115.6 2385.55   147.2 2372.77
   177.5 2355.03   197.8 2346.56   257.6 2346.28   296.3 2342.14   330.4  2346.3
   353.7  2347.3   392.2  2346.2   414.1 2342.12   425.1  2344.3   442.2 2345.35
   466.8 2339.73   483.2  2338.8   490.4 2339.84   511.3 2347.85   537.2 2349.71
   576.8 2350.98     670 2349.45   694.8  2350.4   713.7 2353.33   746.8 2368.68
   771.6 2373.63   796.4 2372.04   811.3 2374.33   886.6 2372.64   931.3    2375
#Mann= 6 ,-1 , 0
       0      .1       0     410    .035       0   466.8    .045       0
   490.4    .035       0  640.79     .04       0  820.79      .1       0
Bank Sta=466.8,490.4
XS Rating Curve= 0 ,0
Exp/Cntr=0.3,0.1

Type RM Length L Ch R = 1 ,25318   ,344.8,350,349
XS GIS Cut Line= 3
     2146497.113       244740.53     2146276.269      245133.139
     2145974.541       245507.39
#Sta/Elev= 30
       0 2401.08    65.9 2390.66   124.3 2385.34   174.3  2378.6   256.6 2361.87
   297.4 2354.82   323.6 2351.61   336.9 2347.52   353.9 2345.81   370.4 2345.66
   391.5 2337.41   417.9 2337.22   436.9 2332.79   446.6 2332.23   460.7 2332.74
     470 2336.37     484 2337.23   515.1 2344.22   691.1 2352.53   701.6 2350.62
   722.5 2350.14   748.6  2353.4   817.7 2356.29     827    2359     834 2358.85
     841 2355.95   852.7 2358.24   880.7 2359.74     897 2358.94   931.2 2361.71
#Mann= 7 ,-1 , 0
       0      .1       0   436.9    .045       0   460.7      .1       0
  520.46    .035       0  640.46      .1       0  770.46     .04       0
  900.46      .1       0
Bank Sta=436.9,460.7
XS Rating Curve= 0 ,0
Exp/Cntr=0.3,0.1

Type RM Length L Ch R = 1 ,24968   ,284.1,282.5,277.7
XS GIS Cut Line= 3
     2146293.004      244594.917     2146006.423      244944.117
     2145698.536      245302.088
#Sta/Elev= 30
       0 2387.59    88.6 2361.87      99 2360.16   120.1 2352.63   133.2 2350.06
   213.9 2345.91   248.3 2347.66   269.3 2342.01   298.8 2341.04   315.7  2335.9
   350.9 2336.41   371.9 2333.68   413.4 2332.77   440.3 2328.37   451.6 2327.66
   455.7 2328.29   516.5 2341.34   611.7 2342.43   621.7 2344.48   633.3 2349.69
   650.6 2351.45     662 2358.66   697.8 2375.59   744.3 2401.54   763.1 2415.67
   776.9 2419.53   789.1 2429.28   858.2 2468.38   890.8 2483.13   923.9 2494.78
#Mann= 5 ,-1 , 0
       0      .1       0   440.3    .045       0   455.7      .1       0
  541.74     .04       0  691.74      .1       0
#XS Ineff= 2 , 0
          343.42 2338.11
Permanent Ineff=
       F       F
Bank Sta=440.3,455.7
XS Rating Curve= 0 ,0
Exp/Cntr=0.3,0.1

Type RM Length L Ch R = 1 ,24686   ,345.4,348.1,348.6
XS GIS Cut Line= 2
     2145988.284      244417.304     2145559.518      245202.647
#Sta/Elev= 30
       0 2379.63   102.9 2356.74   127.6 2349.73   155.2 2344.47   218.8 2340.51
   246.1 2336.02   270.3 2336.69   289.6 2328.24   383.3 2330.37     396 2326.13
   400.9 2325.56   419.4 2326.08   465.5 2327.31   487.9 2326.15   495.4 2333.96
     500 2336.44   533.8 2337.56   562.7 2339.96   565.3  2341.1   611.1 2374.73
   667.3 2411.93   698.3 2431.03   707.9 2438.65   719.7 2441.47   732.1 2451.02
   757.1  2463.6   820.6 2500.87   843.3 2512.88   861.7 2521.81   894.8 2533.54
#Mann= 6 ,-1 , 0
       0      .1       0     396    .045       0   419.4      .1       0
     430     .12       0     500     .04       0     540      .1       0
Bank Sta=396,419.4
XS Rating Curve= 0 ,0
Exp/Cntr=0.3,0.1

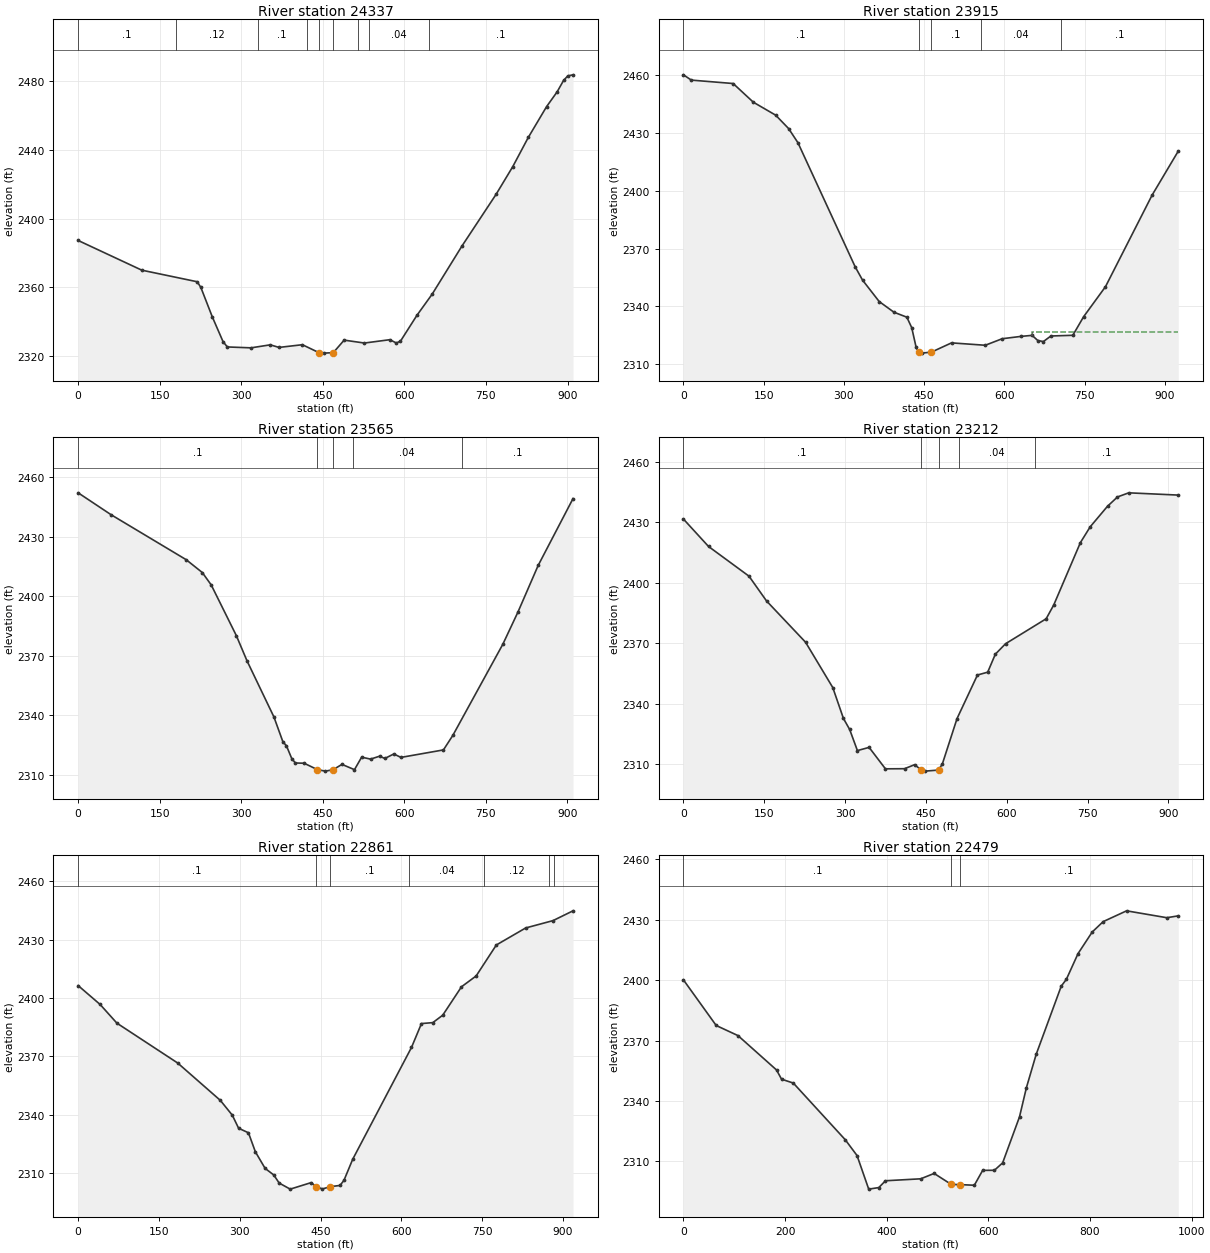
Type RM Length L Ch R = 1 ,24337   ,420.8,422.3,413.7
XS GIS Cut Line= 3
     2145738.613      244250.597     2145484.128      244627.967
     2145238.873      245011.176
#Sta/Elev= 30
       0 2387.31     117 2370.01     219 2363.26   225.7 2359.92   246.7  2342.8
   266.5 2328.35   274.4 2325.27   317.9 2324.75   353.3  2326.5   369.4    2325
   412.4 2326.57   443.1 2321.92   451.9 2321.67   469.2 2321.95   489.2 2329.24
   526.5 2327.55   573.3  2329.5     585  2327.6   592.7  2328.6   623.1 2343.72
   651.2 2356.09   705.7    2384   768.5 2414.13   799.2 2430.27   827.8 2447.32
   861.5  2465.3     881 2473.96   892.7 2480.54   900.5  2483.2   910.1 2483.83
#Mann= 9 ,-1 , 0
       0      .1       0     180     .12       0     330      .1       0
     420     .04       0   443.1    .045       0   469.2     .04       0
  515.16      .1       0  535.16     .04       0  645.16      .1       0
Bank Sta=443.1,469.2
XS Rating Curve= 0 ,0
Exp/Cntr=0.3,0.1

Type RM Length L Ch R = 1 ,23915   ,352.7,350.6,344.5
XS GIS Cut Line= 3
      2145293.26       243966.55     2145150.462      244399.114
     2144985.323      244838.955
#Sta/Elev= 30
       0 2460.18    14.8 2457.44      93 2455.67   130.7 2445.98   172.5 2439.25
   196.7  2432.3   214.1 2424.97     321 2360.67   334.9  2353.7     366 2342.59
   393.6 2337.04   417.8 2334.45   426.9 2329.01   435.1 2318.86   439.8 2316.24
   445.4 2315.81   463.8 2316.34   501.3 2321.13   564.4 2319.89     596 2323.28
   631.2 2324.49     652 2325.03   662.6 2322.36   673.1 2321.81   687.1  2324.7
   728.1 2325.06   748.3  2334.7   789.2 2350.28   876.3 2397.74   925.3 2420.61
#Mann= 5 ,-1 , 0
       0      .1       0   439.8    .045       0   463.8      .1       0
  555.52     .04       0  705.52      .1       0
#XS Ineff= 2 , 0
                          652.44         2326.69
Permanent Ineff=
       F       F
Bank Sta=439.8,463.8
XS Rating Curve= 0 ,0
Exp/Cntr=0.3,0.1

Type RM Length L Ch R = 1 ,23565   ,342.8,352.7,366.2
XS GIS Cut Line= 3
     2144852.001      243893.172     2144808.711      244346.694
     2144774.377      244800.306
#Sta/Elev= 30
       0  2452.1    60.3 2441.11   198.7 2418.39   228.4 2411.91   244.8 2405.66
     291 2380.12   310.7 2367.36   360.2 2339.07   376.6 2326.64   383.3 2324.48
   393.1 2318.03   399.7 2315.86   415.8 2315.73   440.3  2312.5   454.9 2311.75
   468.9 2312.45   485.4 2315.15   508.4 2312.49   521.6 2318.79     538 2317.81
   554.5 2319.27   564.3 2318.15   580.8  2320.4   593.9 2318.67   672.1 2322.45
   689.4 2329.78   781.5  2375.8   809.2 2391.98   846.4 2415.48   910.5 2449.19
#Mann= 5 ,-1 , 0
       0      .1       0   440.3    .045       0   468.9      .1       0
  505.58     .04       0  705.58      .1       0
Bank Sta=440.3,468.9
XS Rating Curve= 0 ,0
Exp/Cntr=0.3,0.1

Type RM Length L Ch R = 1 ,23212   ,343.1,350.6,351.4
XS GIS Cut Line= 3
     2144759.911      243861.716     2144500.448      244243.461
     2144184.043      244572.994
#Sta/Elev= 30
       0 2431.71    46.6 2418.11   121.7 2403.38   154.2 2391.11   226.7 2370.62
   277.2 2348.14     297 2332.81   308.5 2327.38   322.9 2316.89   344.6 2318.49
   374.9 2307.85   410.3 2307.91   429.2 2309.91     441 2307.34   448.5 2306.71
   473.8 2307.24   480.8 2310.48   507.8 2332.77   545.7 2354.37   564.7 2355.78
   578.9  2364.7   597.8 2369.87   673.2 2382.26   687.3 2389.11   736.8 2420.05
     755 2427.88   787.1 2438.06   805.6 2442.67   826.5 2444.71   918.4 2443.59
#Mann= 5 ,-1 , 0
       0      .1       0     441    .045       0   473.8      .1       0
  511.57     .04       0  651.57      .1       0
Bank Sta=441,473.8
XS Rating Curve= 0 ,0
Exp/Cntr=0.3,0.1

Type RM Length L Ch R = 1 ,22861   ,375.3,382,392.4
XS GIS Cut Line= 3
     2144650.411      243741.205     2144267.927      243985.647
     2143947.399       244321.91
#Sta/Elev= 30
       0 2406.37    40.8 2396.66    71.9 2387.07   184.8 2366.57   263.9 2347.38
   286.1 2339.78   297.8 2333.07   316.1 2330.72   328.9 2320.97     347 2312.43
   363.1 2309.04   373.1 2304.89   393.6 2301.77   432.5 2305.12   441.8 2303.03
   453.5 2301.87   467.8 2303.03   486.1 2303.67   493.4 2306.31   509.6 2317.12
   618.7 2374.58   637.2 2386.85   658.3 2387.34   676.7 2391.16   711.5 2405.75
   738.7 2411.32   776.2 2427.24   830.6 2435.98   881.4 2439.76   918.5 2444.79
#Mann= 7 ,-1 , 0
       0      .1       0   441.8    .045       0   467.8      .1       0
  613.92     .04       0  753.92     .12       0  873.92     .04       0
  883.92     .12       0
Bank Sta=441.8,467.8
XS Rating Curve= 0 ,0
Exp/Cntr=0.3,0.1

Type RM Length L Ch R = 1 ,22479   ,310.9,318,326.4
XS GIS Cut Line= 3
     2144611.315      243624.324     2144081.715      243678.928
     2143642.093      243716.868
#Sta/Elev= 30
       0 2400.17    64.5 2377.48   107.4 2372.45   183.2 2355.37   193.1 2350.78
   216.2 2348.87   318.5 2320.67   341.6 2312.84   364.6 2296.14   384.4 2296.91
   397.6  2300.3   466.9 2301.27   493.3 2303.94   527.1 2298.47   543.52298.395
   572.4 2298.07   588.8 2305.46   611.9 2305.51   628.1  2309.2   661.3 2332.07
   674.9  2346.6   694.2 2363.21   743.4 2397.02   753.5 2400.43   776.5 2413.23
   804.4 2423.96   825.9 2429.11     872 2434.48   951.1 2431.06   973.7 2431.98
#Mann= 3 ,-1 , 0
       0      .1       0   527.1    .045       0   543.5      .1       0
Bank Sta=527.1,543.5
XS Rating Curve= 0 ,0
Exp/Cntr=0.3,0.1

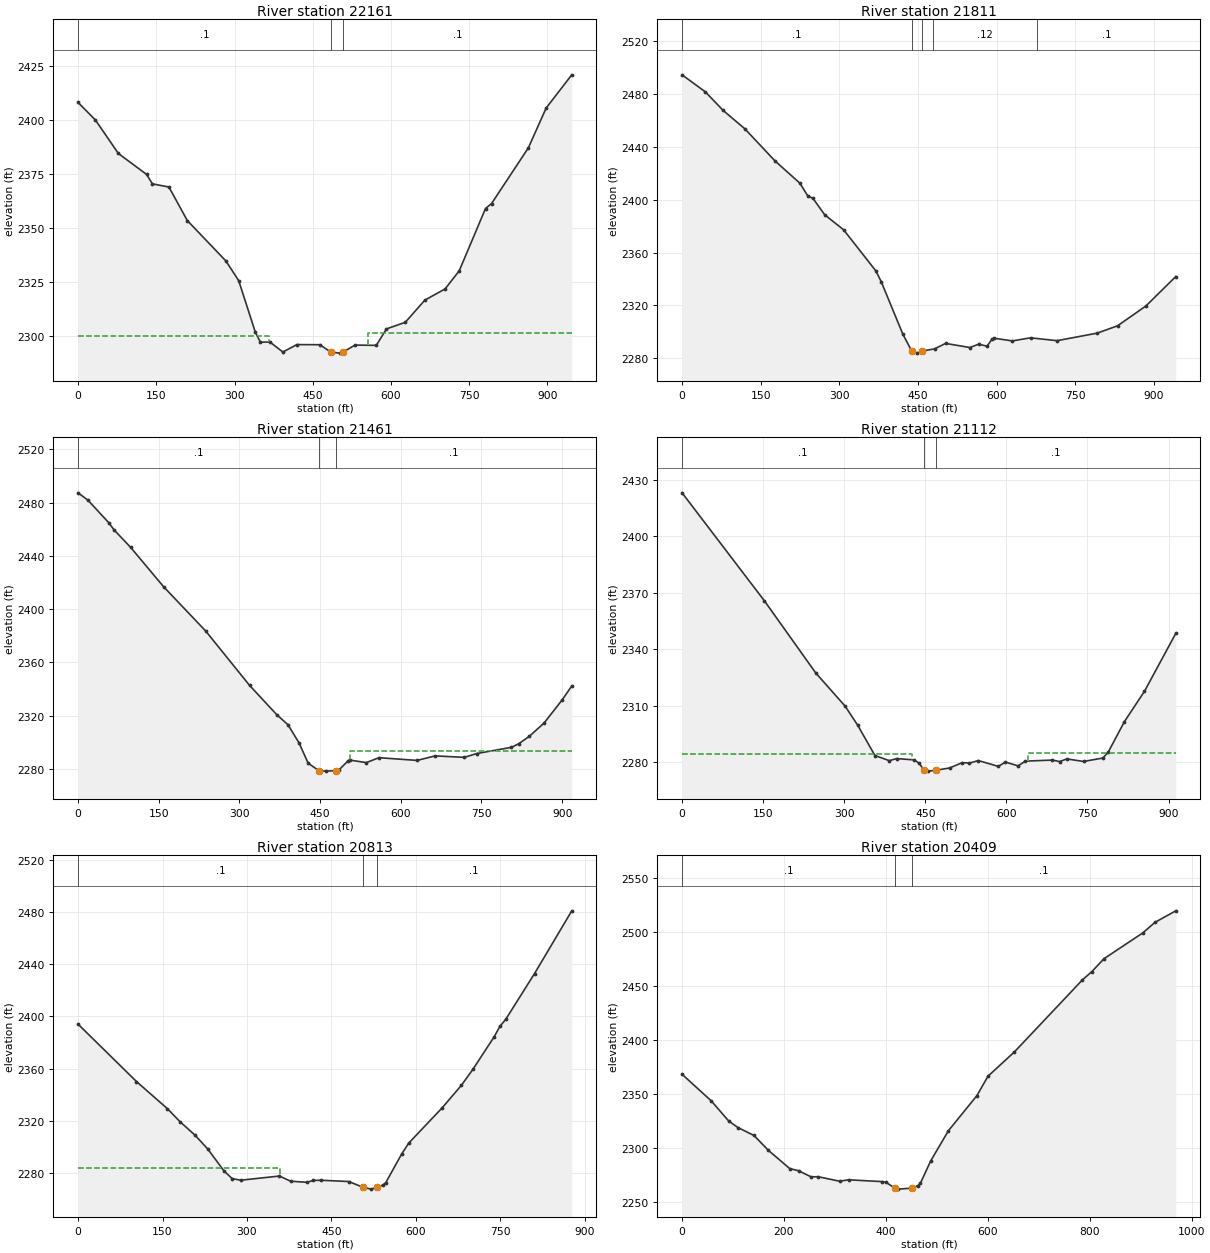
Type RM Length L Ch R = 1 ,22161   ,347.5,350,348.4
XS GIS Cut Line= 3
     2144627.337      243561.344     2144162.056      243379.401
     2143783.845      243141.103
#Sta/Elev= 30
       0 2408.24    33.3 2400.09    77.2 2384.59   131.3 2374.89   142.5 2370.49
   174.2 2369.03   209.4 2353.48   283.4 2334.74     308 2325.58   339.7 2301.79
   349.5 2297.08   367.9 2297.14   392.6  2292.5   419.6 2295.95   463.5 2295.89
   484.2 2292.53   501.3 2291.99   508.5 2292.55   531.1 2295.73   571.8 2295.59
   591.2 2303.21   627.4 2306.29   664.9 2316.58   703.6 2321.75   730.8 2330.17
   781.2 2359.07   792.8 2361.37   863.4 2387.22   897.5 2405.68   946.6 2421.07
#Mann= 3 ,-1 , 0
       0      .1       0   484.2    .045       0   508.5      .1       0
#XS Ineff= 2 , 0
          366.54 2299.72  555.26         2301.25
Permanent Ineff=
       F       F
Bank Sta=484.2,508.5
XS Rating Curve= 0 ,0
Exp/Cntr=0.3,0.1

Type RM Length L Ch R = 1 ,21811   ,349.5,349.8,344.9
XS GIS Cut Line= 3
     2144822.357      243266.046      2144393.65      243135.999
     2143973.691      242875.931
#Sta/Elev= 30
       0 2494.74    44.2 2481.91    78.5 2467.72   119.6 2453.91   177.4 2429.45
   224.8 2412.61   239.6 2403.15   249.9 2401.02   272.2 2388.66   308.2 2377.31
   369.9 2346.08   380.2 2337.79   421.3 2298.15   438.4 2285.25   448.8 2283.81
  458.51 2285.43   481.7 2287.03   502.8 2291.17   549.2 2288.07   565.9 2290.59
   581.8 2289.08   591.3 2294.24   596.1 2295.06   630.2 2293.07   664.9 2295.41
   715.5 2293.25   792.3 2298.98   830.9  2304.5   884.9 2319.48     942 2341.84
#Mann= 5 ,-1 , 0
       0      .1       0   438.4    .045       0  458.51      .1       0
     478     .12       0     678      .1       0
Bank Sta=438.4,458.51
XS Rating Curve= 0 ,0
Exp/Cntr=0.3,0.1

Type RM Length L Ch R = 1 ,21461   ,348.9,349.4,349.7
XS GIS Cut Line= 3
     2144903.693       242917.19     2144455.741      242793.894
     2144014.657       242689.49
#Sta/Elev= 30
       0 2487.27    18.4 2481.73    56.7 2464.98    66.9 2459.42    97.6 2446.38
   158.8 2416.86   237.1 2383.63   318.8 2342.76   369.8  2320.6   390.2 2313.26
   410.9 2299.53   427.7 2284.41   448.22278.599   461.7 2278.41   480.4 2278.76
   485.3  2279.4   502.2 2286.26   505.5  2286.7   535.9  2284.8   559.4  2288.5
   630.3 2286.45     664 2289.84   717.9 2288.75   741.5 2291.62   805.6 2296.27
   819.1  2298.9   839.3 2304.63   866.3 2314.47     900 2331.84   917.9 2342.36
#Mann= 3 ,-1 , 0
       0      .1       0   448.2    .045       0   480.4      .1       0
#XS Ineff= 2 , 0
                          504.64          2293.5
Permanent Ineff=
       F       F
Bank Sta=448.2,480.4
XS Rating Curve= 0 ,0
Exp/Cntr=0.3,0.1

Type RM Length L Ch R = 1 ,21112   ,290.6,298.7,305.1
XS GIS Cut Line= 3
     2145028.627      242594.327     2144585.757      242473.337
     2144138.998      242391.038
#Sta/Elev= 30
       0 2423.08   152.2 2365.74   247.4 2327.33   301.9 2309.65   324.8 2299.64
   356.8 2283.49   383.5 2280.74   396.9 2281.86     429 2281.17   437.9  2279.6
   448.1 2275.66   454.9 2275.19  470.64 2275.69     495 2276.87   518.4  2279.7
   531.7 2279.46   548.3  2280.8   585.1 2277.71   598.4 2279.99   621.8 2277.97
   635.1  2280.5   685.2 2281.07   698.5 2280.28   711.9 2281.68   742.8 2280.33
   778.6 2282.15   788.6 2285.34   818.2 2301.37   855.5  2317.6   913.4 2348.35
#Mann= 3 ,-1 , 0
       0      .1       0   448.1    .045       0  470.64      .1       0
#XS Ineff= 2 , 0
          426.21 2284.32  639.83         2284.93
Permanent Ineff=
       F       F
Bank Sta=448.1,470.64
XS Rating Curve= 0 ,0
Exp/Cntr=0.3,0.1

Type RM Length L Ch R = 1 ,20813   ,393.1,404.8,413.2
XS GIS Cut Line= 3
     2145069.499      242496.605      2144579.48      242129.091
     2144505.102      241875.332
#Sta/Elev= 30
       0 2394.01   103.7 2350.03   158.8 2329.15     181 2319.25     208 2308.75
   229.9  2298.5   259.2 2281.43   273.6 2275.62   288.8 2274.32   357.7 2277.54
   377.5 2273.56   406.9 2272.72   417.7 2274.19   432.2 2274.29   480.7 2273.33
  505.84 2268.96   520.8 2267.49   530.2 2268.78   541.9 2270.62   546.6  2272.5
   574.7 2294.34   587.3 2302.75   646.6 2329.77     681 2347.17   701.5 2359.47
   739.1 2384.32   749.3 2392.29   759.6 2397.67   810.9 2432.87     877 2480.96
#Mann= 3 ,-1 , 0
       0      .1       0  505.84    .045       0   530.2      .1       0
#XS Ineff= 2 , 0
           358.1 2283.78
Permanent Ineff=
       F       F
Bank Sta=505.84,530.2
XS Rating Curve= 0 ,0
Exp/Cntr=0.3,0.1

Type RM Length L Ch R = 1 ,20409   ,614.6,589.1,564.2
XS GIS Cut Line= 3
     2145170.128       242428.79     2144988.558      241938.772
     2144564.167      241800.954
#Sta/Elev= 30
       0 2368.42    57.3  2343.8    91.6 2325.17   109.8  2319.1   141.1 2311.84
   169.1 2298.19   211.2 2281.25   228.7 2279.18   253.2 2273.55   267.2 2273.67
   309.2 2269.51   326.7 2270.84   393.2 2269.12   400.2 2268.51   417.6 2263.13
   424.4  2262.2   452.1 2263.16   463.1 2265.51   467.8 2267.76   488.2 2288.54
   522.7 2316.21   578.7 2348.73   600.3  2366.6   652.1 2389.05   785.8 2455.77
   803.9 2463.22     828  2475.3   904.2 2499.16     928 2508.88   968.8 2519.57
#Mann= 3 ,-1 , 0
       0      .1       0   417.6    .045       0   452.1      .1       0
Bank Sta=417.6,452.1
XS Rating Curve= 0 ,0
Exp/Cntr=0.3,0.1

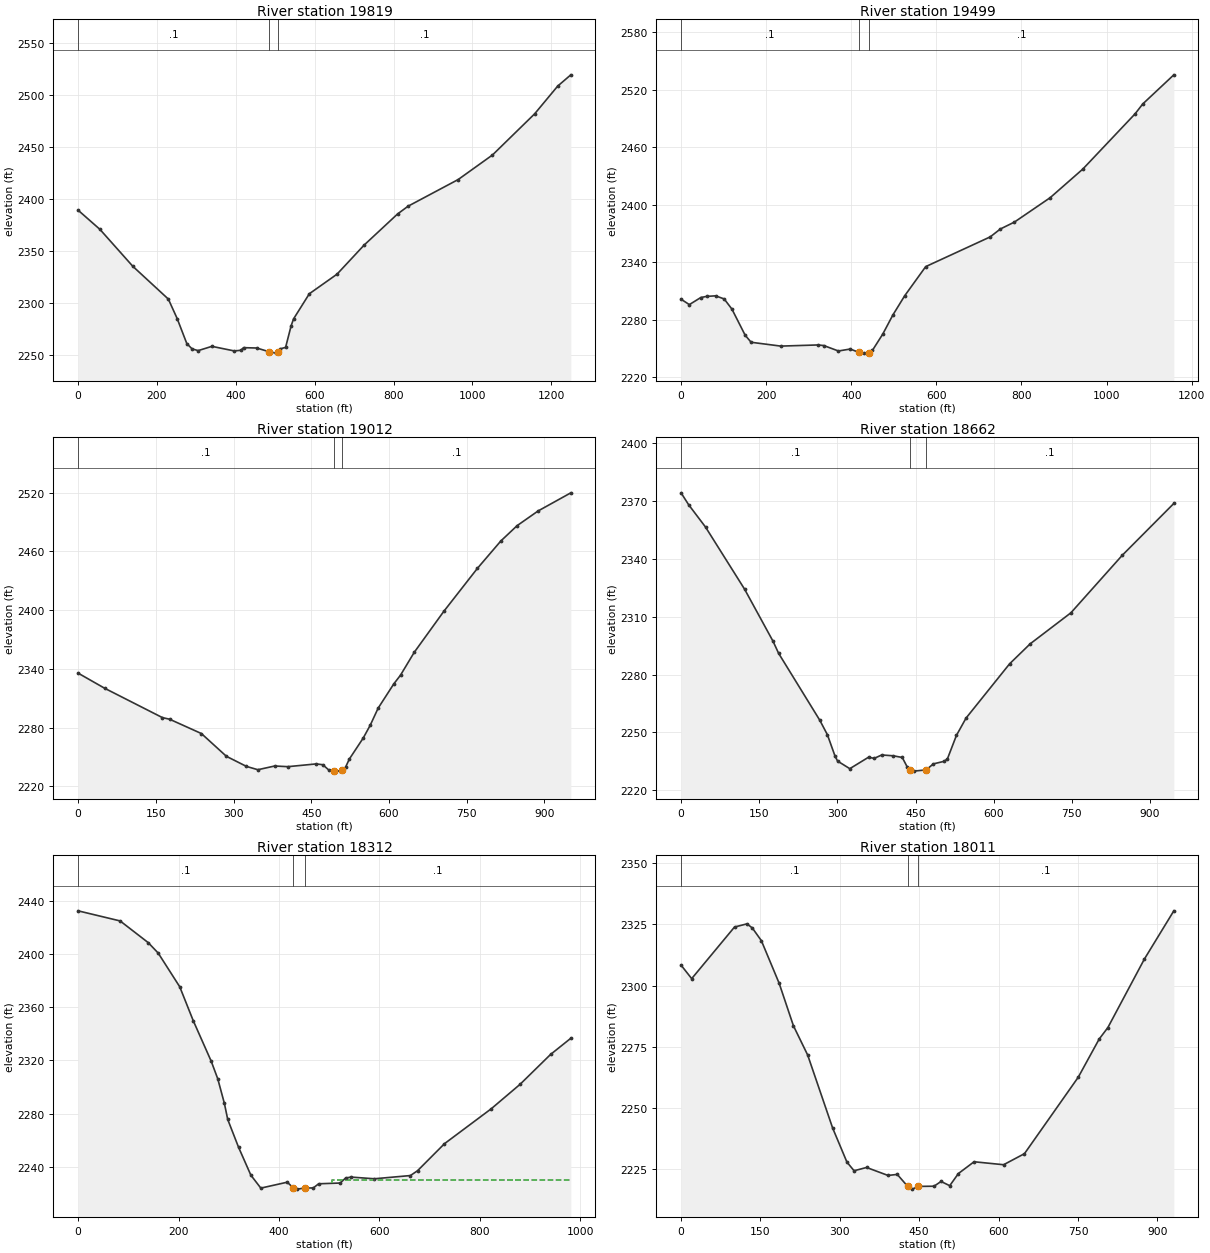
Type RM Length L Ch R = 1 ,19819   ,340.3,320.8,307.5
XS GIS Cut Line= 2
     2145808.902      241551.569     2144581.668      241785.641
#Sta/Elev= 30
       0 2389.16    55.4 2370.67   138.9 2335.04   228.9 2303.49   251.3 2284.71
   275.8 2260.58   289.2 2255.49   304.6 2253.84   339.3 2257.95   396.1 2253.53
   412.8 2254.17   419.6 2256.68   452.8 2256.36   485.2 2252.67   502.9 2251.42
   506.3 2252.78     513 2255.61   526.2 2256.93   540.2 2277.74   546.4 2284.41
   586.4 2308.63   656.6 2327.48   725.3 2355.51   810.2 2385.51   836.9    2393
   963.8 2418.66  1050.7  2442.3  1157.6 2481.94  1216.2 2508.72  1249.4 2519.53
#Mann= 3 ,-1 , 0
       0      .1       0   485.2    .045       0   506.3      .1       0
Bank Sta=485.2,506.3
XS Rating Curve= 0 ,0
Exp/Cntr=0.3,0.1

Type RM Length L Ch R = 1 ,19499   ,479.4,486.6,491.5
XS GIS Cut Line= 3
     2145233.568      241074.676     2145043.248      241617.197
     2144472.288      241735.326
#Sta/Elev= 30
       0 2301.27    19.5 2295.63    46.5 2303.05    60.4 2304.23    81.2 2304.78
   101.3 2301.56   119.5 2290.97   150.7 2263.63   164.7 2256.31   234.2 2252.31
   321.1  2253.5   335.1 2252.91   369.8 2247.21   397.6 2249.24   418.5 2245.67
   428.9 2244.97   442.8 2245.61   449.8 2247.91   474.1 2264.91   497.7 2284.75
   525.6 2304.89   574.9 2335.29   726.4 2366.31   750.4 2374.59   783.4 2381.79
   867.3 2407.23   944.2 2437.17  1066.9  2494.8  1084.9  2505.1    1158 2535.54
#Mann= 3 ,-1 , 0
       0      .1       0   418.5    .045       0   442.8      .1       0
Bank Sta=418.5,442.8
XS Rating Curve= 0 ,0
Exp/Cntr=0.3,0.1

Type RM Length L Ch R = 1 ,19012   ,344.5,350,343.7
XS GIS Cut Line= 3
     2145002.143      240954.884     2144639.584       241305.72
     2144314.055        241611.2
#Sta/Elev= 30
       0 2335.75    51.3 2320.28   162.9 2290.26   176.6 2288.66     238 2274.01
   286.2 2250.78     325 2240.43     347 2237.06   379.5 2240.86   404.9 2240.18
   459.7    2243   472.3 2242.15   483.9 2236.72   494.72236.243   504.8 2235.62
   509.4  2236.3   516.4 2239.85   523.4  2247.9   550.3 2269.43   563.8 2282.51
   579.1 2299.98   609.2 2324.67   622.3 2333.71   648.7 2356.97   705.6 2398.71
   770.7 2442.81   815.8  2470.7   847.2 2486.36   887.8  2501.4   950.9  2519.9
#Mann= 3 ,-1 , 0
       0      .1       0   494.7    .045       0   509.4      .1       0
Bank Sta=494.7,509.4
XS Rating Curve= 0 ,0
Exp/Cntr=0.3,0.1

Type RM Length L Ch R = 1 ,18662   ,365.7,350,341.9
XS GIS Cut Line= 3
       2144921.4      240800.162     2144513.308      240983.386
     2144137.215      241310.471
#Sta/Elev= 30
       0 2374.11    14.6 2367.93      47 2356.37   121.9 2324.23   176.5 2297.27
   187.3 2290.97   266.4 2256.29   280.9 2248.83   295.6 2237.72   300.4  2235.2
   323.9 2231.26   359.9  2237.2   370.7 2236.59   385.1 2238.36   407.3 2237.93
   424.6 2237.06   434.6 2231.87     439 2230.67   446.2 2229.99   470.3 2230.62
   484.3 2233.74   505.2 2235.09   511.2 2236.31   528.6 2248.52     547 2257.46
   630.6 2285.56   670.3 2295.96   748.3 2311.99     847 2341.82   945.8 2368.61
#Mann= 3 ,-1 , 0
       0      .1       0     439    .045       0   470.3      .1       0
Bank Sta=439,470.3
XS Rating Curve= 0 ,0
Exp/Cntr=0.3,0.1

Type RM Length L Ch R = 1 ,18312   ,305.3,300.6,290.3
XS GIS Cut Line= 3
     2144325.662      240316.555     2144284.823      240754.517
     2144068.364      241250.739
#Sta/Elev= 30
       0 2432.29    83.8  2424.7   139.8 2408.39   159.6 2400.57   202.5 2375.26
   229.3 2349.89   265.1 2319.45   278.2 2306.19   291.4 2287.73     298 2275.73
   319.6 2254.83   344.1  2233.9   363.9 2224.19   416.6 2228.64   428.6 2224.35
   436.4 2223.43   452.3 2224.27   468.3 2224.32   479.1 2227.44     522 2228.01
   532.7 2231.76   543.5 2232.47     590  2231.2   661.8 2233.62   675.9 2237.22
   729.6 2257.53   822.7 2283.73     880 2302.05   940.8 2324.49   981.2 2336.67
#Mann= 3 ,-1 , 0
       0      .1       0   428.6    .045       0   452.3      .1       0
#XS Ineff= 2 , 0
                          506.23         2230.26
Permanent Ineff=
       F       F
Bank Sta=428.6,452.3
XS Rating Curve= 0 ,0
Exp/Cntr=0.3,0.1

Type RM Length L Ch R = 1 ,18011   ,395.3,406.6,408.9
XS GIS Cut Line= 3
     2143901.828      240321.433     2144007.064      240765.806
     2144025.254      241239.776
#Sta/Elev= 30
       0 2308.33    20.1 2302.82     101 2323.86   124.6 2325.16   134.7 2323.46
   151.7 2318.32   185.3 2300.96   212.3  2283.6   239.2 2271.68   286.4  2241.9
   313.4 2228.01   326.9 2224.48   350.5 2225.82     391 2222.57   408.5 2222.99
     428 2218.15     437 2216.99   448.3  2218.1     478 2218.18   491.2 2220.12
   507.6 2218.39     524 2223.35   553.6 2228.15   609.4 2226.94   648.8 2231.45
   750.5 2262.65   789.9 2278.17   806.4 2282.88   875.3 2310.78     931 2330.47
#Mann= 3 ,-1 , 0
       0      .1       0     428    .045       0   448.3      .1       0
Bank Sta=428,448.3
XS Rating Curve= 0 ,0
Exp/Cntr=0.3,0.1