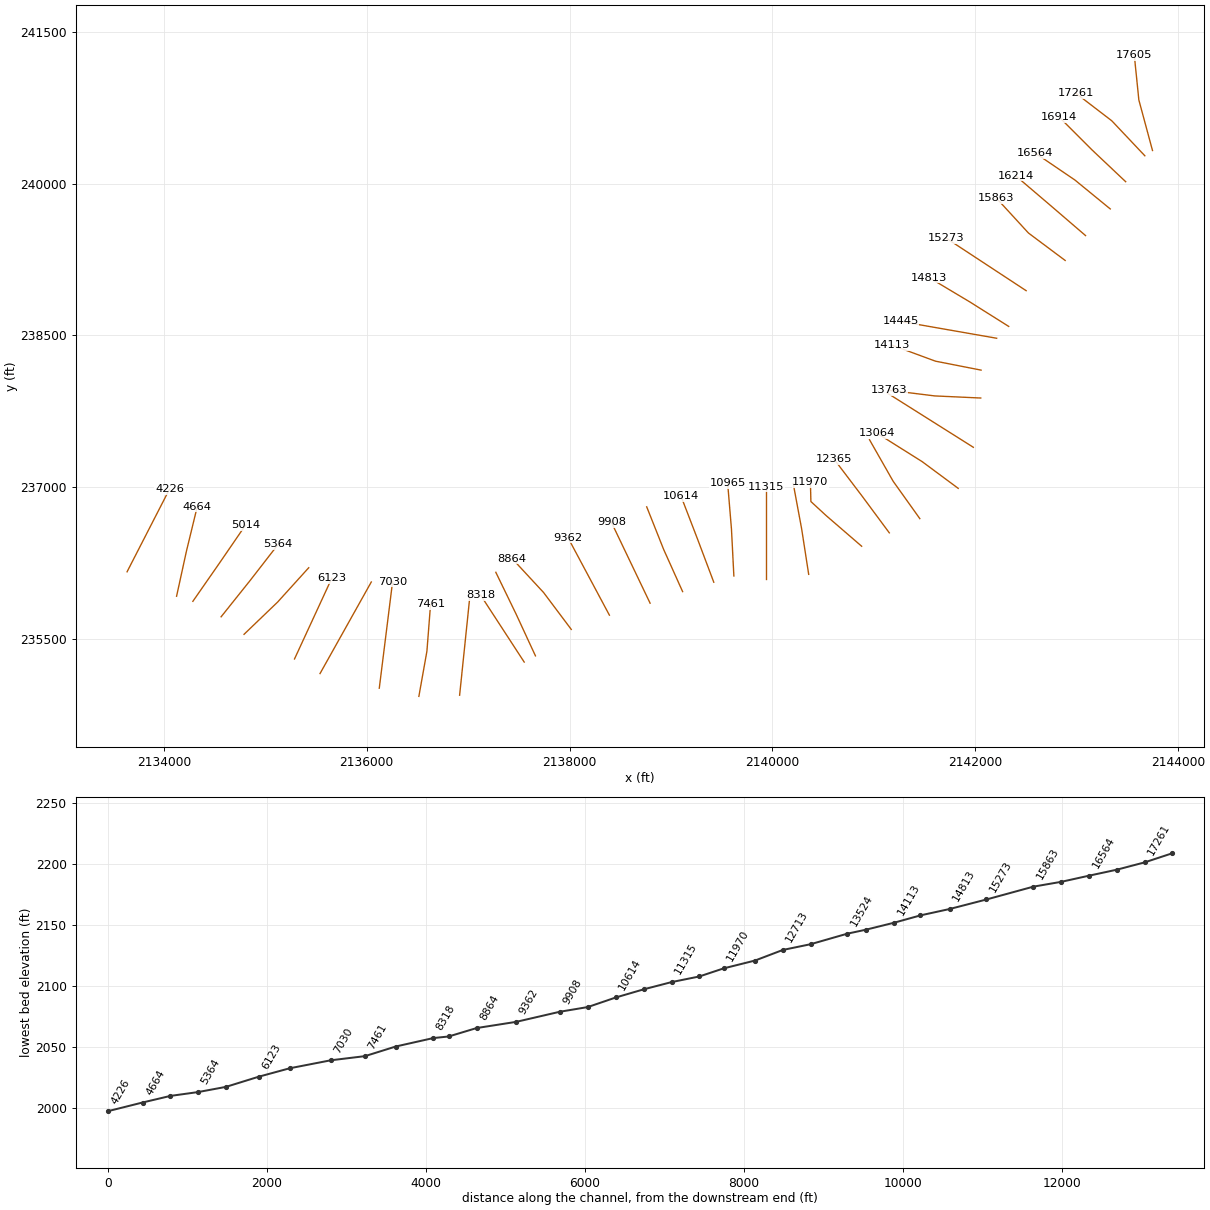
HEC-RAS study LAURELCK3.prj: LAURELCK3

--- LAURELCK3.g01 (geometry) --- (continued)

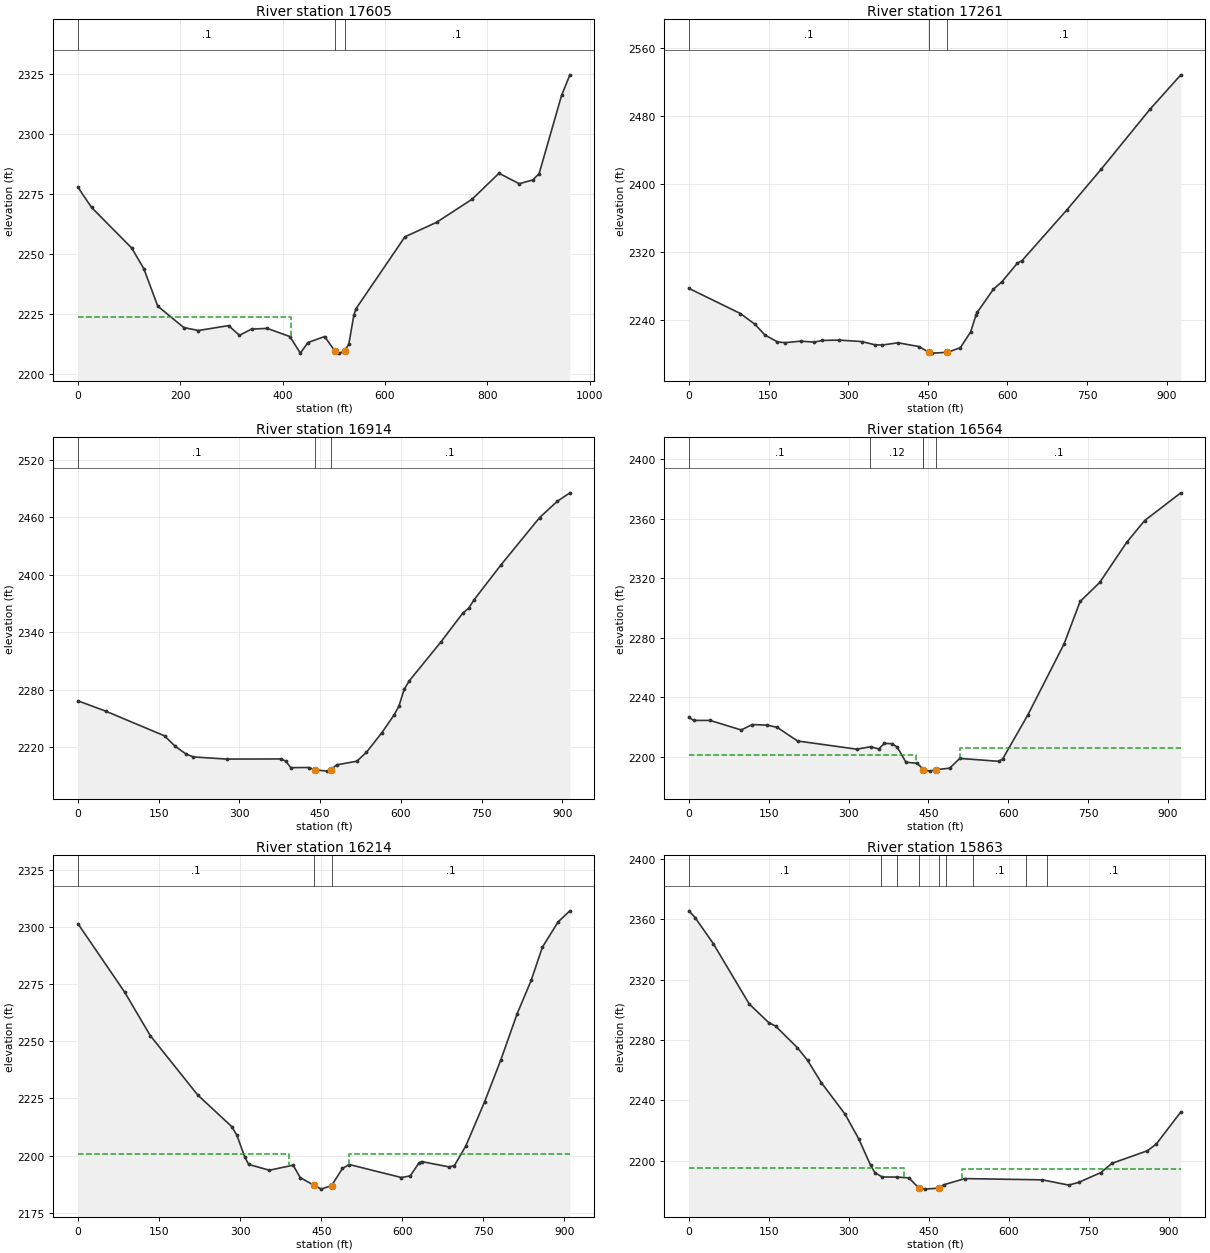
Type RM Length L Ch R = 1 ,17605   ,332.9,343.8,352.4
XS GIS Cut Line= 3
2143746.69934243240328.2504474762143612.14934243240828.066447476
2143567.35734243241269.606447476
#Sta/Elev= 30
       0 2277.82    26.5 2269.43   104.9 2252.51   128.7 2243.84   155.9 2228.21
   206.8 2219.27   235.3 2218.04   294.2 2220.08   315.6 2216.03   339.3 2218.64
   369.9 2218.92   414.1 2215.51   434.5 2208.61   449.5 2213.02     482 2215.52
   502.4 2209.39   510.7 2208.59   520.92209.454   529.3 2212.39   539.2 2224.49
   543.2 2227.12     639 2257.18   700.7 2263.22     770 2272.84   822.8 2283.73
   862.3 2279.35   888.7 2280.92   901.2 2283.54   945.2  2316.3   961.4 2324.84
#Mann= 3 ,-1 , 0
       0      .1       0   502.4    .045       0   520.9      .1       0
#XS Ineff= 2 , 0
          415.79 2223.66
Permanent Ineff=
       F       F
Bank Sta=502.4,520.9
XS Rating Curve= 0 ,0
Exp/Cntr=0.3,0.1

Type RM Length L Ch R = 1 ,17261   ,346.6,347.1,347
XS GIS Cut Line= 3
     2143671.134      240276.196     2143345.441      240622.087
     2142987.609      240897.344
#Sta/Elev= 30
       0 2277.28    96.9 2247.78   124.4  2235.1     143 2222.59   166.5 2214.52
   180.4 2213.49   210.6 2215.29   236.1 2214.18   251.2 2216.11   282.7 2216.53
   325.4 2214.84   350.3 2211.01   363.7 2210.72   393.9 2213.38   433.4 2208.92
     452 2202.15   458.5 2201.23   486.9 2202.16   511.2  2207.6   530.6 2226.11
   540.7 2245.93     543 2249.11   573.4 2276.27   589.8 2285.22   618.8 2307.11
   627.5 2309.97   711.5 2369.25     777  2417.7   868.2 2487.56   926.5 2528.18
#Mann= 3 ,-1 , 0
       0      .1       0     452    .045       0   486.9      .1       0
Bank Sta=452,486.9
XS Rating Curve= 0 ,0
Exp/Cntr=0.3,0.1

Type RM Length L Ch R = 1 ,16914   ,346.8,350,352.7
XS GIS Cut Line= 3
     2143482.184      240019.814     2143150.484      240334.114
     2142827.717      240657.996
#Sta/Elev= 30
       0 2268.54    51.7 2257.78   160.8 2232.05   180.7 2221.11   200.2 2213.35
   214.2  2210.1   276.1 2207.84   376.9 2207.99     386 2205.75   395.4 2198.91
   428.8 2199.06   440.2 2196.68     463 2195.28   469.4 2196.54   480.5 2201.79
   518.2 2205.62   536.1  2214.9   564.6  2235.3   587.1 2253.52   596.3 2262.93
   606.3 2280.73   615.6 2289.34   675.1 2330.41   715.4 2360.18     726 2365.05
   736.2 2373.97   786.2 2410.38     858 2459.66   890.6  2476.5   914.2 2485.41
#Mann= 3 ,-1 , 0
       0      .1       0   440.2    .045       0   469.4      .1       0
Bank Sta=440.2,469.4
XS Rating Curve= 0 ,0
Exp/Cntr=0.3,0.1

Type RM Length L Ch R = 1 ,16564   ,350,350,348.1
XS GIS Cut Line= 3
     2143330.141       239750.48     2142981.028       240036.99
     2142590.557      240303.157
#Sta/Elev= 30
       0 2226.59     8.7 2224.44    39.7 2224.45    98.2 2218.04     119 2221.67
   146.9 2221.29   165.8  2219.8     204 2210.64   315.4 2205.12   341.2 2206.76
   356.8 2205.33   367.1 2209.05   382.2 2208.78   391.7 2206.32   407.7  2196.4
     429 2195.62   440.7 2191.44   452.3 2190.38   464.1 2191.33   489.9 2192.38
     509 2198.92   582.2 2196.97   589.3  2198.5   636.5 2227.96     705 2275.98
     735 2304.37   771.8 2317.12   822.4 2344.03   856.1 2358.66   924.2 2377.34
#Mann= 5 ,-1 , 0
       0      .1       0     340     .12       0     440      .1       0
   440.7    .045       0   464.1      .1       0
#XS Ineff= 2 , 0
          427.24  2201.1  508.77         2206.17
Permanent Ineff=
       F       F
Bank Sta=440.7,464.1
XS Rating Curve= 0 ,0
Exp/Cntr=0.3,0.1

Type RM Length L Ch R = 1 ,16214   ,349,350.6,348
XS GIS Cut Line= 3
     2143086.769      239486.827     2142742.147      239783.912
     2142396.246      240079.517
#Sta/Elev= 30
       0  2301.4    86.1 2271.58   133.7 2252.48   221.5 2226.51   284.3 2212.73
     294 2208.88   308.2 2199.54   315.7 2196.14   354.1 2193.61     398 2195.82
     411  2190.4     437 2186.95   449.9 2185.34   469.1 2186.91   489.3 2194.39
   501.8 2196.11   598.4 2190.41   614.7 2191.16   630.7 2196.78   635.5 2197.41
   686.2 2195.07   696.3 2195.64   717.5 2204.25   752.1  2223.5   782.3 2241.92
   812.4 2262.08   838.4 2276.66     859 2291.12   888.2 2302.25     910 2307.07
#Mann= 3 ,-1 , 0
       0      .1       0     437    .045       0   469.1      .1       0
#XS Ineff= 2 , 0
          390.09 2200.57  501.55         2200.81
Permanent Ineff=
       F       F
Bank Sta=437,469.1
XS Rating Curve= 0 ,0
Exp/Cntr=0.3,0.1

Type RM Length L Ch R = 1 ,15863   ,586.1,590,591.6
XS GIS Cut Line= 3
     2142885.746      239240.808     2142523.866      239512.217
     2142206.438      239858.852
#Sta/Elev= 30
       0 2365.42    11.6 2360.95    45.6 2343.77   113.2 2303.76   150.1 2291.34
   162.4 2289.25   203.4 2274.92   222.5 2266.55   248.2 2251.83   292.8 2230.97
   318.6 2214.47   340.8 2197.09     349 2192.16   362.7  2189.4     390 2189.37
   412.6 2188.81     431 2182.16     431 2182.14   442.8 2181.39   468.4 2182.05
   477.7 2184.24   517.3 2188.36   662.7 2187.53   712.2 2184.06   730.9 2185.86
   772.6 2192.36   793.1 2198.43   859.9 2206.79   876.5 2211.25   922.4 2232.45
#Mann= 9 ,-1 , 0
       0      .1       0     360     .12       0     390      .1       0
     431    .045       0   468.4      .1       0  482.35     .12       0
  532.35      .1       0  632.35     .12       0  672.35      .1       0
#XS Ineff= 2 , 0
          402.48 2195.19  511.87         2194.76
Permanent Ineff=
       F       F
Bank Sta=431,468.4
XS Rating Curve= 0 ,0
Exp/Cntr=0.3,0.1

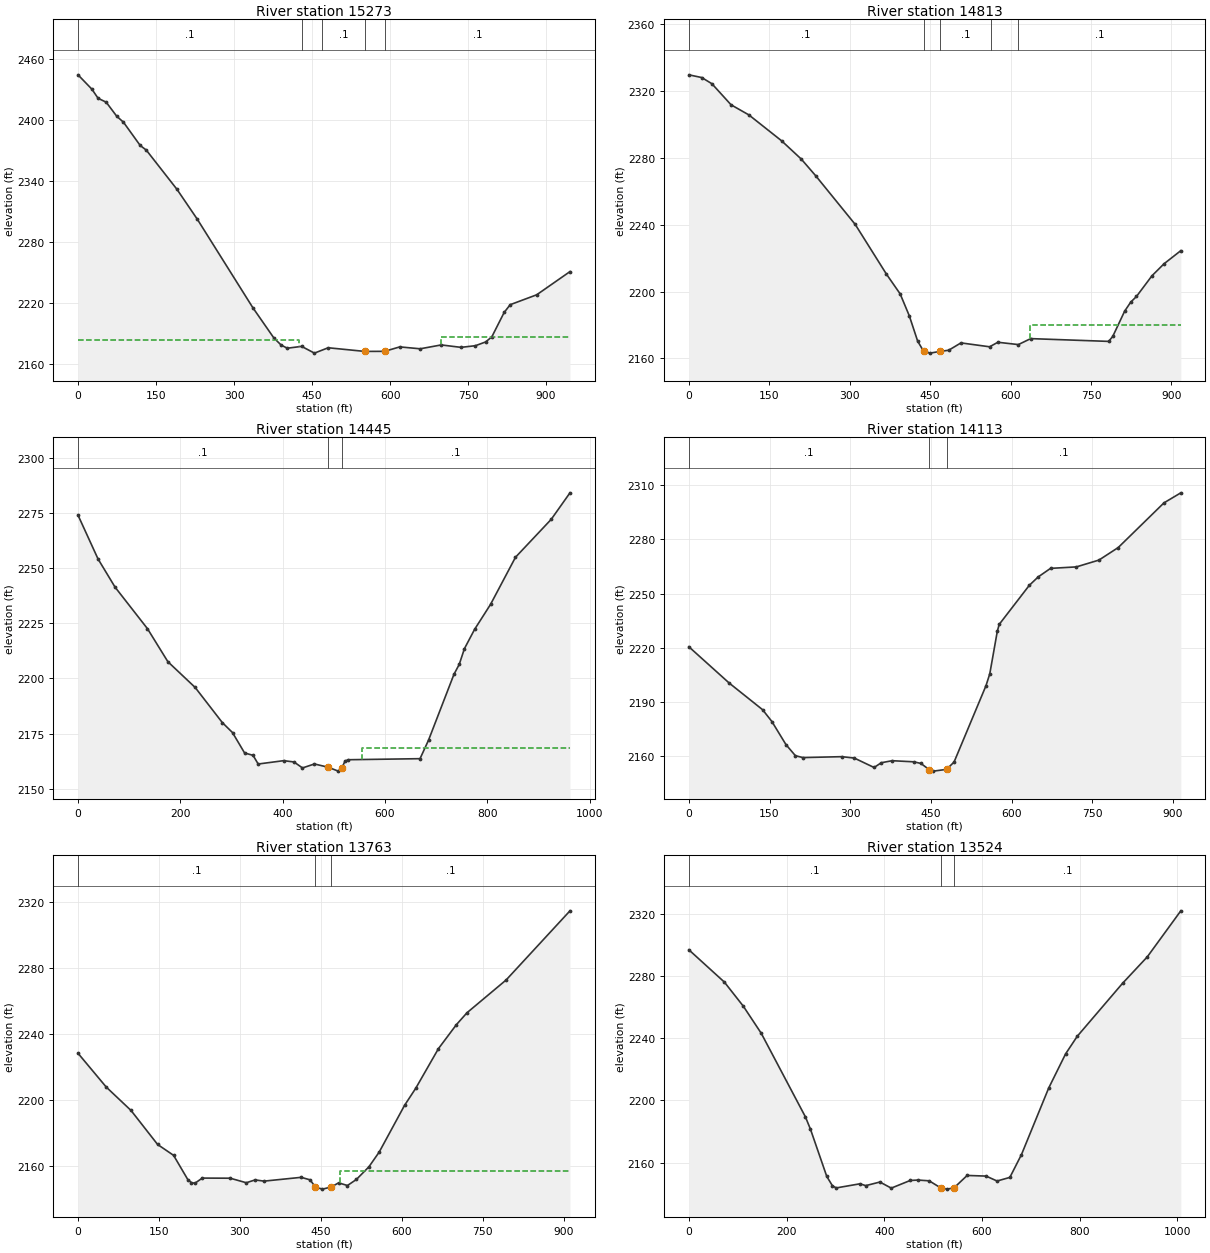
Type RM Length L Ch R = 1 ,15273   ,457.2,460.3,460.5
XS GIS Cut Line= 2
     2142501.275      238941.781     2141711.558      239462.426
#Sta/Elev= 30
       0 2444.13    26.7 2430.03    38.6  2421.1    54.2 2417.26    74.4  2403.5
    87.4 2397.61   119.5  2374.8   131.3 2370.21   190.3 2331.68   229.6 2302.17
     336 2215.61   376.3 2185.97   390.5 2178.82   402.4 2175.72     430 2177.51
   454.5 2170.89   481.1 2176.16   551.2 2172.58   589.4 2172.64   618.6 2177.01
   657.9 2175.15   698.4 2178.94   736.3 2176.56     764 2178.17   783.7 2181.86
   795.6 2186.85   819.4 2210.88     831 2218.45   881.9 2228.16   945.9 2250.94
#Mann= 5 ,-1 , 0
       0      .1       0     430     .12       0     470      .1       0
   551.2    .045       0   589.4      .1       0
#XS Ineff= 2 , 0
          425.18 2183.45  698.66         2186.99
Permanent Ineff=
       F       F
Bank Sta=551.2,589.4
XS Rating Curve= 0 ,0
Exp/Cntr=0.3,0.1

Type RM Length L Ch R = 1 ,14813   ,357.8,368.3,371.2
XS GIS Cut Line= 3
     2142329.143      238588.598     2141945.796      238830.716
     2141547.832      239069.383
#Sta/Elev= 30
       0 2329.62      24    2328      43 2324.29    78.7 2311.69     112 2305.63
   172.8 2290.19   209.7  2279.2   236.5 2269.26   310.2 2240.15   368.4 2210.42
     394  2198.6   411.1 2185.45   426.7 2170.28   437.8 2164.25   449.7 2163.14
   468.8  2164.2   484.4 2164.85   507.4 2169.26   560.9 2166.93   576.2 2169.64
   614.5 2168.25   637.4 2171.82   782.8 2170.16   790.5 2173.14   812.7 2188.27
     824 2193.65   834.7 2197.03   863.7 2209.45   886.1 2216.59   917.4 2224.44
#Mann= 5 ,-1 , 0
       0      .1       0   437.8    .045       0   468.8      .1       0
   563.4     .12       0   613.4      .1       0
#XS Ineff= 2 , 0
                          636.51         2180.25
Permanent Ineff=
       F       F
Bank Sta=437.8,468.8
XS Rating Curve= 0 ,0
Exp/Cntr=0.3,0.1

Type RM Length L Ch R = 1 ,14445   ,333.1,331.7,328.8
XS GIS Cut Line= 2
     2142210.327      238471.451     2141263.103      238637.707
#Sta/Elev= 30
       0 2274.22    39.1 2254.34    72.4 2241.52   135.7 2222.66   175.7 2207.62
     229 2195.93   282.1 2179.96     302 2175.42   325.6 2166.16   342.2 2165.07
   352.2 2161.13   402.2 2162.66   422.2 2162.06   438.8 2159.35   462.1 2161.15
   488.8 2159.69   508.7  2157.9   515.4 2159.21   522.1 2162.52   528.7 2163.08
   668.6 2163.56   685.3 2172.03   734.9 2201.89   745.3 2206.45   755.3 2213.53
   775.2 2222.31   806.4 2233.67   855.2  2255.1   925.1 2272.35   961.7 2284.38
#Mann= 3 ,-1 , 0
       0      .1       0   488.8    .045       0   515.4      .1       0
#XS Ineff= 2 , 0
                          554.18         2168.38
Permanent Ineff=
       F       F
Bank Sta=488.8,515.4
XS Rating Curve= 0 ,0
Exp/Cntr=0.3,0.1

Type RM Length L Ch R = 1 ,14113   ,347.1,350,355.9
XS GIS Cut Line= 3
     2142057.008      238156.186     2141606.875      238244.845
     2141179.267      238403.012
#Sta/Elev= 30
       0 2220.62    75.2 2200.52   137.1 2185.84   154.4  2179.3   180.6 2166.54
   198.1 2160.43   212.1 2159.38   284.2 2159.89   307.6 2159.12   344.4 2153.91
   357.8 2156.53   377.9 2157.66     418 2157.05   431.4 2156.16   446.8 2152.74
   454.8  2151.9   479.1 2152.87   493.1 2156.92   552.5 2199.14   559.5 2205.67
   573.5 2229.16     577 2232.97     633 2254.57   649.5 2259.21   672.5 2263.94
   720.4 2264.75   762.4 2268.51   798.3 2275.44   883.4 2300.14   914.7 2305.68
#Mann= 3 ,-1 , 0
       0      .1       0   446.8    .045       0   479.1      .1       0
Bank Sta=446.8,479.1
XS Rating Curve= 0 ,0
Exp/Cntr=0.3,0.1

Type RM Length L Ch R = 1 ,13763   ,248.7,239.4,230.2
XS GIS Cut Line= 3
     2142053.502      237880.238     2141599.329      237901.119
     2141145.867      237957.595
#Sta/Elev= 30
       0 2228.34    52.3 2207.92    98.3 2193.76   147.5 2173.23   177.1 2166.66
   203.4 2152.05     210 2150.21   216.5 2149.78   230.3 2152.92     282 2152.85
   311.8 2150.11   328.2 2151.82   344.6 2151.08   413.6 2153.38   430.1 2151.85
   439.9 2147.47     453 2146.25   469.5 2147.56   482.8 2150.04   499.3 2148.44
   515.8 2152.08     539 2159.72   558.1 2168.65   605.1 2196.88   625.7 2207.14
   667.9 2231.15     701 2245.57   720.8 2252.83   793.3 2272.63   911.6 2314.41
#Mann= 3 ,-1 , 0
       0      .1       0   439.9    .045       0   469.5      .1       0
#XS Ineff= 2 , 0
                          486.07         2157.03
Permanent Ineff=
       F       F
Bank Sta=439.9,469.5
XS Rating Curve= 0 ,0
Exp/Cntr=0.3,0.1

Type RM Length L Ch R = 1 ,13524   ,459.9,460,456.1
XS GIS Cut Line= 2
      2141980.63      237392.972      2141129.66      237931.118
#Sta/Elev= 30
       0 2296.72    72.7 2275.96   111.5 2260.46   148.1 2243.09   238.5 2189.38
   248.9 2181.41   282.3 2151.05   293.9 2145.05   301.7 2143.69   350.2 2146.33
   362.1 2145.16     391 2147.47   414.3 2143.56   453.1 2148.48   469.1 2148.74
   491.9 2148.25   515.2 2143.76   528.6 2142.91   542.8 2143.76   569.6  2151.7
   608.4 2151.29   630.8 2148.12     657 2150.45   680.8 2165.14   736.5 2207.89
   771.1 2229.84   794.9 2241.12   887.6 2275.16   938.3 2292.19  1006.9 2321.76
#Mann= 3 ,-1 , 0
       0      .1       0   515.2    .045       0   542.8      .1       0
Bank Sta=515.2,542.8
XS Rating Curve= 0 ,0
Exp/Cntr=0.3,0.1

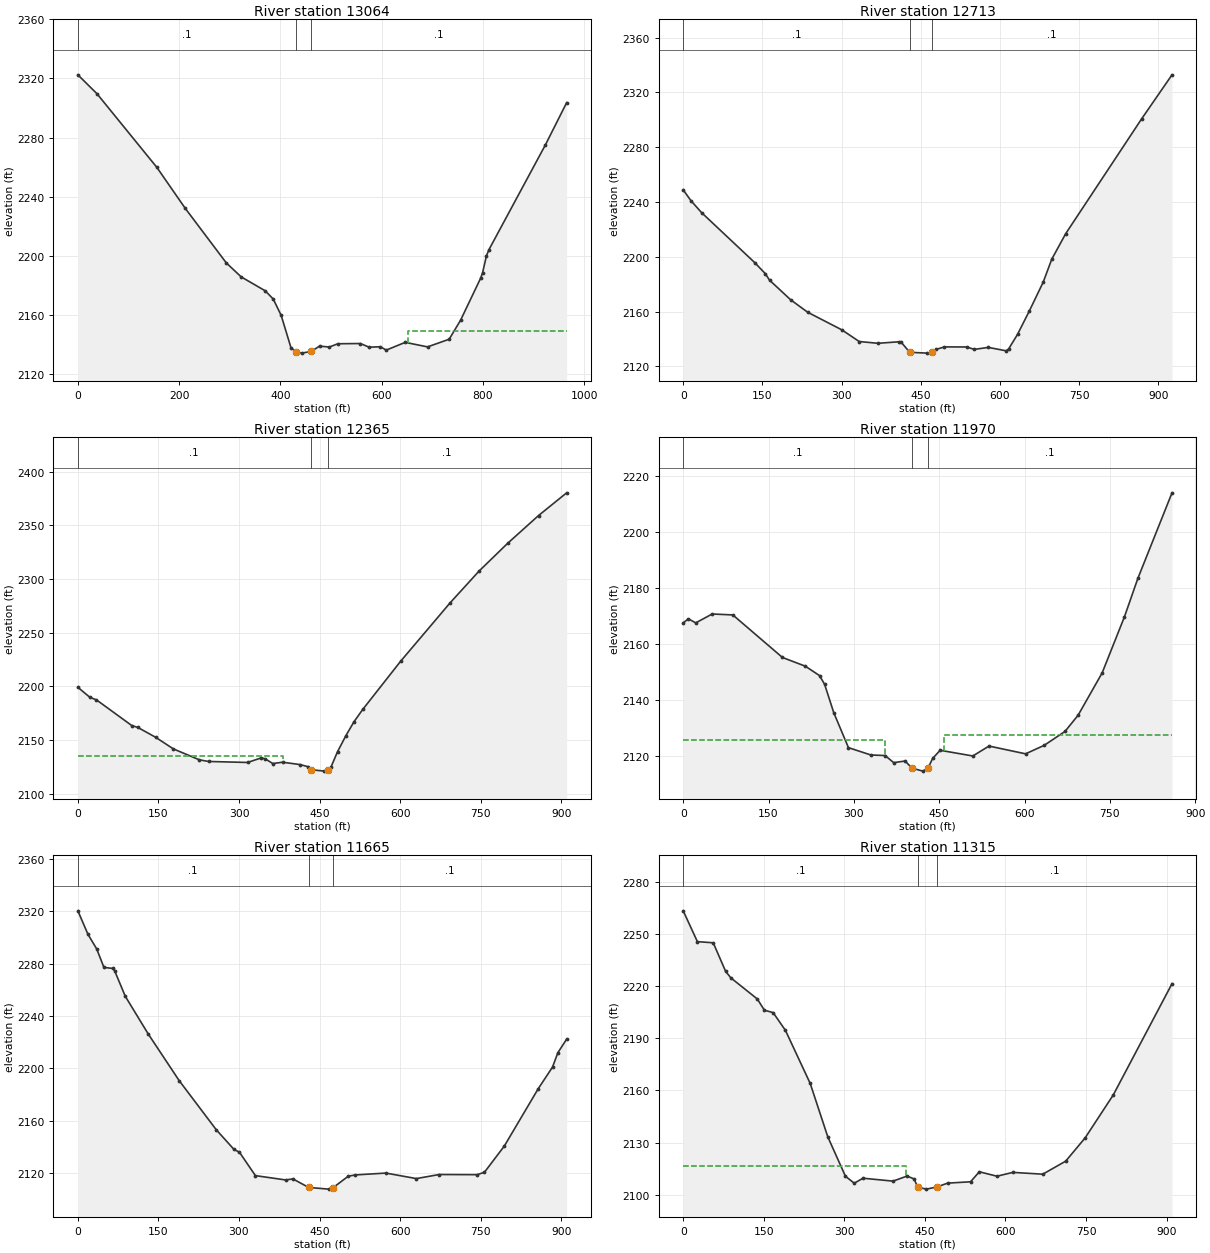
Type RM Length L Ch R = 1 ,13064   ,355.1,350.4,338.8
XS GIS Cut Line= 3
     2141831.382      236986.903      2141475.83      237251.292
     2141033.885      237530.124
#Sta/Elev= 30
       0 2322.44    37.7 2309.69   156.1 2259.86   212.3 2232.11   293.2 2195.33
   322.5 2185.89   370.2 2176.42   385.9  2170.9   401.6  2159.9     421 2137.98
   430.2  2135.4   442.5 2134.32   461.1  2135.5   477.4 2139.05   496.8 2138.44
   513.5 2140.65   558.3 2140.81   575.3 2138.33   597.7 2138.62   609.3 2136.37
   646.7  2141.6   690.8 2138.54   733.5 2143.71   756.1 2156.61   795.5 2184.86
   799.4 2188.47   807.2 2200.18   812.2 2204.34   923.6 2275.08   965.6 2303.64
#Mann= 3 ,-1 , 0
       0      .1       0   430.2    .045       0   461.1      .1       0
#XS Ineff= 2 , 0
                          651.32          2149.3
Permanent Ineff=
       F       F
Bank Sta=430.2,461.1
XS Rating Curve= 0 ,0
Exp/Cntr=0.3,0.1

Type RM Length L Ch R = 1 ,12713   ,345.5,348.6,348.9
XS GIS Cut Line= 3
     2141453.003      236687.319     2141189.983      237057.247
     2140956.855      237467.944
#Sta/Elev= 30
       0 2248.89    14.6 2240.99    34.8 2232.25   135.4 2195.77   155.5 2187.68
   163.6  2182.9   203.6 2168.56     236 2159.44   300.5 2146.62   333.5 2138.08
   368.9 2136.78   409.1  2137.9   413.2 2137.49   429.3 2130.18   462.6  2129.6
   472.1 2130.26   479.9  2132.4     495 2134.15   537.2  2134.1   551.5 2132.32
   578.1 2133.79   611.9 2131.29   616.6 2132.65   633.5 2143.31   655.9 2160.44
   682.1 2181.43   698.4 2198.27   724.9 2216.97   868.4 2300.62   926.2 2332.91
#Mann= 3 ,-1 , 0
       0      .1       0   429.3    .045       0   472.1      .1       0
Bank Sta=429.3,472.1
XS Rating Curve= 0 ,0
Exp/Cntr=0.3,0.1

Type RM Length L Ch R = 1 ,12365   ,388.4,394.9,396.6
XS GIS Cut Line= 3
      2141152.12      236546.689     2140881.924      236912.821
     2140607.513       237275.75
#Sta/Elev= 30
       0 2199.09    22.4 2189.73    34.7 2187.33   100.5 2163.39   111.6 2161.69
   144.7 2152.52   177.9 2141.65   226.3 2131.48   243.3 2129.97     316 2129.03
   341.8 2133.36   349.2 2132.31   362.9 2128.03   381.2 2129.27   413.9 2127.05
   428.6 2125.07   433.3 2122.32   459.1 2120.96     465 2122.27   471.1 2124.56
   483.4 2139.04   498.9 2153.91     514 2166.91   530.3  2178.4     601  2223.4
   693.3 2277.92   747.2 2307.52   800.1  2333.2   857.7 2359.13     910 2380.27
#Mann= 3 ,-1 , 0
       0      .1       0   433.3    .045       0     465      .1       0
#XS Ineff= 2 , 0
          381.17 2135.08
Permanent Ineff=
       F       F
Bank Sta=433.3,465
XS Rating Curve= 0 ,0
Exp/Cntr=0.3,0.1

Type RM Length L Ch R = 1 ,11970   ,323.9,305.1,295.9
XS GIS Cut Line= 4
     2140879.462      236414.427      2140530.56      236716.452
     2140379.234      236856.393     2140374.482      237048.004
#Sta/Elev= 30
       0 2167.48     9.1 2168.92    22.1 2167.48    50.9 2170.65    87.2 2170.32
   174.5 2155.12   214.6 2152.02   239.7 2148.65   248.6 2145.52   264.7  2135.4
   290.5 2122.92   329.9 2120.31     355  2120.1     370 2117.57   390.1 2118.15
   402.1 2115.62   421.3 2114.54   430.1 2115.53   438.6 2119.11   451.7 2121.98
   509.1 2119.95   537.6 2123.49   601.9 2120.72   634.6 2123.75   671.2 2128.72
   694.2  2134.5   736.5 2149.62   775.6  2169.6   799.2 2183.33   859.3 2213.92
#Mann= 3 ,-1 , 0
       0      .1       0   402.1    .045       0   430.1      .1       0
#XS Ineff= 2 ,-1
       0  355.01 2125.74  459.24   859.2 2127.57
Permanent Ineff=
       F       F
Bank Sta=402.1,430.1
XS Rating Curve= 0 ,0
Exp/Cntr=0.3,0.1

Type RM Length L Ch R = 1 ,11665   ,353.8,350,345.6
XS GIS Cut Line= 3
      2140357.48      236136.253     2140288.053      236585.881
     2140205.145      237033.516
#Sta/Elev= 30
       0 2320.17    18.9  2302.2    35.2 2291.03    48.5 2277.04    65.1 2276.23
    68.4 2274.57    88.3    2255   131.1 2226.22   188.6 2190.72   257.6 2153.28
   290.8 2138.17   300.8 2136.14   330.6 2118.24     387 2114.92   400.4 2115.73
   429.7 2109.24   466.8 2107.93   475.7 2109.16   503.5 2117.78   516.9 2118.76
   573.6 2120.17   630.3 2115.97   672.8 2119.07   743.8 2118.95   757.1 2120.79
   794.1 2140.77   857.2 2184.47   883.9 2201.03   893.9 2212.02   910.2 2222.35
#Mann= 3 ,-1 , 0
       0      .1       0   429.7    .045       0   475.7      .1       0
Bank Sta=429.7,475.7
XS Rating Curve= 0 ,0
Exp/Cntr=0.3,0.1

Type RM Length L Ch R = 1 ,11315   ,349,350,350.9
XS GIS Cut Line= 3
     2139940.851      236092.142     2139940.851      236547.142
     2139940.851      237002.142
#Sta/Elev= 30
       0 2263.26    26.4 2245.55    55.9 2244.89    78.9 2228.51    88.7 2224.73
   137.9 2212.61   151.1 2206.16   167.5 2204.75   190.4 2194.51   236.4 2164.07
   269.2 2133.34     302 2110.73   318.4 2106.72   334.8 2109.58   390.6 2107.91
   416.8 2110.82   429.9 2109.16   436.5 2104.42   452.9 2103.31   472.6 2104.59
   492.3 2106.76   534.9 2107.53   551.3 2113.28   584.1 2110.73   613.7 2112.93
   669.4  2111.9   712.1 2119.39   748.2 2132.74   800.7 2157.47     910 2221.39
#Mann= 3 ,-1 , 0
       0      .1       0   436.5    .045       0   472.6      .1       0
#XS Ineff= 2 , 0
          414.86 2116.72
Permanent Ineff=
       F       F
Bank Sta=436.5,472.6
XS Rating Curve= 0 ,0
Exp/Cntr=0.3,0.1

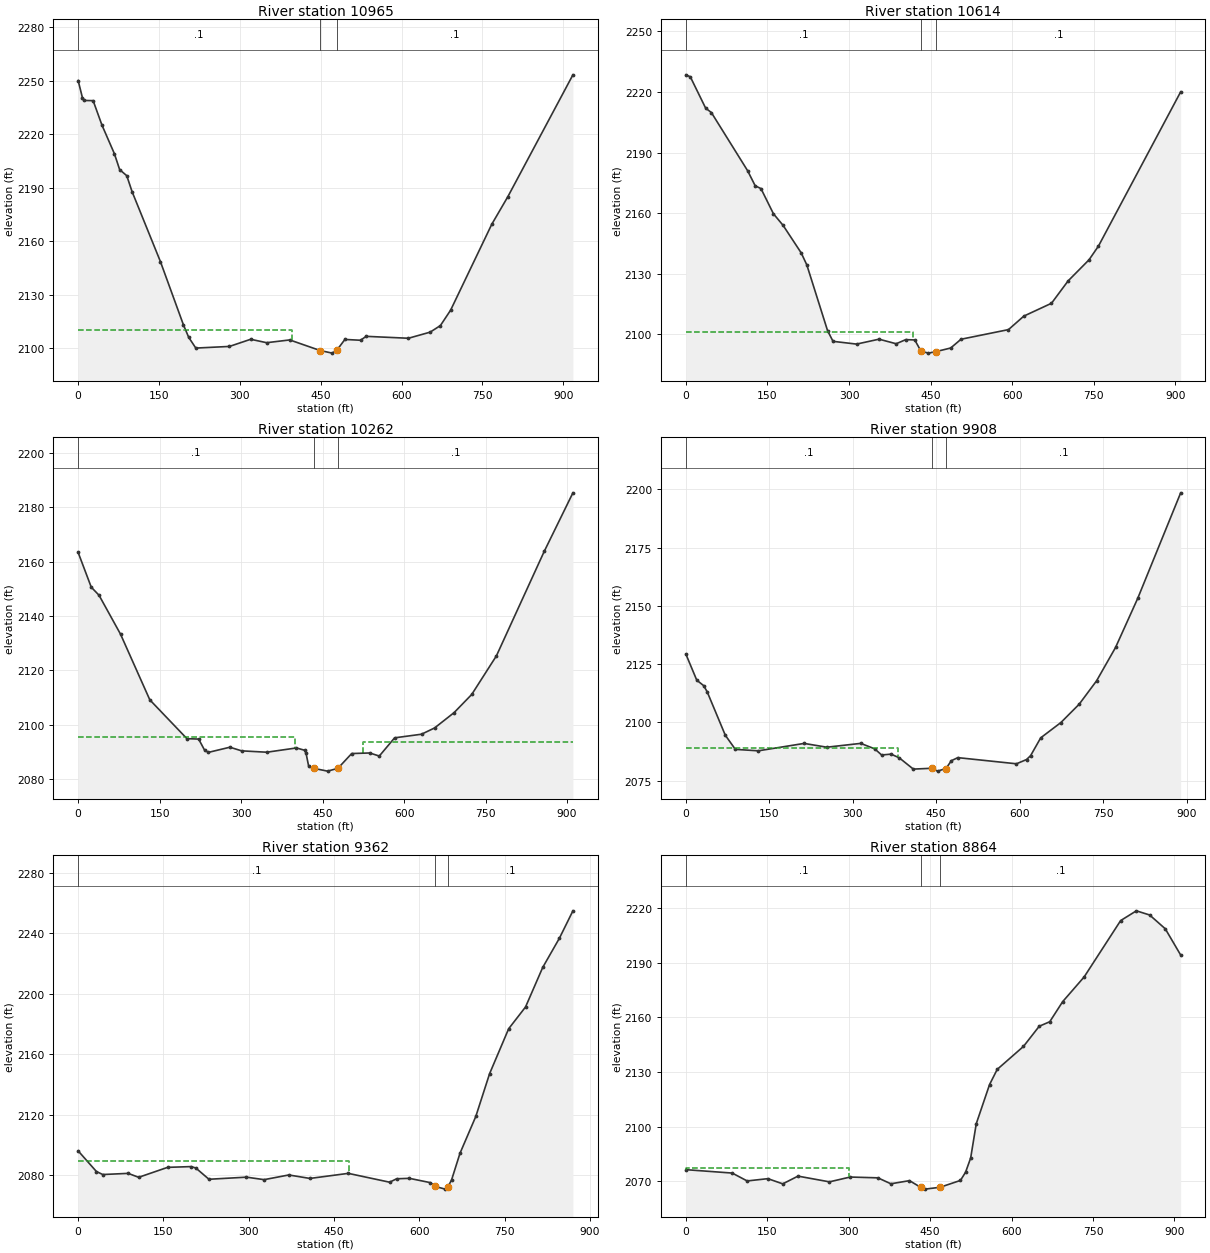
Type RM Length L Ch R = 1 ,10965   ,344.3,350.8,356.1
XS GIS Cut Line= 3
     2139619.897       236120.35     2139596.186      236584.525
     2139558.656      237036.223
#Sta/Elev= 30
       0    2250       8 2240.34    11.3 2238.87    27.8 2238.77    44.2 2225.04
    67.2 2209.09      77 2200.15    90.2 2196.74     100 2187.86   152.6 2148.69
   195.3 2113.26   205.1 2106.25   218.3 2100.23   280.7 2101.15   320.1 2105.15
   349.7 2103.24   392.6 2104.79   448.9 2098.87   471.3  2097.4   479.7 2098.92
   494.9 2105.06   523.9 2104.61   534.4  2106.8   612.8 2105.73     653 2109.14
   672.1 2112.82   691.1 2121.47   767.5 2169.59   797.2 2184.96     918 2253.23
#Mann= 3 ,-1 , 0
       0      .1       0   448.9    .045       0   479.7      .1       0
#XS Ineff= 2 , 0
          397.32 2110.41
Permanent Ineff=
       F       F
Bank Sta=448.9,479.7
XS Rating Curve= 0 ,0
Exp/Cntr=0.3,0.1

Type RM Length L Ch R = 1 ,10614   ,348.5,351.4,352.4
XS GIS Cut Line= 3
     2139421.893      236058.291     2139262.043      236484.304
     2139099.039      236909.101
#Sta/Elev= 30
       0 2228.44     8.1 2227.46    36.3 2211.95    46.8 2209.79   113.4 2181.03
   127.4 2173.55   138.1 2172.13     161 2159.68   178.8 2153.93     212 2140.35
   222.4 2134.37   260.6 2101.79   270.6 2096.56   313.9  2095.2   355.2 2097.63
   386.7 2095.37   404.3  2097.4   420.9 2097.26   432.3 2091.72   446.1 2090.73
   460.3  2091.5     487 2093.27     506  2097.6   593.3 2102.37   621.6 2109.06
   672.4  2115.4   702.9 2126.45   741.5 2136.93   758.8 2143.71     910 2220.03
#Mann= 3 ,-1 , 0
       0      .1       0   432.3    .045       0   460.3      .1       0
#XS Ineff= 2 , 0
          416.92 2101.08
Permanent Ineff=
       F       F
Bank Sta=432.3,460.3
XS Rating Curve= 0 ,0
Exp/Cntr=0.3,0.1

Type RM Length L Ch R = 1 ,10262   ,354.6,354.2,354.6
XS GIS Cut Line= 3
     2139114.657       235965.35     2138928.277      236381.291
     2138760.602      236804.119
#Sta/Elev= 30
       0 2163.36    24.1  2150.6    38.4 2147.63      78  2133.3   131.9 2109.14
   200.2 2094.86   221.8  2094.7   232.6 2090.67   239.8 2089.81   279.3 2091.71
   300.9 2090.37   347.2 2089.87   401.9 2091.44   416.8 2090.59   419.5 2089.48
   424.2 2084.81   433.9 2083.92     459 2082.91  478.06 2083.93   503.5 2089.38
   536.7 2089.59   554.3 2088.46   582.5 2095.16     632 2096.49   656.1  2098.8
     692 2104.44   724.4 2111.11   769.9 2125.33   857.8 2163.73   910.7 2185.31
#Mann= 3 ,-1 , 0
       0      .1       0   433.9    .045       0  478.06      .1       0
#XS Ineff= 2 ,-1
       0  398.35 2095.61  524.25   910.6 2093.58
Permanent Ineff=
       F       F
Bank Sta=433.9,478.06
XS Rating Curve= 0 ,0
Exp/Cntr=0.3,0.1

Type RM Length L Ch R = 1 ,9908    ,542.1,546,541.7
XS GIS Cut Line= 2
     2138794.049      235851.246     2138411.221      236654.089
#Sta/Elev= 30
       0 2129.21    19.5 2118.07    31.8 2115.74    38.1 2113.15    70.8 2094.44
    88.9 2088.36   130.2 2087.75   212.5 2090.92   253.3  2089.3   314.3 2090.94
   339.4 2088.59   351.8 2085.96   368.8 2086.32   383.4 2084.76   408.8  2079.9
   441.5 2080.25   452.4 2079.03   467.4 2080.15   477.3 2083.52   488.8 2084.82
   594.2 2082.18   612.3    2084   619.6 2085.66   637.8 2093.32   674.1 2099.89
   706.9 2107.74   738.2 2117.78   772.3 2132.09   812.3 2153.24   889.4 2198.47
#Mann= 3 ,-1 , 0
       0      .1       0   441.5    .045       0   467.4      .1       0
#XS Ineff= 2 , 0
          381.84 2089.09
Permanent Ineff=
       F       F
Bank Sta=441.5,467.4
XS Rating Curve= 0 ,0
Exp/Cntr=0.3,0.1

Type RM Length L Ch R = 1 ,9362    ,495.7,498.7,499.5
XS GIS Cut Line= 2
     2138392.993      235732.596     2137983.914      236500.438
#Sta/Elev= 30
       0 2096.12    32.1 2082.46    43.3 2080.46    87.9 2081.23   106.4 2078.62
   157.3 2085.21   198.5 2085.71   206.8 2084.81     230 2077.33     296 2078.72
     327 2077.07   370.4 2080.17   407.6 2077.88     475 2081.23   547.7 2075.38
     560 2077.65   582.3 2077.95   619.5 2075.08   627.8 2072.58   645.5  2070.8
   650.4 2072.43   656.6 2076.87   671.4  2094.5   699.2 2118.87   723.5 2147.23
     757 2176.93   786.7 2191.36   816.9 2217.53   846.2 2236.83     870 2254.98
#Mann= 3 ,-1 , 0
       0      .1       0   627.8    .045       0   650.4      .1       0
#XS Ineff= 2 , 0
          475.75  2089.7
Permanent Ineff=
       F       F
Bank Sta=627.8,650.4
XS Rating Curve= 0 ,0
Exp/Cntr=0.3,0.1

Type RM Length L Ch R = 1 ,8864    ,353.8,350.2,344.6
XS GIS Cut Line= 3
     2138016.906      235591.866     2137744.018      235956.598
     2137434.761      236291.634
#Sta/Elev= 30
       0 2076.39    85.3 2074.53   112.8 2070.21     151 2071.46   178.4 2068.62
   206.5 2072.85   264.4 2069.71   302.6 2072.35   353.7 2071.91   377.6 2068.65
   411.9 2070.37   432.4 2066.72   440.6 2065.72  468.25 2066.74   505.8  2070.5
   515.2 2074.99   524.6 2082.79   534.9 2101.59   559.4 2123.06   573.5 2131.38
   621.9 2143.99   650.9 2155.04   670.3 2157.52   694.1 2168.53   733.6 2182.06
   800.9 2212.99   829.9 2218.34   854.3 2216.06   883.1  2208.5   911.5  2194.1
#Mann= 3 ,-1 , 0
       0      .1       0   432.4    .045       0  468.25      .1       0
#XS Ineff= 2 , 0
          300.31  2077.3
Permanent Ineff=
       F       F
Bank Sta=432.4,468.25
XS Rating Curve= 0 ,0
Exp/Cntr=0.3,0.1

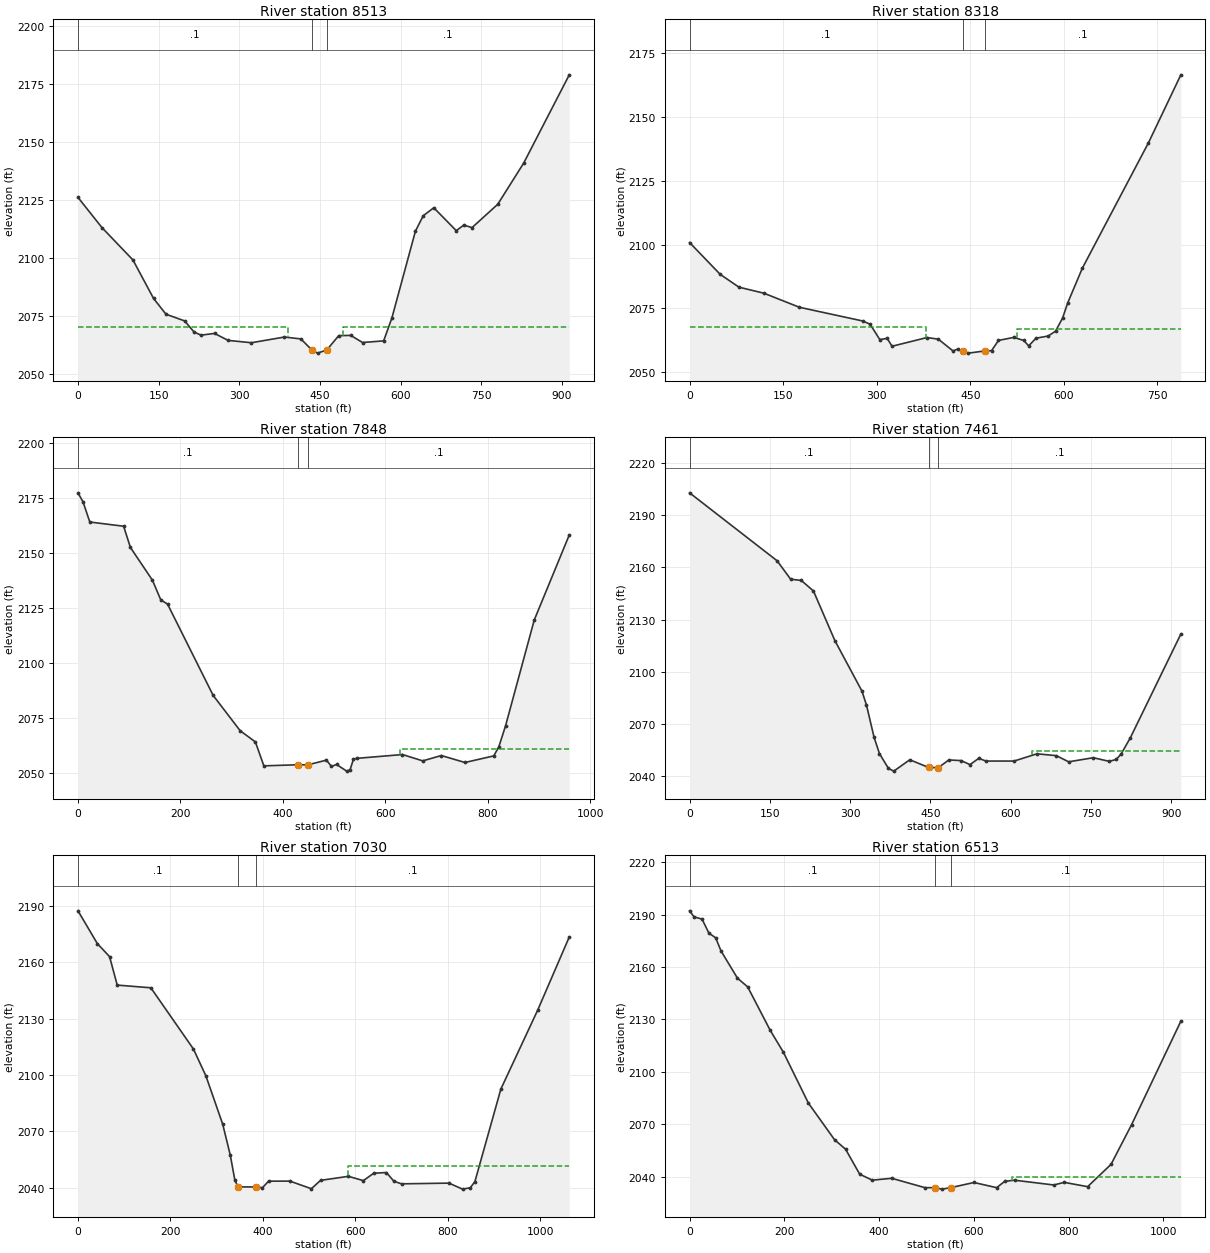
Type RM Length L Ch R = 1 ,8513    ,191.9,195.1,197.3
XS GIS Cut Line= 3
     2137663.842       235330.13     2137473.522      235742.493
     2137273.383      236156.384
#Sta/Elev= 30
       0 2125.96    44.5 2112.97   102.3 2098.98   140.6 2082.41   163.7 2075.61
   198.5 2072.72   215.8 2067.96   228.8 2066.58     254 2067.33   279.3 2064.33
   322.7 2063.32   384.1 2065.78   414.7 2064.96   434.7 2060.27   445.6 2058.84
   462.9 2060.21     485 2066.37   507.4 2066.48   529.3 2063.42   568.6 2064.12
     584 2074.03   627.7 2111.39   642.2 2118.04   661.9  2121.5   703.7 2111.62
   717.6 2114.01   733.1 2112.96   780.8 2122.98     829  2140.7   913.9 2178.79
#Mann= 3 ,-1 , 0
       0      .1       0   434.7    .045       0   462.9      .1       0
#XS Ineff= 2 , 0
          391.12 2070.03  493.29         2070.27
Permanent Ineff=
       F       F
Bank Sta=434.7,462.9
XS Rating Curve= 0 ,0
Exp/Cntr=0.3,0.1

Type RM Length L Ch R = 1 ,8318    ,479.9,470.6,462.8
XS GIS Cut Line= 2
      2137552.96      235268.828     2137124.194      235929.478
#Sta/Elev= 30
       0 2100.77    49.2  2088.3    79.3  2083.3     119 2080.97     176 2075.46
   277.7 2070.08   289.4 2068.83     305 2062.81   316.8 2063.29   324.6 2060.21
   380.7 2063.62   398.9 2062.97   422.4 2058.36   430.2 2059.15     438 2058.17
     447 2057.52   473.2 2058.37   484.2  2058.5   495.2 2062.48   519.8 2063.68
   535.8 2062.46   543.6 2060.36   555.4 2063.36   574.9 2064.21   586.7  2066.1
   598.1 2071.29   606.2 2077.16   629.7 2090.75   735.7 2139.79   787.6 2166.36
#Mann= 3 ,-1 , 0
       0      .1       0     438    .045       0   473.2      .1       0
#XS Ineff= 2 , 0
          379.77 2067.67  524.25         2066.96
Permanent Ineff=
       F       F
Bank Sta=438,473.2
XS Rating Curve= 0 ,0
Exp/Cntr=0.3,0.1

Type RM Length L Ch R = 1 ,7848    ,385.4,386.8,385.5
XS GIS Cut Line= 2
     2136916.373       234940.69     2137014.815      235894.477
#Sta/Elev= 30
       0 2177.35     9.9  2173.2    23.1 2164.06    89.1 2162.14   102.3 2152.49
   145.2 2137.61   161.6 2128.62   174.8 2126.69   263.9 2085.09   316.5 2069.04
   346.3 2063.92   362.8 2053.03   428.8 2053.52   448.6 2053.49   484.9 2055.63
   494.8 2052.78   504.7 2053.66   524.5 2050.63     531 2051.21   537.6    2056
   543.7 2056.44   633.4 2058.18   672.9  2055.3   709.2 2057.73   755.3 2054.56
   811.4 2057.56   821.3  2061.6   834.5 2071.22   890.6 2119.46   958.9 2158.16
#Mann= 3 ,-1 , 0
       0      .1       0   428.8    .045       0   448.6      .1       0
#XS Ineff= 2 , 0
                          628.95         2060.56
Permanent Ineff=
       F       F
Bank Sta=428.8,448.6
XS Rating Curve= 0 ,0
Exp/Cntr=0.3,0.1

Type RM Length L Ch R = 1 ,7461    ,432,430.5,427.6
XS GIS Cut Line= 3
     2136514.766      234929.392      2136594.01      235376.197
     2136629.826       235838.59
#Sta/Elev= 30
       0  2202.9   163.4 2163.82   188.8  2153.2   208.7 2152.47   231.4 2146.41
   271.4 2117.86   321.9 2088.85   330.4 2080.78   344.7 2062.11   354.7 2052.81
   371.4 2044.32   381.4 2042.75   411.3 2049.28   446.4 2044.87   464.5 2044.74
   484.3 2049.18   507.3 2048.81   523.8 2046.49   540.2 2050.13   553.4 2048.55
     606 2048.54   648.8 2052.71     685 2051.66     708 2048.11   754.1 2050.47
   783.7 2048.38   796.9 2049.45   806.2 2052.69   823.2  2061.9   917.6 2121.64
#Mann= 3 ,-1 , 0
       0      .1       0   446.4    .045       0   464.5      .1       0
#XS Ineff= 2 , 0
                          639.47         2054.12
Permanent Ineff=
       F       F
Bank Sta=446.4,464.5
XS Rating Curve= 0 ,0
Exp/Cntr=0.3,0.1

Type RM Length L Ch R = 1 ,7030    ,525.1,517.6,505.8
XS GIS Cut Line= 2
     2136124.468      235010.693     2136255.723      236065.109
#Sta/Elev= 30
       0 2187.24    41.9 2169.82    68.3 2162.91    84.9 2147.77   157.6 2146.34
   249.7 2113.81   276.6 2099.58     313 2073.88   329.5 2057.34   339.4 2044.01
  346.46 2040.54   385.7 2040.51     399 2040.09   412.2 2043.58   458.4 2043.61
   504.8 2039.56   524.6    2044   584.8 2046.15   617.2 2043.88   639.8 2047.81
   667.2 2048.17   683.3 2043.52   699.8 2042.16   802.4 2042.54   831.8 2039.35
   848.6 2040.09   858.5 2043.35   914.7 2092.55   994.1 2134.36  1062.6 2173.34
#Mann= 3 ,-1 , 0
       0      .1       0  346.46    .045       0   385.7      .1       0
#XS Ineff= 2 , 0
                          584.26         2051.72
Permanent Ineff=
       F       F
Bank Sta=346.46,385.7
XS Rating Curve= 0 ,0
Exp/Cntr=0.3,0.1

Type RM Length L Ch R = 1 ,6513    ,382.1,389.3,389
XS GIS Cut Line= 2
     2135540.383      235155.074     2136045.715      236060.733
#Sta/Elev= 30
       0 2192.13     9.5 2188.69    26.4 2187.37    40.8 2179.36    55.1 2176.69
    66.4 2169.15   101.1 2153.58   122.7 2148.58   170.1 2123.79   197.9 2111.25
   250.9 2082.03   306.1 2061.07   329.4 2055.64   359.1 2041.37   385.7 2037.93
   426.7 2039.01   496.6 2033.66   518.3 2033.61   532.8  2032.8     551 2033.63
   600.3  2036.6   648.2 2033.64   665.4 2037.28   686.3 2037.91   768.9 2035.17
   790.8 2036.68   840.3 2034.21   889.7 2046.98   933.1  2069.7  1037.1 2128.93
#Mann= 3 ,-1 , 0
       0      .1       0   518.3    .045       0     551      .1       0
#XS Ineff= 2 , 0
                          680.27         2039.69
Permanent Ineff=
       F       F
Bank Sta=518.3,551
XS Rating Curve= 0 ,0
Exp/Cntr=0.3,0.1

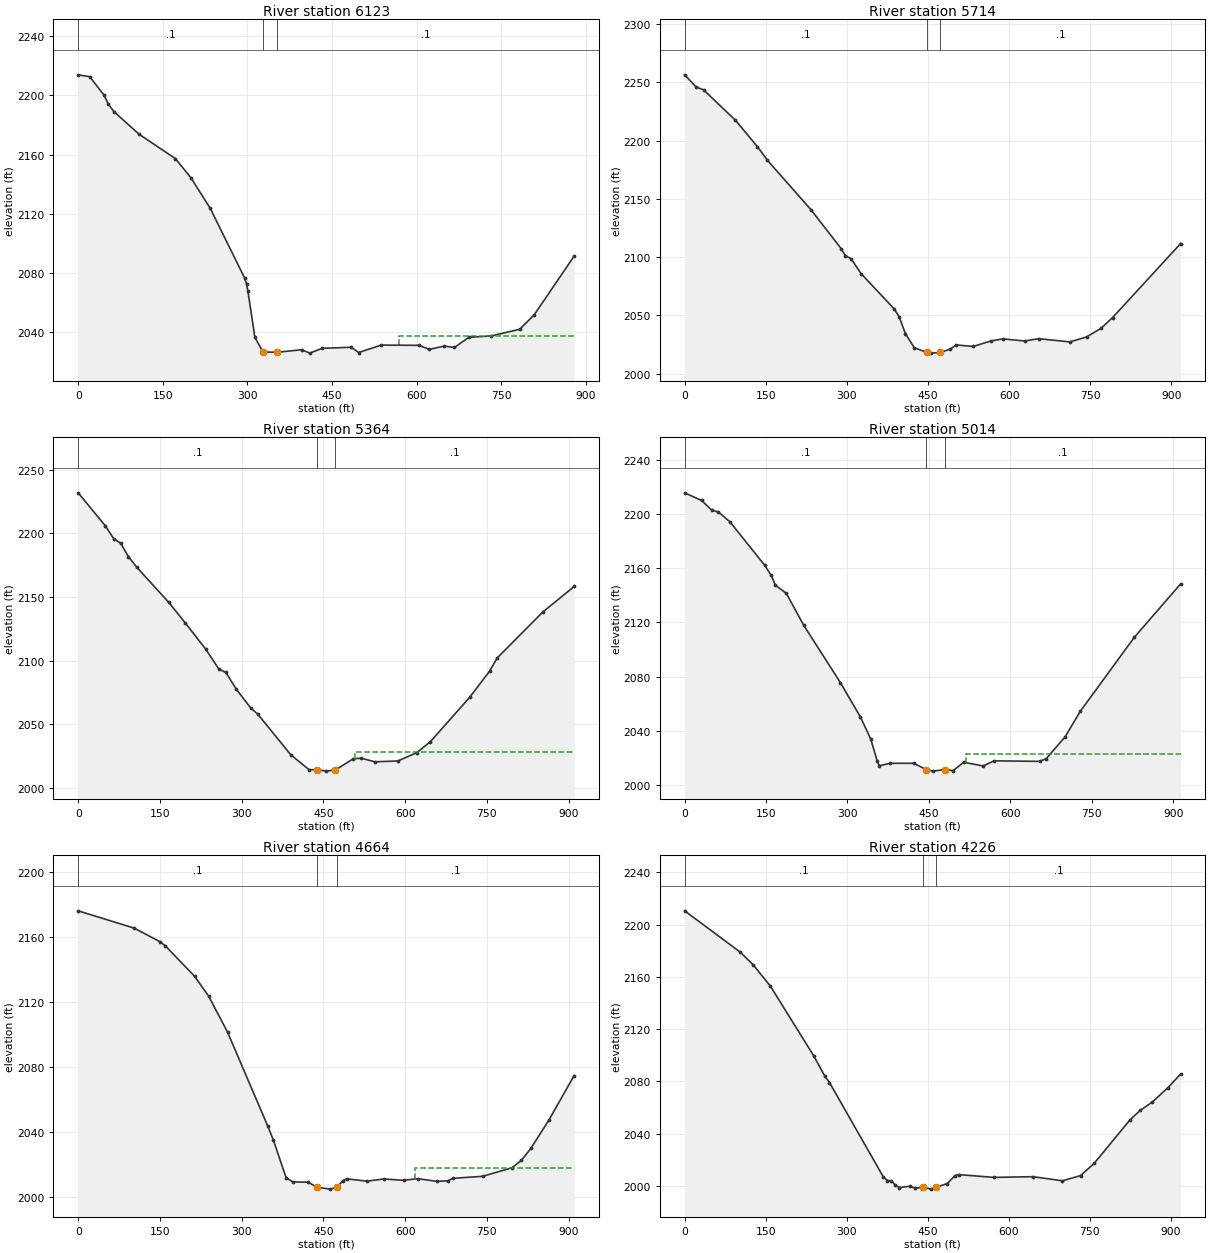
Type RM Length L Ch R = 1 ,6123    ,414.8,409.9,403.1
XS GIS Cut Line= 2
     2135288.811      235299.454     2135656.325      236097.922
#Sta/Elev= 30
       0 2213.92    20.4 2212.64    45.7 2200.25    53.4 2194.12    63.3 2189.07
   107.8 2173.81   172.2 2157.34   199.4 2144.55     234 2123.73   294.9 2076.67
   298.3 2072.76   300.8 2067.72   313.1 2036.62   327.4 2026.64   352.7  2026.5
     396 2028.18   410.5  2025.9   432.2 2029.14   483.8 2029.87   497.2 2026.32
   536.9 2031.33   603.8 2031.17   622.3 2028.45   648.9 2030.65   666.8 2029.72
   692.2 2036.56   731.9 2037.52   782.5 2042.01   807.8 2051.59     879 2091.44
#Mann= 3 ,-1 , 0
       0      .1       0   327.4    .045       0   352.7      .1       0
#XS Ineff= 2 , 0
                          568.93         2037.75
Permanent Ineff=
       F       F
Bank Sta=327.4,352.7
XS Rating Curve= 0 ,0
Exp/Cntr=0.3,0.1

Type RM Length L Ch R = 1 ,5714    ,347.6,350,350.5
XS GIS Cut Line= 3
     2134791.231      235543.118     2135122.233      235862.016
     2135428.906      236201.705
#Sta/Elev= 30
       0 2256.56      21 2246.17    34.9 2243.71    93.9 2217.54   134.6 2194.86
   153.1 2183.17   233.5  2140.8   289.8 2107.13     297  2101.4     308 2098.62
   326.2 2085.92   387.5  2055.6   396.8 2048.79   408.2 2034.39   424.6 2022.33
   447.8 2018.16   455.8 2017.62   472.9 2018.16   491.4 2021.14   502.3 2024.66
   533.8 2023.33   566.5 2028.11   588.6 2029.84     629 2028.05   654.9 2030.03
   712.4 2027.23   743.3 2031.52   769.9 2038.86   791.6 2048.19   917.3 2111.73
#Mann= 3 ,-1 , 0
       0      .1       0   447.8    .045       0   472.9      .1       0
Bank Sta=447.8,472.9
XS Rating Curve= 0 ,0
Exp/Cntr=0.3,0.1

Type RM Length L Ch R = 1 ,5364    ,347.7,349.5,350.3
XS GIS Cut Line= 3
     2134565.248      235716.441     2134848.754      236072.313
     2135127.181      236432.229
#Sta/Elev= 30
       0 2231.81      50 2205.76    65.3 2195.73    77.9 2192.18    92.1  2181.8
   107.2 2173.51   165.9 2145.95   196.2 2129.83   234.3 2108.94   258.2 2093.35
   270.8 2090.95   290.2 2077.59   316.9 2062.73   329.3 2058.19     390 2026.22
   423.8 2014.46     439 2014.51   455.4 2013.37     472 2014.28   505.1 2023.16
   519.8 2023.46   544.3  2020.7   586.4 2021.33   621.3 2027.88   646.2  2036.5
   718.1 2071.22   754.7 2091.75   768.8 2102.21   852.2 2138.16     910 2158.31
#Mann= 3 ,-1 , 0
       0      .1       0     439    .045       0     472      .1       0
#XS Ineff= 2 , 0
                          508.77         2028.29
Permanent Ineff=
       F       F
Bank Sta=439,472
XS Rating Curve= 0 ,0
Exp/Cntr=0.3,0.1

Type RM Length L Ch R = 1 ,5014    ,341.4,349.8,358
XS GIS Cut Line= 3
     2134286.856      235869.545     2134545.666        236242.8
     2134805.275      236622.077
#Sta/Elev= 30
       0 2215.51    31.2 2209.86    50.1 2202.64    61.9 2201.43    83.1 2194.25
   147.3 2162.14   159.3 2154.71   167.3 2147.27   187.2 2141.44   219.2  2117.9
     287 2075.44   323.6  2050.3   342.9 2033.82   354.9 2017.47   358.9 2014.16
   378.8    2016   422.3 2015.97   445.3 2011.28   457.9 2010.21   479.2 2011.37
   494.5  2010.6   514.3 2016.73   550.1 2014.03     570 2017.81   653.8 2017.41
     666 2019.35   700.8  2035.4     729 2054.38   828.4 2108.88   913.8 2148.33
#Mann= 3 ,-1 , 0
       0      .1       0   445.3    .045       0   479.2      .1       0
#XS Ineff= 2 , 0
                          519.09          2022.8
Permanent Ineff=
       F       F
Bank Sta=445.3,479.2
XS Rating Curve= 0 ,0
Exp/Cntr=0.3,0.1

Type RM Length L Ch R = 1 ,4664    ,445,438,432.8
XS GIS Cut Line= 3
     2134126.213      235919.712     2134223.099       236364.25
     2134330.212      236806.613
#Sta/Elev= 30
       0 2176.14   102.8 2165.47   149.8 2157.16   159.7 2154.65   213.6 2135.85
   239.6 2123.49     274 2101.51   347.9 2043.59   358.2 2034.94   381.5 2011.87
     394 2009.27   421.8 2009.08   438.5 2005.97   462.1 2004.82   474.3 2005.84
   485.7 2010.01   492.7 2011.16   529.6 2009.72   560.6 2011.07   597.1 2010.25
   623.2 2011.27   657.9  2009.6   678.1 2009.93   688.3 2011.49   742.3 2012.72
   796.3    2018   813.4 2022.62   830.6 2029.86   863.8 2047.37   910.1 2074.75
#Mann= 3 ,-1 , 0
       0      .1       0   438.5    .045       0   474.3      .1       0
#XS Ineff= 2 , 0
                          617.13         2017.94
Permanent Ineff=
       F       F
Bank Sta=438.5,474.3
XS Rating Curve= 0 ,0
Exp/Cntr=0.3,0.1

Type RM Length L Ch R = 1 ,4226    ,311.9,316.9,322.1
XS GIS Cut Line= 2
     2133638.136      236161.445     2134056.538      236979.153
#Sta/Elev= 30
       0 2210.48   102.9 2178.88   126.8 2169.23   158.5 2153.07   239.3 2099.41
   259.8 2083.88   268.2 2079.19   368.1 2006.89   375.6 2004.27     383 2004.06
   390.4 2000.52   397.7 1998.91   416.9 1999.87   427.2  1998.4     442  1999.2
   455.9 1997.68  466.36 1999.16   486.2 2001.94   500.9 2008.08   508.3 2008.77
   572.4 2006.64   644.7  2007.2   699.7 2004.05   733.1 2008.02   758.2 2017.28
   825.2 2050.87   843.5 2057.82   865.8 2064.21   895.3 2075.34   918.5  2085.7
#Mann= 3 ,-1 , 0
       0      .1       0     442    .045       0  466.36      .1       0
Bank Sta=442,466.36
XS Rating Curve= 0 ,0
Exp/Cntr=0.3,0.1