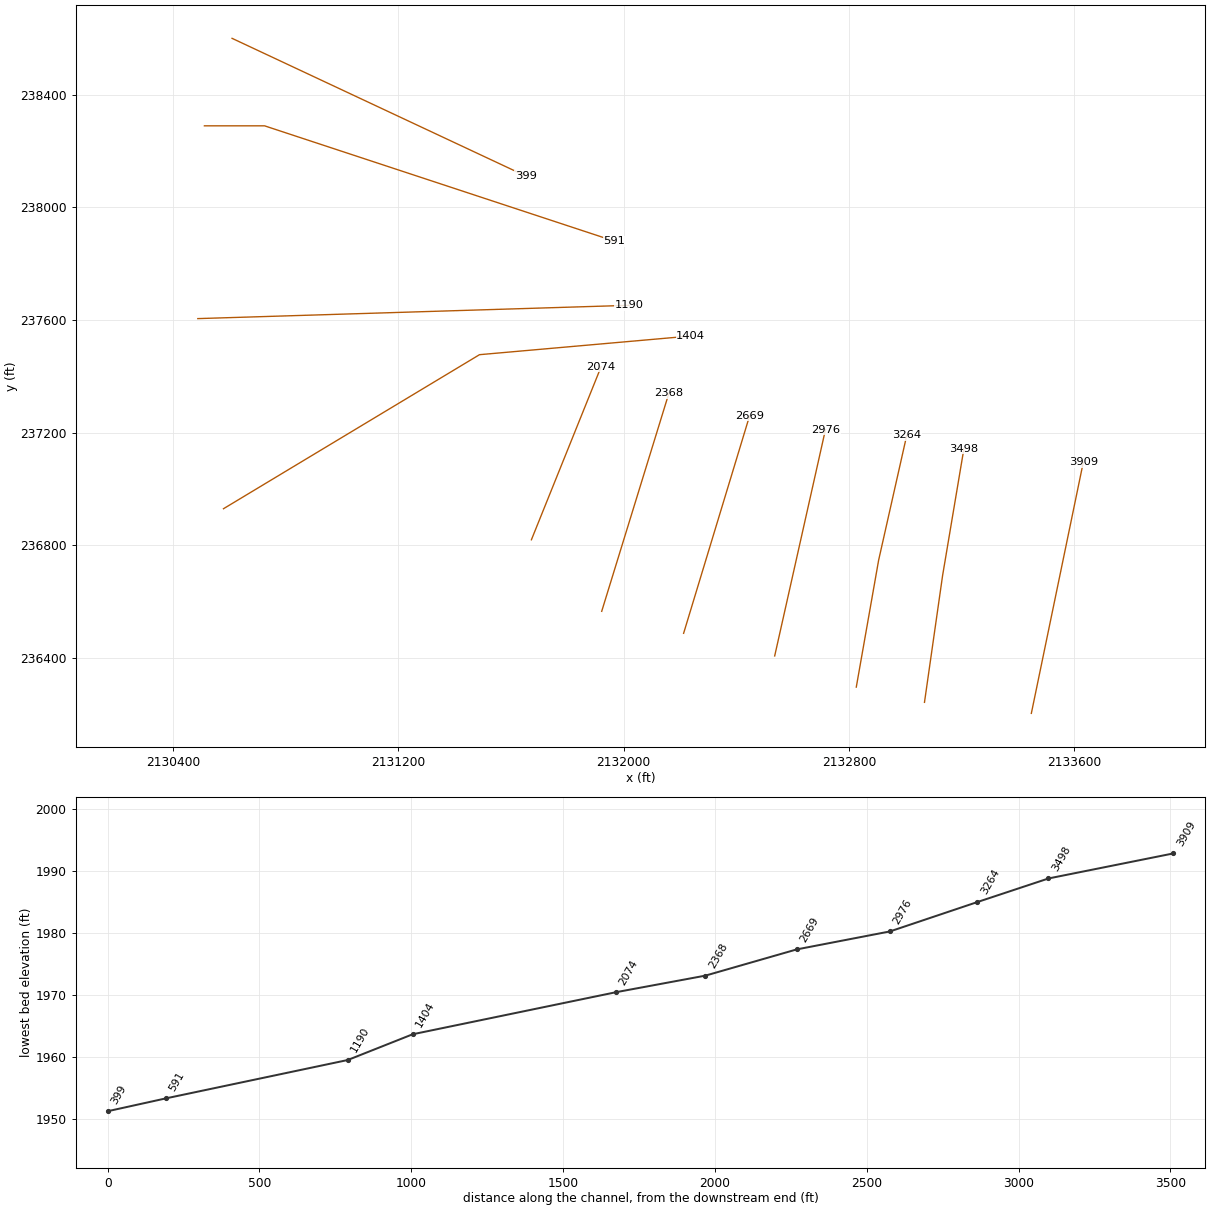
HEC-RAS study LAURELCK3.prj: LAURELCK3

--- LAURELCK3.g01 (geometry) --- (continued)

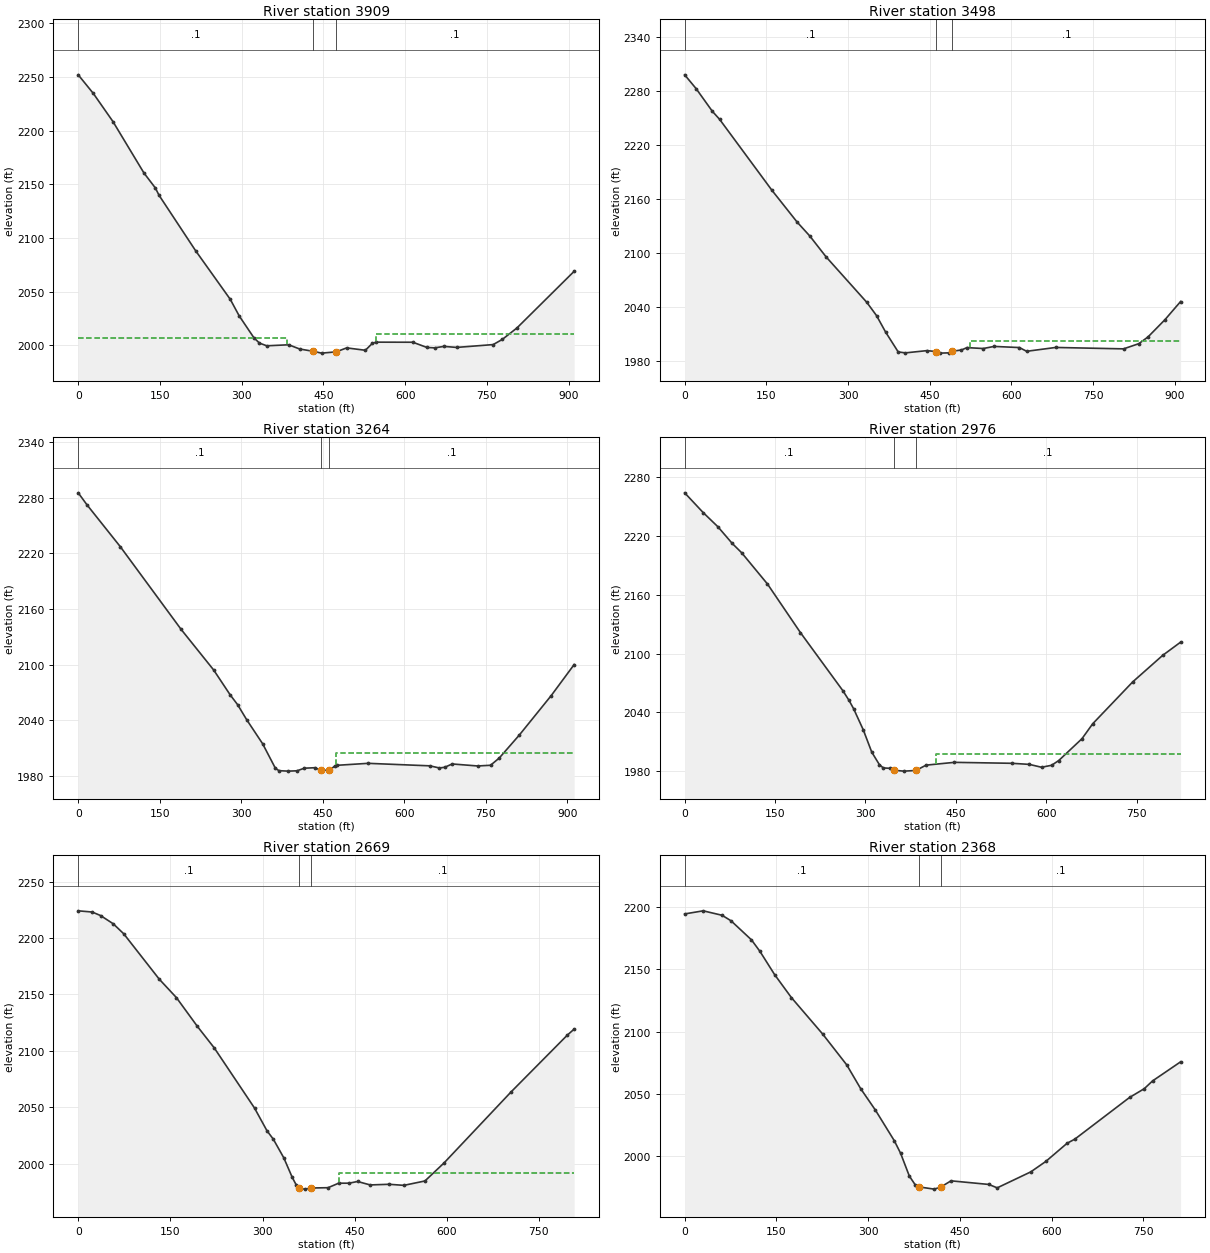
Type RM Length L Ch R = 1 ,3909    ,409.4,411.5,411.5
XS GIS Cut Line= 3
     2133447.451      236202.965     2133539.637      236648.528
     2133631.822      237094.092
#Sta/Elev= 30
       0  2252.1    27.7 2234.77    63.7 2208.58   120.6 2160.65   141.6 2146.65
   148.3 2139.87   215.3  2088.3     279 2042.92   295.5 2027.38   322.5 2007.02
   332.6 2002.11     346  1999.6   386.2 2000.56   406.3 1996.64   431.6 1994.43
   446.5 1992.78   473.2 1993.95   492.6 1997.66   526.9 1995.44   539.8 2001.92
     547    2003     614 2002.93   639.8 1998.07   654.2 1997.71     671 1999.05
   694.4  1998.1   761.4 2000.74   778.2 2005.57     805 2016.22     910 2069.03
#Mann= 3 ,-1 , 0
       0      .1       0   431.6    .045       0   473.2      .1       0
#XS Ineff= 2 , 0
          382.87 2006.76  545.92          2010.9
Permanent Ineff=
       F       F
Bank Sta=431.6,473.2
XS Rating Curve= 0 ,0
Exp/Cntr=0.3,0.1

Type RM Length L Ch R = 1 ,3498    ,233.8,234,233.8
XS GIS Cut Line= 3
     2133068.061      236242.117     2133132.383       236692.36
      2133207.96      237142.109
#Sta/Elev= 30
       0 2298.37      21 2283.01    50.8 2257.81    64.1  2248.9     160 2170.12
   206.6 2134.49   229.8 2119.06   259.6 2095.94   334.5 2045.26   352.4 2030.48
     369 2012.23   392.2 1990.08   405.4 1989.03   445.2 1991.55   461.8 1990.47
   468.5 1988.75   485.1 1989.05   491.7 1990.84   508.4 1992.25   518.4 1994.89
   548.3 1993.88   568.3 1996.21   614.8 1994.95   628.1 1990.78   681.4 1995.06
   806.1  1993.5   834.2 1999.29     851 2006.75   882.2    2026   910.9 2046.18
#Mann= 3 ,-1 , 0
       0      .1       0   461.8    .045       0   491.7      .1       0
#XS Ineff= 2 , 0
                          523.22         2002.03
Permanent Ineff=
       F       F
Bank Sta=461.8,491.7
XS Rating Curve= 0 ,0
Exp/Cntr=0.3,0.1

Type RM Length L Ch R = 1 ,3264    ,291.6,288.2,287.7
XS GIS Cut Line= 3
     2132825.955      236296.244     2132905.371      236747.142
     2133005.195      237190.541
#Sta/Elev= 30
       0 2285.24    16.1 2272.31    77.7 2226.93   189.3  2137.9   249.3 2093.99
   279.8 2067.03   293.1 2056.78     310 2040.35   339.2 2014.55   362.6 1988.19
   369.2 1985.45   385.9 1984.96   402.5  1985.3   415.9 1988.12   435.9 1988.65
   445.8 1985.95   462.1 1985.87   472.6 1990.76     476 1991.24   533.2 1993.37
   646.8 1990.67   664.3 1988.39   674.2 1989.09   687.9 1992.69   734.9 1990.52
   758.5 1991.28   774.6 1999.14   811.5 2023.94   870.1 2066.46   912.3 2099.96
#Mann= 3 ,-1 , 0
       0      .1       0   445.8    .045       0   462.1      .1       0
#XS Ineff= 2 , 0
                          474.72         2004.39
Permanent Ineff=
       F       F
Bank Sta=445.8,462.1
XS Rating Curve= 0 ,0
Exp/Cntr=0.3,0.1

Type RM Length L Ch R = 1 ,2976    ,308.5,306.9,305.6
XS GIS Cut Line= 2
     2132536.303      236406.921     2132716.424      237209.872
#Sta/Elev= 30
       0 2263.66    30.6  2243.6      55 2229.18    78.8 2212.19    94.5 2202.66
   137.4 2170.79     192 2121.37   262.6 2062.04   272.7 2052.26   280.2  2043.9
   296.2 2022.47   310.4 1999.59   323.1  1986.8   329.6 1983.48   340.6 1983.11
   346.7 1981.15   363.5 1980.23   383.6 1980.87   400.5 1986.32   447.5 1989.17
   542.7 1988.21   571.9  1987.1   592.1 1984.17   608.9 1986.19   620.7 1991.04
   659.2 2013.23     677 2028.45   743.4 2071.11   793.1 2098.12   822.9  2111.6
#Mann= 3 ,-1 , 0
       0      .1       0   346.7    .045       0   383.6      .1       0
#XS Ineff= 2 , 0
                          416.92         1997.89
Permanent Ineff=
       F       F
Bank Sta=346.7,383.6
XS Rating Curve= 0 ,0
Exp/Cntr=0.3,0.1

Type RM Length L Ch R = 1 ,2669    ,300.3,300.9,301
XS GIS Cut Line= 2
     2132212.952      236487.216     2132447.327      237259.785
#Sta/Elev= 30
       0 2224.12    22.7 2223.06    36.4 2219.93      57 2212.63    74.1 2203.77
   131.8 2163.59   159.9 2147.14   194.1 2121.56   221.6 2102.45     287 2049.23
   307.3 2029.06   317.6 2021.63   334.7 2005.04   348.4 1987.75   355.1 1980.84
   358.7 1978.36   368.5 1977.34   379.7 1978.34   406.7 1978.61   423.9 1982.59
     441 1982.62   454.7 1984.11   475.3 1981.06   506.1 1981.63   530.1 1980.69
   564.4 1984.57   595.3 2000.45   704.5 2063.47   796.4 2114.02   807.3 2119.23
#Mann= 3 ,-1 , 0
       0      .1       0   358.7    .045       0   379.7      .1       0
#XS Ineff= 2 , 0
                          425.18         1991.55
Permanent Ineff=
       F       F
Bank Sta=358.7,379.7
XS Rating Curve= 0 ,0
Exp/Cntr=0.3,0.1

Type RM Length L Ch R = 1 ,2368    ,295.8,293.9,292.2
XS GIS Cut Line= 2
     2131922.154      236565.341     2132160.869      237340.081
#Sta/Elev= 30
       0 2194.68    30.3 2197.17    61.2 2193.57    75.9  2189.1   109.2 2173.79
     123 2164.56     147 2145.83   174.4 2127.35   225.5 2098.02   264.9 2073.15
   287.7    2054   311.8 2036.72   342.7 2012.06     353 2001.94   367.2 1983.68
     377 1976.48     383  1974.9   407.9 1973.12   418.2 1974.68   435.4  1979.8
   497.2 1976.89   510.9 1974.15   565.8 1987.02   590.3  1995.4   625.1 2010.03
   637.9 2013.41   727.2 2046.91   751.2 2053.96   764.9 2060.26   810.7 2075.61
#Mann= 3 ,-1 , 0
       0      .1       0     383    .045       0   418.2      .1       0
Bank Sta=383,418.2
XS Rating Curve= 0 ,0
Exp/Cntr=0.3,0.1

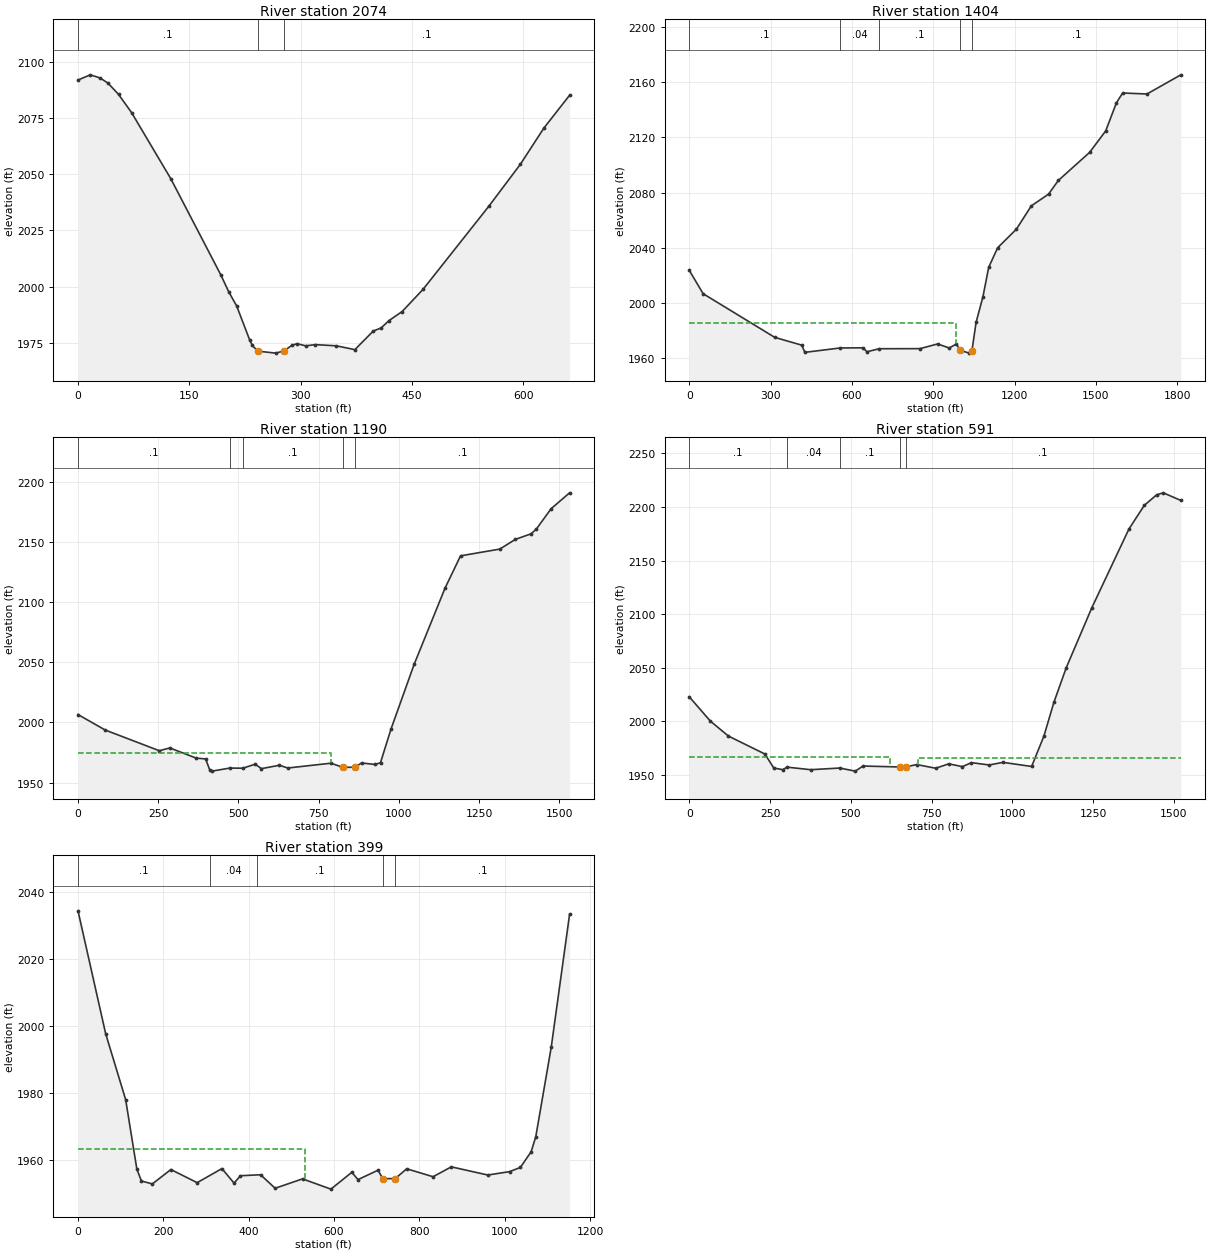
Type RM Length L Ch R = 1 ,2074    ,677.3,670,648.1
XS GIS Cut Line= 2
     2131672.588      236819.247     2131919.983      237433.397
#Sta/Elev= 30
       0 2091.85    16.6 2094.17    29.8 2092.76    40.4 2090.48    54.6 2085.48
    72.1 2077.42   125.1 2047.92   192.5 2005.14   203.1 1997.66   213.7 1991.43
   231.4 1976.16   234.9 1973.89     242 1971.35   266.3 1970.46   277.4 1971.45
     288 1973.91   295.1 1974.66   306.6 1973.71   319.8 1974.24   348.1  1973.7
   372.9 1972.01   397.6 1980.25   408.3 1981.68   418.9 1984.94   436.6 1988.95
   464.8 1998.84   553.3 2035.74   595.7 2054.36   627.6 2070.55   662.1 2085.09
#Mann= 3 ,-1 , 0
       0      .1       0     242    .045       0   277.4      .1       0
Bank Sta=242,277.4
XS Rating Curve= 0 ,0
Exp/Cntr=0.3,0.1

Type RM Length L Ch R = 1 ,1404    ,222,213.8,199.3
XS GIS Cut Line= 3
     2130579.402      236929.483     2131488.256      237476.358
     2132238.041      237542.655
#Sta/Elev= 30
       0 2023.73    51.2 2006.75   315.4 1975.11     415 1969.47   426.5 1964.25
   556.7 1967.42   640.9 1967.55   655.5 1964.68   700.9 1966.88   851.5 1966.94
   916.1 1970.34   959.1 1967.43   985.5  1970.3   999.7 1965.68  1033.2 1963.69
  1042.8  1965.4  1058.2 1986.05  1083.4 2004.53  1104.7 2025.89  1137.6 2040.02
  1206.8 2053.51  1261.9 2070.39  1325.5  2078.9  1361.6 2088.82  1476.9 2109.13
  1536.2 2124.67  1575.7 2145.01  1598.7 2152.16  1688.6 2151.45  1813.4 2165.33
#Mann= 5 ,-1 , 0
       0      .1       0   556.7     .04       0   700.9      .1       0
   999.7    .045       0  1042.8      .1       0
#XS Ineff= 2 , 0
          983.03 1985.24
Permanent Ineff=
       F       F
Bank Sta=999.7,1042.8
XS Rating Curve= 0 ,0
Exp/Cntr(USF)=0,0
Exp/Cntr=0.3,0.1

Type RM Length L Ch R = 1 ,1190    ,595.2,598.8,609.8
XS GIS Cut Line= 2
     2130488.256237604.450926843     2132019.291237651.650926843
#Sta/Elev= 30
       0 2006.57    84.9  1993.7   253.3 1976.51   286.1 1978.81   368.2 1970.38
   397.7 1969.67     410  1960.9   417.4 1959.55   473.2  1962.1   513.5 1961.97
     552 1965.32   571.7 1961.62   627.5 1964.43   653.7 1962.15   788.3 1966.14
   825.5 1962.67   863.7 1962.82   883.5 1966.35   926.2 1965.06   942.6 1966.61
   975.6 1994.73  1047.6 2048.45  1143.9 2111.78    1192 2138.49  1314.3 2144.11
  1362.7 2152.16    1412 2156.83  1428.4 2160.81  1474.3  2177.7  1531.8 2190.87
#Mann= 5 ,-1 , 0
       0      .1       0   473.2     .04       0   513.5      .1       0
   825.5    .045       0   863.7      .1       0
#XS Ineff= 2 , 0
           789.3 1974.33
Permanent Ineff=
       F       F
Bank Sta=825.5,863.7
XS Rating Curve= 0 ,0
Exp/Cntr(USF)=0,0
Exp/Cntr=0.3,0.1

Type RM Length L Ch R = 1 ,591     ,192,192,192
XS GIS Cut Line= 3
     2130511.694      238288.858     2130725.236      238288.858
     2131967.208       237879.46
#Sta/Elev= 30
       0 2022.81    65.7 1999.97   121.4 1986.09     234 1969.38   261.7 1956.27
   289.3 1954.76   303.1  1957.1   375.7 1954.71   465.5 1956.27   513.8 1953.38
     538 1958.14     652 1957.26   669.3 1957.19   703.8 1959.55   762.6 1956.07
   803.1 1960.18   845.5 1957.58   873.1  1961.3   928.4 1959.13   970.7 1961.57
  1059.6 1957.73  1097.6 1986.13  1128.7 2017.82  1166.7 2049.94  1245.9 2105.97
  1360.4  2179.3  1408.5 2201.66  1446.5 2211.38    1467 2213.25  1521.3 2206.15
#Mann= 5 ,-1 , 0
       0      .1       0   303.1     .04       0   465.5      .1       0
     652    .045       0   669.3      .1       0
#XS Ineff= 2 , 0
          620.23 1966.55  706.84         1966.03
Permanent Ineff=
       F       F
Bank Sta=652,669.3
XS Rating Curve= 0 ,0
Exp/Cntr(USF)=0,0
Exp/Cntr=0.3,0.1

Type RM Length L Ch R = 1 ,399     ,,,
XS GIS Cut Line= 2
2130609.86527312238599.465280482     2131653.056       238110.48
#Sta/Elev= 30
       0 2034.37    64.8 1997.71   111.7 1978.01     138 1957.24   148.7 1953.73
   174.3 1952.87   217.7 1957.16   279.3 1953.24   337.3 1957.44   365.8  1953.1
   380.8 1955.31   427.9  1955.6     462 1951.57   526.2 1954.37   592.7 1951.31
   641.7 1956.33   656.2 1954.15   703.3 1956.97   714.1 1954.43   743.3 1954.45
   770.4 1957.38   832.1 1955.01   874.9 1957.96   960.5 1955.52  1011.3 1956.53
  1036.6 1957.77    1062 1962.46  1072.9 1966.98  1109.1 1993.69  1152.1 2033.35
#Mann= 5 ,-1 , 0
       0      .1       0     310     .04       0     420      .1       0
   714.1    .045       0   743.3      .1       0
#XS Ineff= 2 , 0
          531.38 1963.34
Permanent Ineff=
       F       F
Bank Sta=714.1,743.3
XS Rating Curve= 0 ,0
Exp/Cntr=0.3,0.1
LCMann Table=0

Chan Stop Cuts=-1
Use User Specified Reach Order=0
Composite Channel Slope=5